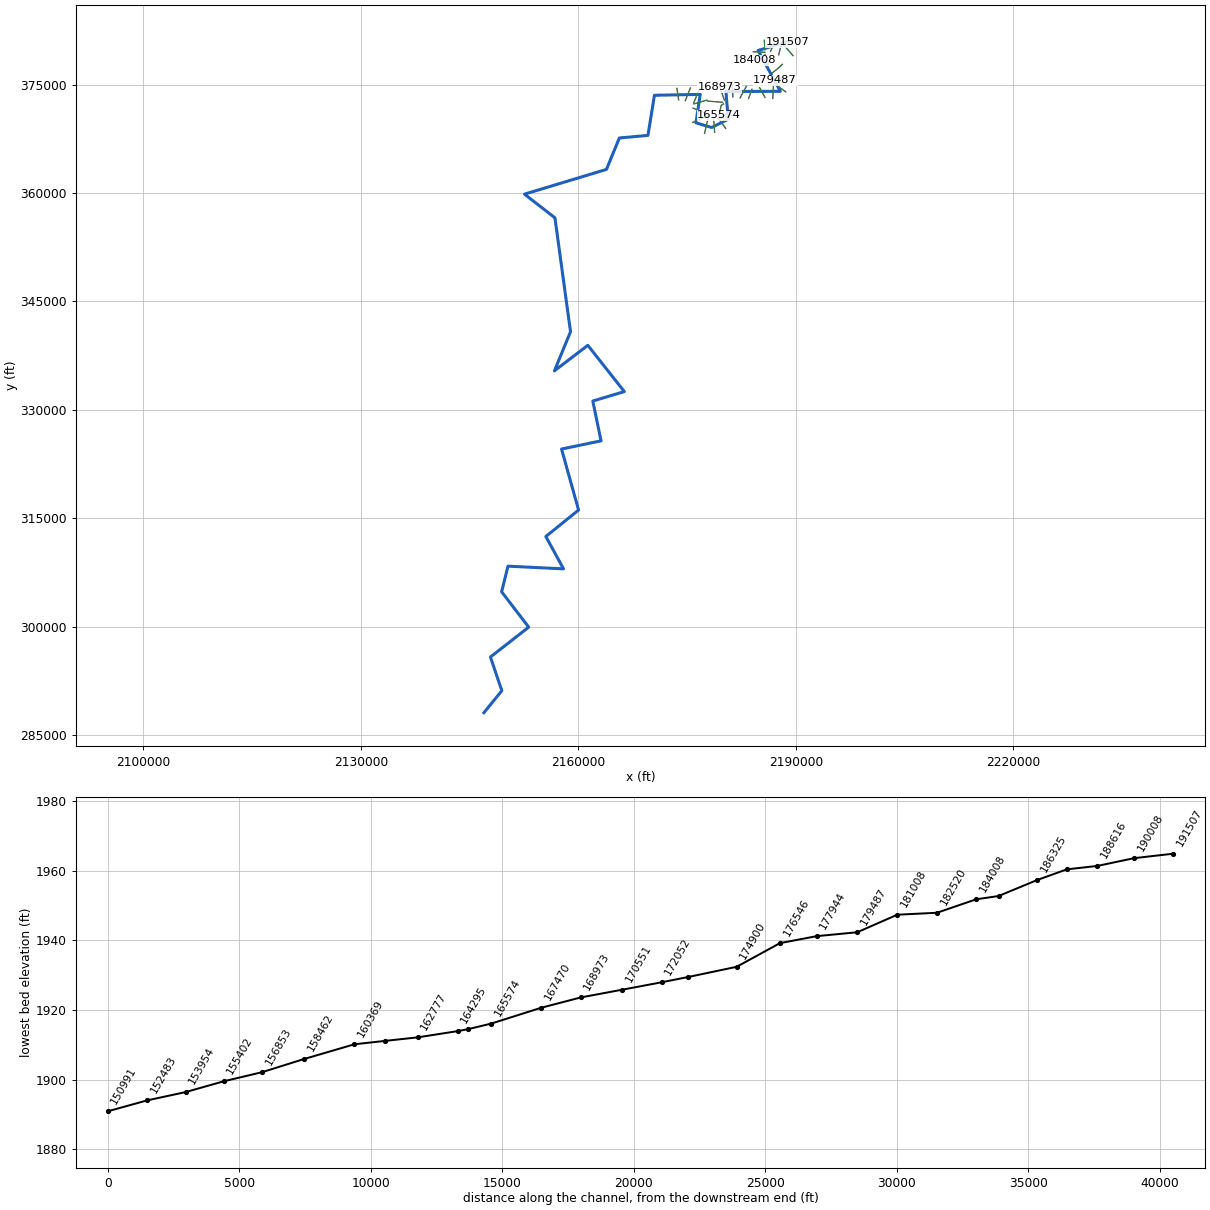
--- GRBRRV5.prj (project) ---

Proj Title=GRBRRV5
Current Plan=p01
Default Exp/Contr=0,0
English Units
Geom File=g01
Flow File=f01
Plan File=p01
BEGIN DESCRIPTION:
Stream Name- Greenbrier River 5
Flood Zone: Zone A
Greenbrier County, WV
County-Wide Study
WVDHSEM-2018-3, Flood Risk Project
HEC-RAS Version: 5.0.7
General Notes:
For the Hydrology gage weighting was used.
END DESCRIPTION:
DSS Export Rating Curves= 0
DSS Export Rating Curve Sorted= 0
DSS Export Volume Flow Curves= 0
DXF OffsetX= 0
DXF OffsetY= 0
DXF ScaleX= 0
DXF ScaleY= 0

--- GRBRRV5.p01 (plan) ---

Plan Title=Floodplain
Program Version=5.07
Short Identifier=Floodplain
Geom File=g01
Flow File=f01
Subcritical Flow
K Sum by GR= 0
Std Step Tol= 0.01
Critical Tol= 0.01
Num of Std Step Trials= 20
Max Error Tol= 0.3
Flow Tol Ratio= 0.001
Split Flow NTrial= 30
Split Flow Tol= 0.02
Split Flow Ratio= 0.02
Log Output Level= 0
Friction Slope Method= 1
Unsteady Friction Slope Method= 2
Unsteady Bridges Friction Slope Method= 1
Parabolic Critical Depth
Global Vel Dist= 0 , 0 , 0
Global Log Level= 0
CheckData=True
Encroach Param=-1 ,0,0, 0
Mapping Interval=1HOUR
Computation Time Step Use Courant=        0
Computation Time Step Use Time Series=    0
Computation Time Step Count To Double=0
Computation Time Step Max Doubling=0
Computation Time Step Max Halving=0
Computation Time Step Residence Courant=0
Run HTab= 0
Run UNet= 0
Run Sediment= 0
Run PostProcess= 0
Run WQNet= 0
Run RASMapper= 0
UNET Theta= 0
UNET Theta Warmup= 0
UNET ZTol= 0
UNET ZSATol= 0
UNET MxIter= 0
UNET Max Iter WO Improvement= 0
UNET MaxInSteps= 0
UNET DtIC= 0
UNET DtMin= 0
UNET MaxCRTS= 0
UNET WFStab= 0
UNET SFStab= 0
UNET WFX= 1
UNET SFX= 1
UNET 1D Methodology=Finite Difference
UNET DSS MLevel= 1
UNET Pardiso=0
UNET DZMax Abort= 0
UNET Use Existing IB Tables= 0
UNET Froude Reduction=False
UNET Froude Limit= 0
UNET Froude Power= 0
UNET D1 Cores= 0
UNET D2 Coriolis=0
UNET D2 Cores= 0
UNET D2 Theta= 1
UNET D2 Theta Warmup= 1
UNET D2 Z Tol= 0.01
UNET D2 Volume Tol= 0.01
UNET D2 Max Iterations= 20
UNET D2 Equation= 0
UNET D2 RampUpFraction=0.1
UNET D2 TimeSlices= 1
UNET D2 BCVolumeCheck=0
UNET D1D2 MaxIter= 0
UNET D1D2 ZTol=0.01
UNET D1D2 QTol=0.1
UNET D1D2 MinQTol=1
Write IC File= 0
Write IC File at Fixed DateTime=0
Write IC File at Sim End=0
Echo Input=False
Echo Parameters=False
Echo Output=False
Write Detailed= 0
HDF Write Warmup=0
HDF Write Time Slices=0
HDF Flush=0
HDF Face Node Velocities=0
HDF Compression= 1
HDF Chunk Size= 1
HDF Spatial Parts= 1
HDF Use Max Rows=0
HDF Fixed Rows= 1
Calibration Method= 0
Calibration Iterations= 20
Calibration Max Change=0.05
Calibration Tolerance=0.2
Calibration Maximum=1.5
Calibration Minimum=0.5
Calibration Optimization Method= 1
WQ AD Non Conservative
WQ ULTIMATE=-1
WQ Max Comp Step=1HOUR
WQ Output Interval=15MIN
WQ Output Selected Increments= 0
WQ Output face flow=0
WQ Output face velocity=0
WQ Output face area=0
WQ Output face dispersion=0
WQ Output cell volume=0
WQ Output cell surface area=0
WQ Output cell continuity=0
WQ Output cumulative cell continuity=0
WQ Output face conc=0
WQ Output face dconc_dx=0
WQ Output face courant=0
WQ Output face peclet=0
WQ Output face adv mass=0
WQ Output face disp mass=0
WQ Output cell mass=0
WQ Output cell source sink temp=0
WQ Output nsm pathways=0
WQ Output nsm derived pathways=0
WQ Output MaxMinRange=-1
WQ Daily Max Min Mean=-1
WQ Daily Range=0
WQ Daily Time=0
WQ Create Restart=0
WQ Fixed Restart=0
WQ System Summary=0
WQ Write To DSS=0
WQ Use Fixed Temperature=0
Sorting and Armoring Iterations= 10
XS Update Threshold= 0.02
Bed Roughness Predictor= 0
Hydraulics Update Threshold= 0.02
Energy Slope Method= 1
Volume Change Method= 1
Sediment Retention Method= 0
XS Weighting Method= 0
Number of US Weighted Cross Sections= 1
Number of DS Weighted Cross Sections= 1
Upstream XS Weight=0
Main XS Weight=1
Downstream XS Weight=0
Number of DS XS's Weighted with US Boundary= 1
Upstream Boundary Weight= 1
Weight of XSs Associated with US Boundary= 0
Number of US XS's Weighted with DS Boundary= 1
Downstream Boundary Weight= 0.5
Weight of XSs Associated with DS Boundary= 0.5
Percentile Method= 0
Sediment Output Level= 3
Mass or Volume Output= 0
Output Increment Type= 1
Profile and TS Output Increment= 1
XS Output Flag= 0
XS Output Increment= 10
Write Gradation File= 0
Read Gradation Hotstart= 0
Write HDF5 File= 1
Write Binary Output= 1
Write DSS Sediment File= 0
SV Curve= 0
Specific Gage Flag= 0

--- GRBRRV5.f01 (steady flow) ---

Flow Title=Flow
Program Version=5.07
Number of Profiles= 6
Profile Names=Flow1p,Flow10p,Flow4p,Flow2p,Flow02p,Flow1pplus
River Rch & RM=GRBRRV5,Main            ,191507
   60300   36700   45500   52700   80500   70100
River Rch & RM=GRBRRV5,Main            ,104508
   67600   45500   54500   61100   83200   74900
Boundary for River Rch & Prof#=GRBRRV5,Main            , 1
Up Type= 0
Dn Type= 1
Dn Known WS=1696.34
Boundary for River Rch & Prof#=GRBRRV5,Main            , 2
Up Type= 0
Dn Type= 1
Dn Known WS=1691.8
Boundary for River Rch & Prof#=GRBRRV5,Main            , 3
Up Type= 0
Dn Type= 1
Dn Known WS=1693.71
Boundary for River Rch & Prof#=GRBRRV5,Main            , 4
Up Type= 0
Dn Type= 1
Dn Known WS=1695.04
Boundary for River Rch & Prof#=GRBRRV5,Main            , 5
Up Type= 0
Dn Type= 1
Dn Known WS=1699.52
Boundary for River Rch & Prof#=GRBRRV5,Main            , 6
Up Type= 0
Dn Type= 1
Dn Known WS=1697.82
Set Internal Change=GRBRRV5         ,Main            ,695     , 6 , 3 ,1697.67
Set Internal Change=GRBRRV5         ,Main            ,695     , 5 , 3 ,1698.55
Set Internal Change=GRBRRV5         ,Main            ,695     , 4 , 3 ,1694.38
Set Internal Change=GRBRRV5         ,Main            ,695     , 3 , 3 ,1693.06
Set Internal Change=GRBRRV5         ,Main            ,695     , 2 , 3 ,1691.18
Set Internal Change=GRBRRV5         ,Main            ,695     , 1 , 3 ,1695.62
DSS Import GetInterval= 0
DSS Import GetPeak= 0
DSS Import FillOption= 0

--- GRBRRV5.g01 (geometry) ---

Geom Title=Geometry
Program Version=5.07

River Reach=GRBRRV5         ,Main
Reach XY= 30
     2189236.753      381067.641      2184787.83      379736.384
     2187862.483      374080.134     2180352.066       374050.62
     2180670.627      370230.493     2178391.997      369071.453
     2176215.997       369721.17     2176808.664      373654.787
     2170490.955      373529.787     2169598.594       367979.44
      2165654.15      367620.065     2163872.899       363269.37
     2152565.495      359844.396     2156765.147       356570.09
     2158916.129      340799.013      2156692.17      335385.819
     2161301.545      338922.278     2166338.004      332521.236
     2161989.046      331210.472     2163127.934      325698.319
     2157678.281      324564.638      2160027.24       316121.93
     2155513.351      312462.208     2157950.851      307981.306
     2150287.656      308352.833     2149409.183      304811.166
     2153148.768      299913.597     2147869.253       295778.18
     2149442.171      291114.9862146961.29709689 288063.66332717

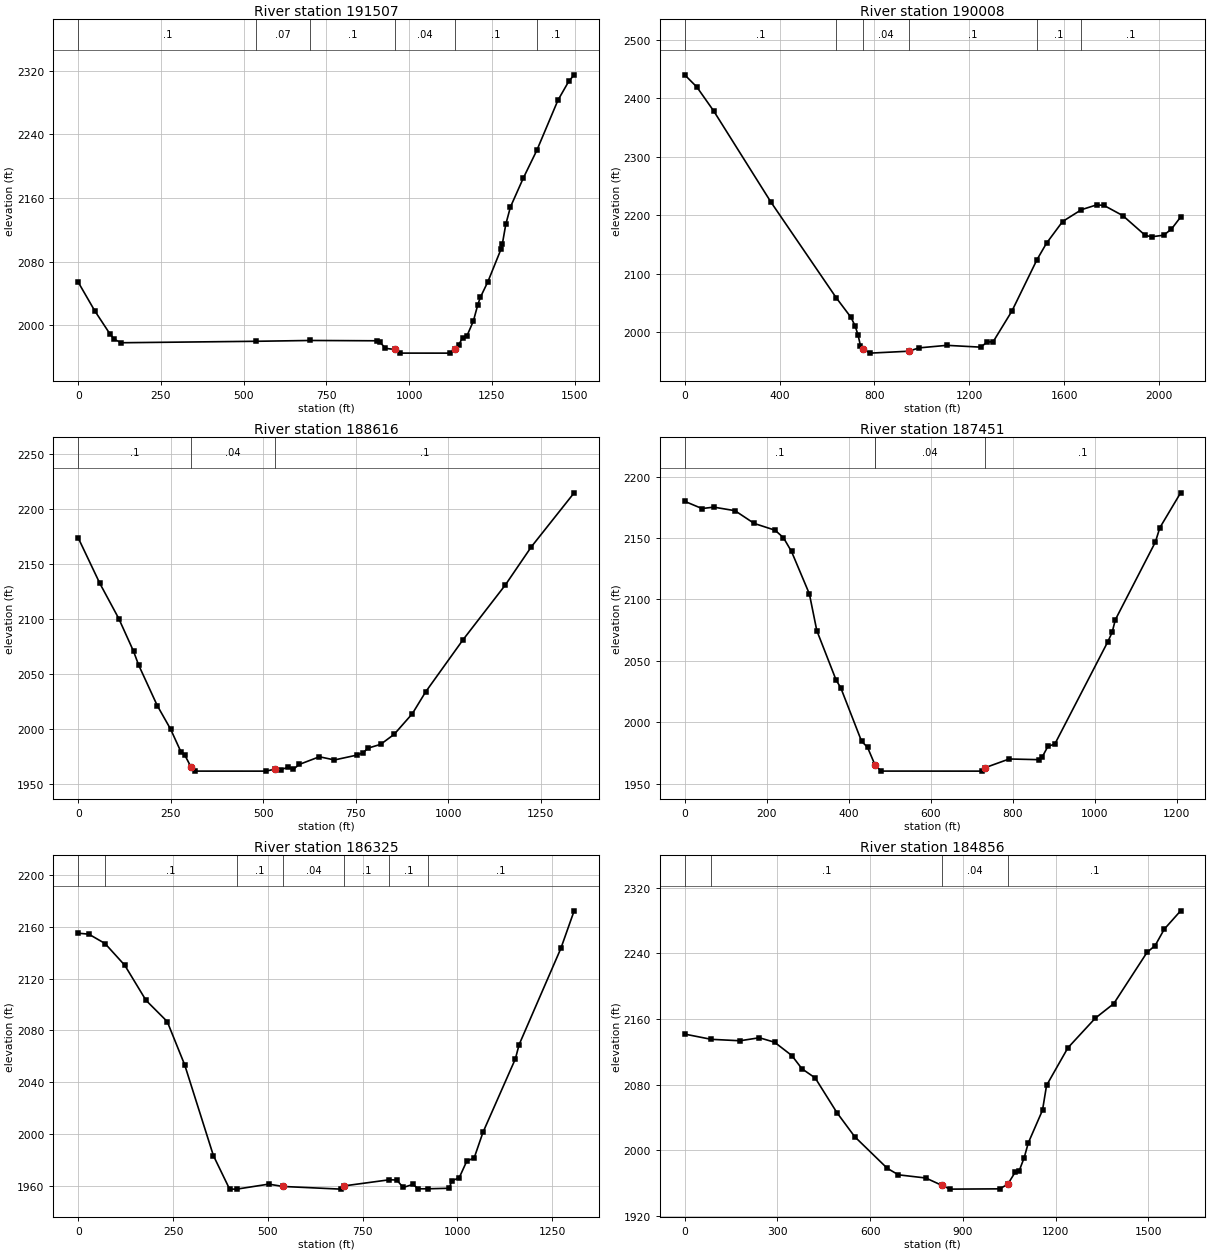
Type RM Length L Ch R = 1 ,191507  ,1603.8,1499.5,1374.9
XS GIS Cut Line= 2
2190206.07548683381416.2196352762188800.90518397380894.785945729
#Sta/Elev= 30
       0 2054.14    49.9 2018.15    95.4 1989.31   109.4 1982.07   130.4 1977.94
  538.741979.779   700.91980.796   903.6 1980.41   910.8 1979.28   928.3 1970.96
   956.3 1969.47   973.8 1964.91  1124.3 1964.88  1138.7 1970.07  1149.4 1974.87
  1161.7 1984.32  1174.5 1986.26  1194.3 2005.34  1207.6 2025.74  1215.2  2034.9
  1238.3 2054.91  1278.2 2096.12  1281.7 2101.94  1292.2 2126.93  1306.2 2148.64
  1344.7 2184.68 1386.142220.104  1449.7 2282.88  1482.2 2306.58  1498.8 2314.94
#Mann= 6 ,-1 , 0
       0      .1       0  538.74     .07       0   700.9      .1       0
   956.3     .04       0  1138.7      .1       0 1386.14      .1       0
Bank Sta=956.3,1138.7
XS Rating Curve= 0 ,0
Exp/Cntr=0.3,0.1

Type RM Length L Ch R = 1 ,190008  ,1487.7,1392.1,1297.2
XS GIS Cut Line= 3
     2189607.863      379011.495     2189061.209      379664.832
      2188233.66      380587.405
#Sta/Elev= 30
       0 2440.45    51.3 2419.55   122.4 2378.49     364  2222.2  639.782058.025
   701.1 2024.95     719  2009.9   731.4 1994.09     741 1976.47   752.3 1970.24
   781.9 1963.59   944.2 1966.86   988.2 1972.58  1105.7 1976.93  1248.3 1973.82
  1274.7 1982.37  1301.2 1983.43  1379.9 2035.72 1485.722123.865  1525.9 2152.05
  1593.6 2189.13 1673.022209.377  1737.6 2217.65  1768.3 2216.63  1847.7 2199.15
  1942.1 2165.35  1968.8 2162.97  2019.6  2165.6  2052.3 2176.03  2091.2 2196.73
#Mann= 6 ,-1 , 0
       0      .1       0  639.78      .1       0   752.3     .04       0
   944.2      .1       0 1485.72      .1       0 1673.02      .1       0
Bank Sta=752.3,944.2
XS Rating Curve= 0 ,0
Exp/Cntr=0.3,0.1

Type RM Length L Ch R = 1 ,188616  ,1189.1,1164.3,1148
XS GIS Cut Line= 2
2187640.11966652379131.9722097072187948.86113598380436.005685585
#Sta/Elev= 30
       0 2173.41    58.5 2131.98   109.6 2100.06   149.6 2070.25     163 2058.01
   213.6 2020.95   249.7 1999.48   277.7  1978.8   287.8 1976.07   304.6 1965.19
   314.8 1961.38   506.9 1961.36   530.5 1963.05   547.4 1962.69   567.3 1964.93
   581.1    1963   597.5 1967.46   651.7 1974.42   692.4 1971.52   753.1 1975.93
   769.9 1978.19   783.4 1982.29   817.1 1985.68   853.8 1994.85   902.9 2013.59
   938.5 2033.25  1039.6 2080.71  1154.3 2130.67  1224.5 2165.34  1340.1 2214.38
#Mann= 3 , 0 , 0
       0      .1       0   304.6     .04       0   530.5      .1       0
Bank Sta=304.6,530.5
XS Rating Curve= 0 ,0
Exp/Cntr=0.3,0.1

Type RM Length L Ch R = 1 ,187451  ,1083.4,1126.6,1186
XS GIS Cut Line= 2
2186506.83047087379623.2822624872187028.61788259380714.292305167
#Sta/Elev= 30
       0 2179.84    42.2 2173.95      71  2175.1   122.7 2172.21   169.5 2161.84
   220.4 2156.34   240.8 2150.26   260.5 2139.04   304.1 2104.52   322.2 2074.69
   369.5 2034.27   380.4 2028.36   431.3 1984.72   445.9 1979.73   464.1 1965.44
   464.6 1965.19   479.4 1960.42   724.4 1960.38   733.2 1963.25   791.4 1970.26
   863.2 1969.71   871.4 1971.59   885.9 1980.59   902.6 1982.37  1031.4 2065.33
  1042.3 2073.17  1050.2 2083.51  1147.8 2146.68  1158.7 2158.34  1209.4 2186.74
#Mann= 4 ,-1 , 0
       0      .1       0   464.1      .1       0   464.6     .04       0
   733.2      .1       0
Bank Sta=464.6,733.2
XS Rating Curve= 0 ,0
Exp/Cntr=0.3,0.1

Type RM Length L Ch R = 1 ,186325  ,1333.1,1468.4,1605.9
XS GIS Cut Line= 2
2185742.87141257379834.1852250212185643.50948057 381138.04693044
#Sta/Elev= 30
       0  2155.1    28.1 2154.34   70.712147.115   122.8 2130.29   178.7 2103.23
   234.7 2086.81   280.7 2053.38   356.4 1983.23   399.2 1957.31  418.191957.318
     502 1961.16   540.7 1959.36     692 1957.31   701.9 1959.84  820.731964.552
   840.1 1964.34   856.6 1958.59   882.9 1960.99     896 1957.56  922.311957.573
   978.3 1957.98   984.9 1963.66  1004.6 1966.14  1024.4  1978.9  1044.1 1981.51
  1067.1 2001.14  1152.7 2058.04  1162.4 2068.93  1272.5 2143.32  1307.6 2172.39
#Mann= 7 ,-1 , 0
       0      .1       0   70.71      .1       0  418.19      .1       0
   540.7     .04       0   701.9      .1       0  820.73      .1       0
  922.31      .1       0
Bank Sta=540.7,701.9
XS Rating Curve= 0 ,0
Exp/Cntr=0.3,0.1

Type RM Length L Ch R = 1 ,184856  ,794.9,848.5,896.8
XS GIS Cut Line= 2
2185732.05522317379487.3013006452184128.74481262379547.385911692
#Sta/Elev= 30
       0 2141.73   85.872135.352   179.2  2133.6   241.6 2137.28   290.8 2131.81
   346.7 2115.55   379.5 2099.41   422.2 2088.26   492.5 2045.98   550.2 2016.58
   655.3 1978.14   691.4 1970.15     780 1966.28   832.6 1957.22   858.8 1952.71
  1019.7 1953.05  1045.6 1958.91  1068.9 1973.21  1082.1 1974.97  1098.5 1991.25
  1111.6 2009.09  1157.6 2048.93  1170.7 2079.18  1239.7 2124.98  1328.3 2161.12
  1388.1 2178.84  1495.7 2241.34    1522 2249.68  1551.6 2269.71  1604.4 2292.02
#Mann= 4 ,-1 , 0
       0      .1       0   85.87      .1       0   832.6     .04       0
  1045.6      .1       0
Bank Sta=832.6,1045.6
XS Rating Curve= 0 ,0
Exp/Cntr=0.3,0.1

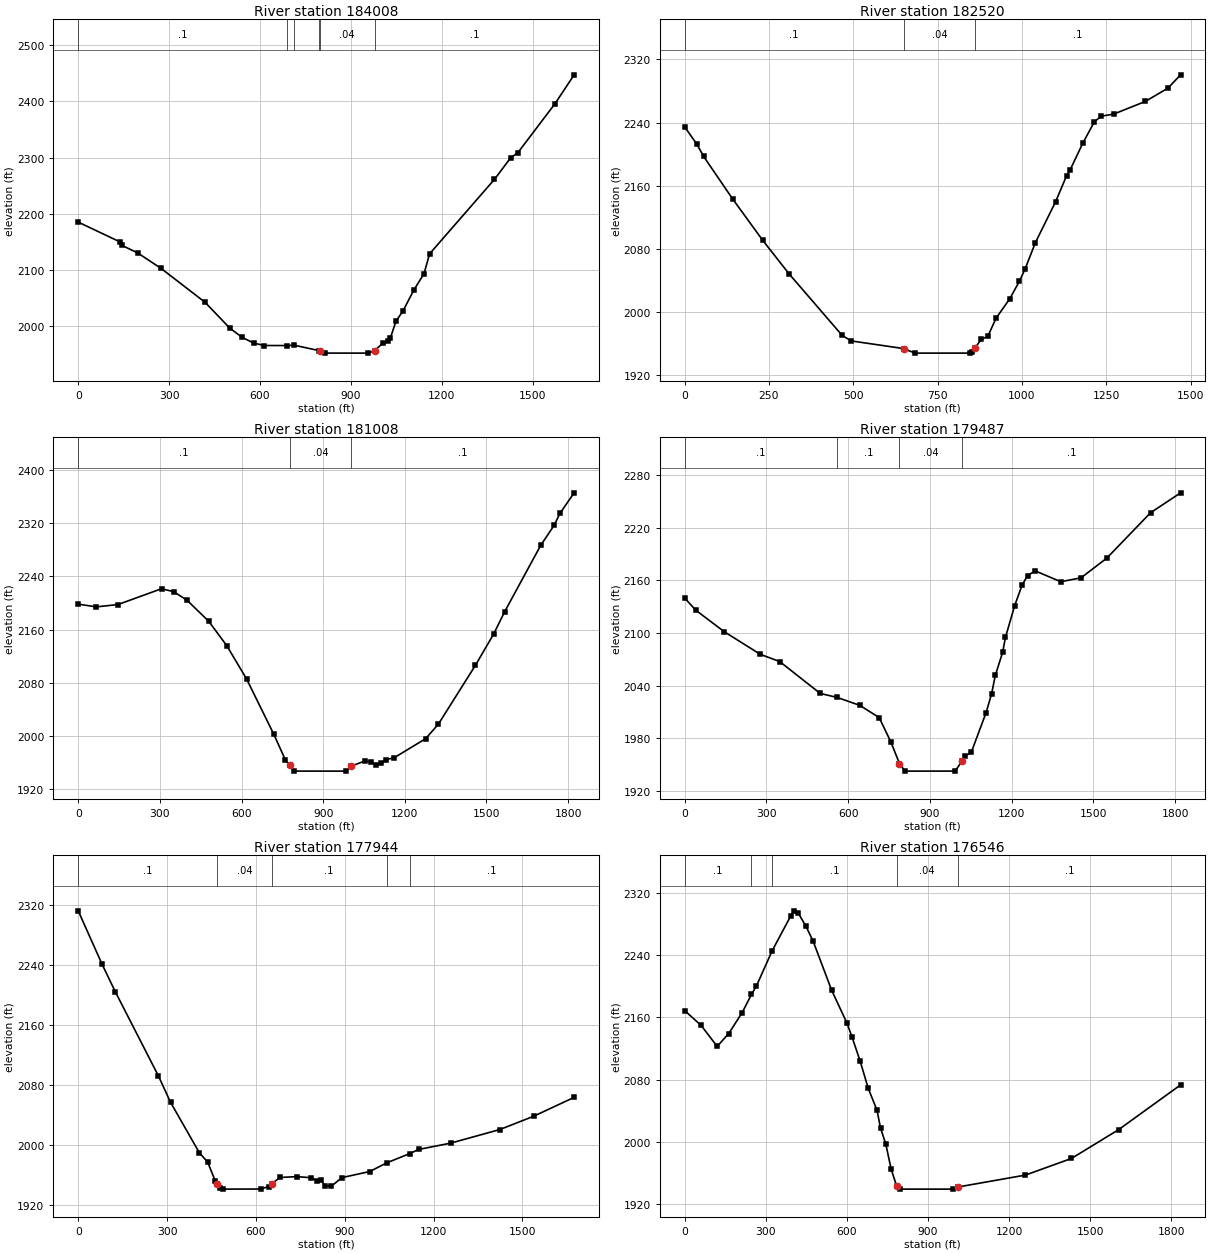
Type RM Length L Ch R = 1 ,184008  ,1403.4,1488.2,1555
XS GIS Cut Line= 2
2185770.00339857379117.3065905192184315.32334166378367.830126417
#Sta/Elev= 30
       0 2185.02   137.2 2149.91   144.5 2143.47   196.2 2130.18   273.7 2102.46
   418.6 2042.23   500.1  1996.3   541.5 1979.66   578.4 1969.85   613.2 1965.35
  687.791965.238  712.191965.923   794.8 1956.25   796.4 1955.56   814.3 1951.85
   956.4 1951.78   978.6 1956.32  1006.8 1970.37  1022.9 1972.92  1030.3 1979.21
  1048.7 2008.87  1070.9 2026.15  1107.8  2064.4    1141  2093.2  1159.4  2128.5
  1373.5 2261.12  1426.7 2299.33  1450.1 2308.15  1572.8 2395.48  1636.4 2447.17
#Mann= 6 ,-1 , 0
       0      .1       0  687.79      .1       0  712.19      .1       0
   794.8      .1       0   796.4     .04       0   978.6      .1       0
Bank Sta=796.4,978.6
XS Rating Curve= 0 ,0
Exp/Cntr=0.3,0.1

Type RM Length L Ch R = 1 ,182520  ,1581.1,1511.9,1457.6
XS GIS Cut Line= 2
2186456.23290367378750.4742283422186029.31593045377343.229390682
#Sta/Elev= 30
       0 2234.53      36 2212.59    56.1 2197.12   141.8 2143.47   230.9 2091.08
   309.5 2048.33   466.9  1970.4   493.7 1963.38   648.9  1953.7   683.1 1947.91
   846.2 1947.96   851.7 1949.01   861.9 1954.84   878.9 1965.31   898.8 1969.12
   923.5 1992.24   964.2  2016.9   992.1 2038.64  1009.4 2054.51  1040.1 2088.02
  1099.8 2139.61  1132.6 2172.74  1142.9 2179.98  1180.6 2213.89  1214.9 2241.01
  1235.4 2248.07  1272.3  2250.7  1365.8 2266.68  1432.8 2283.53  1470.6 2300.42
#Mann= 3 , 0 , 0
       0      .1       0   648.9     .04       0   861.9      .1       0
Bank Sta=648.9,861.9
XS Rating Curve= 0 ,0
Exp/Cntr=0.3,0.1

Type RM Length L Ch R = 1 ,181008  ,1574.3,1520.5,1471.7
XS GIS Cut Line= 3
     2188138.196      377807.595     2187465.869      377195.085
     2186748.899      376630.098
#Sta/Elev= 30
       0 2198.11    66.5    2194     146 2197.49   306.1 2221.26   350.6 2216.82
   399.5 2204.07   479.2 2172.53   545.5 2135.98   618.6 2085.79   718.9 2002.49
   761.6 1963.84   777.6 1956.16   794.3  1947.4   985.2 1947.35  1003.7 1954.96
  1052.8 1962.49  1075.3 1961.52  1092.5 1955.96  1114.4 1958.91  1131.1 1964.74
  1160.1 1967.23  1276.7 1996.14  1323.3 2017.85  1459.3  2106.1    1527 2153.57
  1566.7 2186.58  1699.2 2286.26  1748.5 2316.33  1770.2 2334.52  1822.3 2365.27
#Mann= 3 , 0 , 0
       0      .1       0   777.6     .04       0  1003.7      .1       0
Bank Sta=777.6,1003.7
XS Rating Curve= 0 ,0
Exp/Cntr=0.3,0.1

Type RM Length L Ch R = 1 ,179487  ,1631.1,1543.4,1466.5
XS GIS Cut Line= 2
      2188896.45      376052.214     2187130.793       375608.89
#Sta/Elev= 30
       0 2139.79    40.9 2125.93   145.3 2101.41   277.7 2075.58   348.9 2067.36
   497.5 2030.98  559.372026.437     643 2017.35   714.1 2003.39   757.1 1975.44
   788.5 1950.94   808.8 1942.31   992.4 1942.36  1018.5 1953.73  1028.7 1959.23
  1052.3 1963.97  1106.5 2009.12  1126.7 2030.65  1140.3 2051.55  1167.3 2078.04
  1177.5 2094.99  1211.2 2131.07  1238.3 2154.39  1258.7 2165.55  1287.1  2170.8
  1380.4 2158.47  1454.9  2162.9  1549.6  2185.4    1710 2237.15  1820.5 2259.91
#Mann= 4 ,-1 , 0
       0      .1       0  559.37      .1       0   788.5     .04       0
  1018.5      .1       0
Bank Sta=788.5,1018.5
XS Rating Curve= 0 ,0
Exp/Cntr=0.3,0.1

Type RM Length L Ch R = 1 ,177944  ,1503.8,1398,1312.2
XS GIS Cut Line= 2
2188603.46716158374003.7899556962187249.98223907374990.442516033
#Sta/Elev= 30
       0 2311.94    80.4 2240.93   124.9 2204.41   270.6 2092.22   311.8 2056.85
   409.1 1989.66   437.3 1977.15   463.1 1951.66   470.2 1947.64   478.2 1943.05
     489 1941.19   616.3 1941.34   642.9 1944.54   652.8 1947.95   681.2 1956.72
   738.1 1957.84   786.8  1956.4     806 1952.28   820.1 1952.82   834.1  1945.6
   855.3 1945.26   890.5  1956.5   984.4 1964.64 1042.17 1976.21 1119.131988.455
  1149.7 1994.05  1257.8 2002.45  1424.2  2020.6  1537.9 2038.24  1674.9 2063.45
#Mann= 5 ,-1 , 0
       0      .1       0   470.2     .04       0   652.8      .1       0
 1042.17      .1       0 1119.13      .1       0
Bank Sta=470.2,652.8
XS Rating Curve= 0 ,0
Exp/Cntr=0.3,0.1

Type RM Length L Ch R = 1 ,176546  ,1579.7,1646.2,1692.5
XS GIS Cut Line= 2
2186819.01559833373091.1849603912186909.50259833374923.678960391
#Sta/Elev= 30
       0 2168.59    61.1 2149.48   120.2 2122.59   162.9 2139.14   212.2 2165.73
  247.14 2189.39   264.7 2199.67  323.452245.338   392.8 2290.57     406 2296.81
   419.1  2294.5   448.7 2276.93   474.9 2258.06   543.9 2194.59   599.5 2153.17
   618.9 2134.85   649.1 2103.73   678.9 2068.86   711.5 2040.54   724.6 2017.64
   744.1 1997.01     764 1964.56   783.7 1943.73   796.9 1939.22     994 1939.18
  1010.7  1941.9  1260.6 1957.23  1430.9  1978.6    1605 2015.52  1834.7 2073.15
#Mann= 5 ,-1 , 0
       0      .1       0  247.14      .1       0  323.45      .1       0
   783.7     .04       0  1010.7      .1       0
Bank Sta=783.7,1010.7
XS Rating Curve= 0 ,0
Exp/Cntr=0.3,0.1

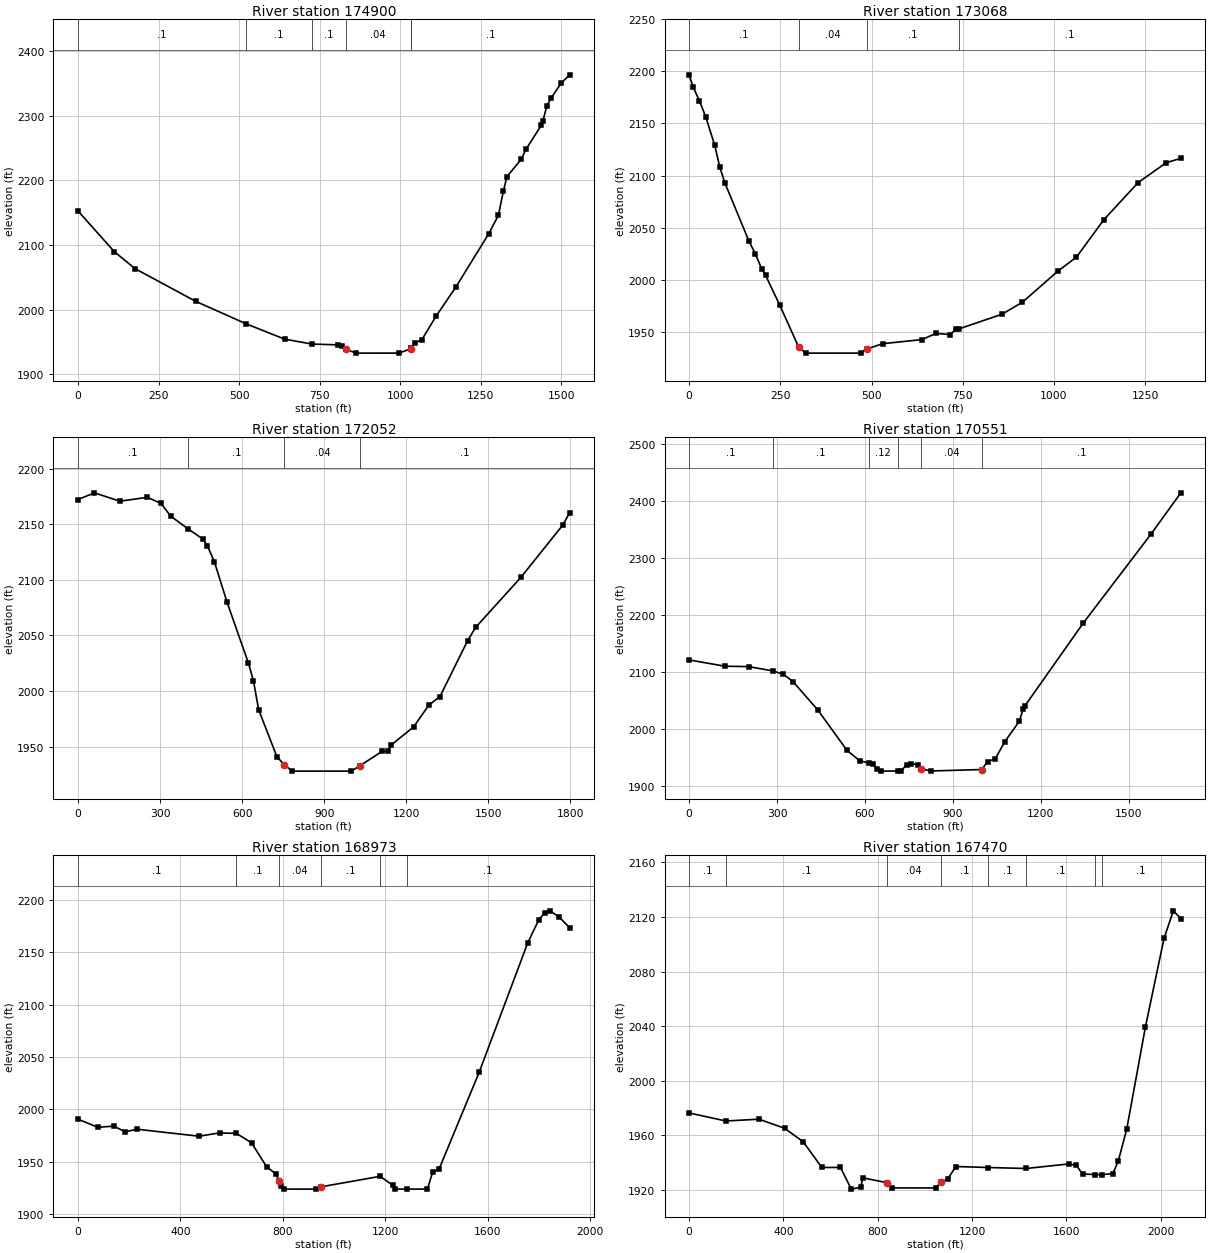
Type RM Length L Ch R = 1 ,174900  ,1925.3,1831.5,1764.9
XS GIS Cut Line= 2
2185747.86696292373243.7723317612185002.95833474 374575.47219062
#Sta/Elev= 30
       0  2152.7   113.1 2089.47   177.5  2063.2   365.2 2012.67  521.941977.791
   641.2 1954.07   725.61946.459   807.8 1945.18   819.8  1943.5   830.5 1938.13
   864.2 1932.38   996.5 1932.43    1033 1939.23  1034.1 1939.79  1046.6 1948.61
  1066.7 1952.79  1111.6 1989.88  1172.8 2034.87  1274.1 2116.96  1304.8 2145.96
  1319.9 2182.94  1331.1 2205.88  1375.3 2232.64  1391.2 2248.98    1438 2285.65
  1442.8 2292.12  1455.1  2315.8  1469.3 2328.48  1500.3 2351.32  1525.9 2363.75
#Mann= 6 ,-1 , 0
       0      .1       0  521.94      .1       0   725.6      .1       0
   830.5     .04       0    1033      .1       0  1034.1      .1       0
Bank Sta=830.5,1033
XS Rating Curve= 0 ,0
Exp/Cntr=0.3,0.1

Type RM Length L Ch R = 1 ,173068  ,1032.6,1016.6,1008.3
XS GIS Cut Line= 2
2183482.65955788373089.6254378082183939.44315063374358.078337671
#Sta/Elev= 30
       0 2196.73    10.7 2184.97    28.1 2171.93    45.6 2156.19      70 2129.15
    83.9 2108.19    97.9 2092.98   164.3 2036.67   181.6 2024.72     199 2010.27
   209.5 2004.16   247.8 1976.04   300.5    1935   320.7 1929.49     471 1929.47
   487.4 1933.41   530.3 1938.53   638.4 1942.48   676.7 1948.43   715.1 1947.32
   732.5 1952.51  740.98 1952.89   858.1 1966.85   913.9  1978.4  1011.5 2008.34
  1061.7 2021.57    1137 2057.56  1231.2 2093.27  1307.9 2112.31  1348.2 2116.52
#Mann= 4 ,-1 , 0
       0      .1       0   300.5     .04       0   487.4      .1       0
  740.98      .1       0
Bank Sta=300.5,487.4
XS Rating Curve= 0 ,0
Exp/Cntr=0.3,0.1

Type RM Length L Ch R = 1 ,172052  ,1424.8,1500.4,1560.7
XS GIS Cut Line= 2
2182304.59011378373168.2105869082183156.93142873374750.231551546
#Sta/Elev= 30
       0  2172.3    60.1 2178.33   153.1 2170.79   253.8 2174.29   303.3 2168.76
   339.6  2157.2  402.832145.771   455.9 2136.82   472.8 2130.75   498.8  2116.1
   544.5  2080.1     623 2025.08   641.4 2009.08   660.1 1983.35     727 1940.86
   754.7 1933.56     783 1927.94   999.2 1927.94  1031.4 1932.99    1111 1945.64
  1133.4 1945.71  1144.5 1951.39  1226.5 1967.71  1282.4 1987.33  1322.9 1995.04
    1424 2045.32  1453.3 2057.25  1618.4 2102.17  1771.5 2149.22    1797 2160.43
#Mann= 4 ,-1 , 0
       0      .1       0  402.83      .1       0   754.7     .04       0
  1031.4      .1       0
Bank Sta=754.7,1031.4
XS Rating Curve= 0 ,0
Exp/Cntr=0.3,0.1

Type RM Length L Ch R = 1 ,170551  ,1532.3,1578,1595.8
XS GIS Cut Line= 2
2181317.59556041      373313.0222181233.01607312374989.059309327
#Sta/Elev= 30
       0 2121.03   121.5 2110.04   203.4  2109.3  286.442101.694   321.9  2095.7
   354.7 2082.93   440.1 2032.48   538.7 1962.24   581.8 1944.12  612.271940.142
   627.4 1938.56   640.5 1929.31   653.6 1925.81  711.87 1926.06   722.6 1926.27
   742.3 1936.63   758.8 1938.74   781.8  1937.4   791.6 1930.02   824.5 1926.06
   998.6 1928.63  1018.3 1942.41  1044.6 1947.41  1077.4 1977.58  1126.7 2013.08
  1139.8 2034.76  1146.4 2040.68  1345.5 2186.02  1576.2 2341.84  1678.2 2414.44
#Mann= 6 ,-1 , 0
       0      .1       0  286.44      .1       0  612.27     .12       0
  711.87      .1       0   791.6     .04       0   998.6      .1       0
Bank Sta=791.6,998.6
XS Rating Curve= 0 ,0
Exp/Cntr=0.3,0.1

Type RM Length L Ch R = 1 ,168973  ,1379.3,1503.3,1611.6
XS GIS Cut Line= 2
2180146.02810336 372836.23259482 2179520.1390935374652.044596646
#Sta/Elev= 30
       0 1990.48    77.4 1982.79   139.9 1983.82     185 1978.42   230.1  1980.9
   472.8 1974.19   552.8 1977.38  618.821976.875   677.8 1967.92   736.7 1944.97
   774.9 1937.76   784.9    1931   792.3 1926.74   806.2 1923.62   931.1 1923.58
   948.4 1925.76 1180.431935.811  1229.5  1927.3  1239.9 1923.59 1283.73  1923.6
  1364.9 1923.62  1385.7 1939.92    1410 1942.44  1567.2 2035.39    1757 2159.25
  1799.4 2180.91  1822.9 2188.12  1843.8 2189.85  1878.5 2184.11  1920.7 2173.75
#Mann= 6 ,-1 , 0
       0      .1       0  618.82      .1       0   784.9     .04       0
   948.4      .1       0 1180.43      .1       0 1283.73      .1       0
Bank Sta=784.9,948.4
XS Rating Curve= 0 ,0
Exp/Cntr=0.3,0.1

Type RM Length L Ch R = 1 ,167470  ,1751.7,1896.3,2036.6
XS GIS Cut Line= 2
2179890.16654376372560.6757633032177811.20426195372727.512195198
#Sta/Elev= 30
       0  1976.4  156.171970.543   296.1 1971.86   404.8 1965.21   483.7 1955.31
   562.7 1936.48   641.7  1936.5   687.8 1920.62   727.3 1921.99   737.2 1928.89
   838.7 1925.35   862.3 1921.51  1046.6 1921.47  1067.2 1925.81  1095.9 1927.82
  1131.2 1937.19 1269.141936.461 1429.411935.741  1609.6 1939.06  1642.3 1937.98
  1668.6 1931.69 1720.461931.321 1749.571931.212    1797    1932    1820  1941.1
  1856.3 1964.72  1935.2 2039.28  2014.2 2104.28  2053.7 2124.52  2085.6 2118.84
#Mann= 8 ,-1 , 0
       0      .1       0  156.17      .1       0   838.7     .04       0
  1067.2      .1       0 1269.14      .1       0 1429.41      .1       0
 1720.46    .045       0 1749.57      .1       0
Bank Sta=838.7,1067.2
XS Rating Curve= 0 ,0
Exp/Cntr=0.3,0.1

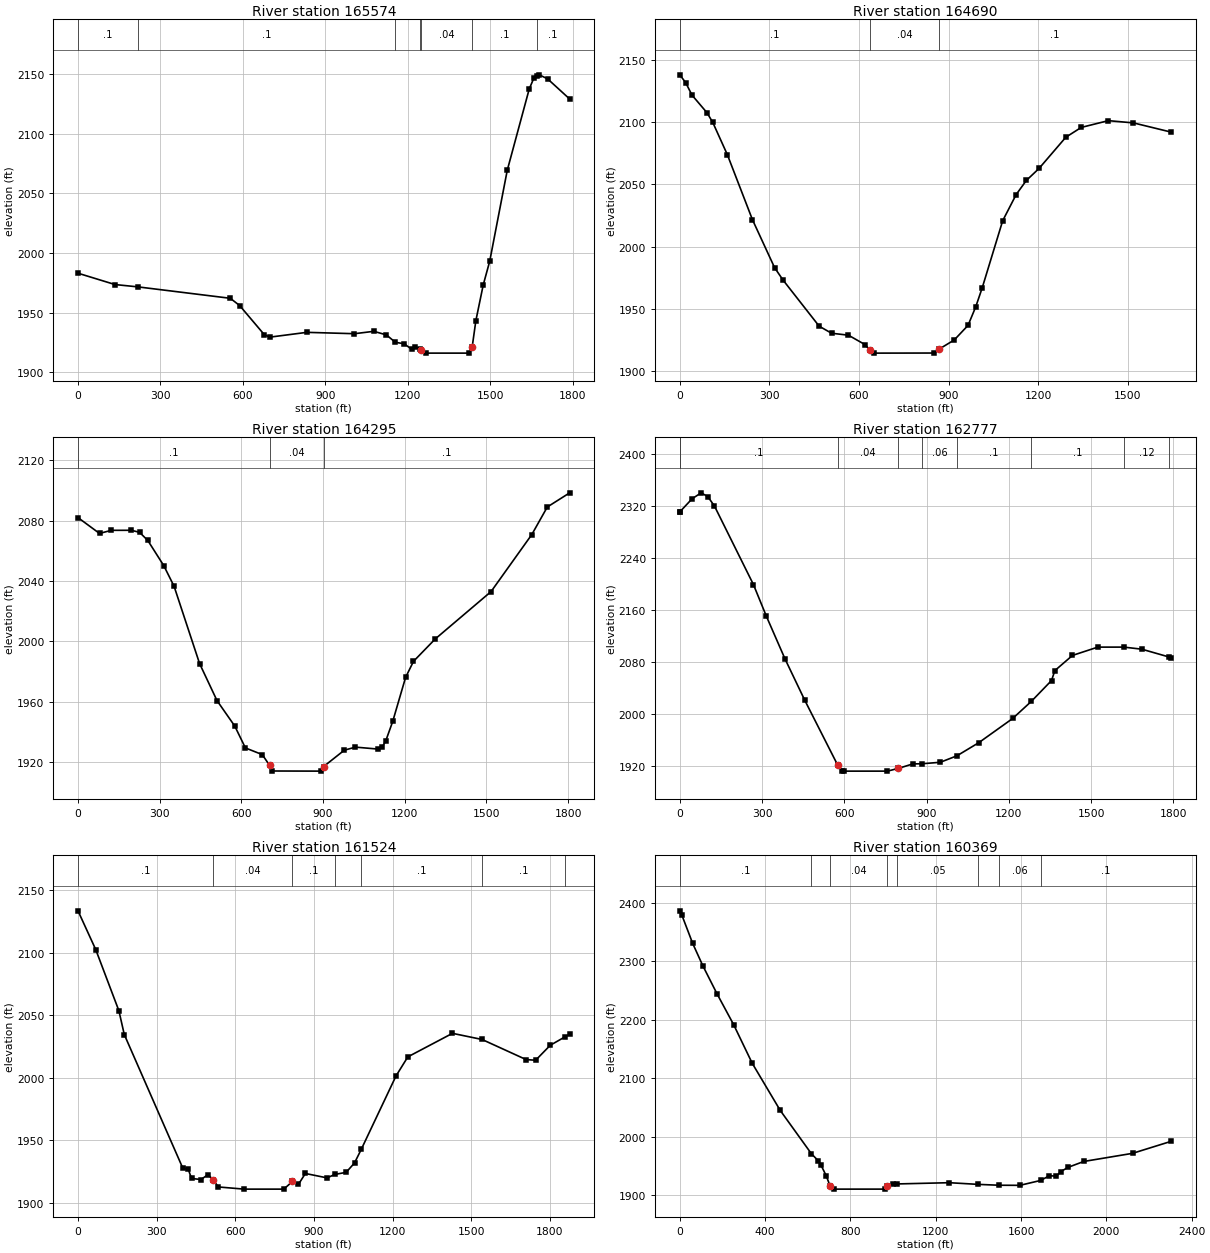
Type RM Length L Ch R = 1 ,165574  ,947.6,883.6,814.5
XS GIS Cut Line= 3
2180023.91180853372340.6432309342179691.70582829372120.610698566
2179415.58657198370757.271870558
#Sta/Elev= 30
       0  1983.1   134.5  1973.6   217.71971.647   554.4 1962.06   588.3 1955.98
   678.2 1931.52   698.3 1929.49   832.9 1933.51  1006.3 1932.37  1076.6 1934.36
  1122.4 1931.37 1154.741925.185    1187 1923.93  1213.8 1919.43  1228.2 1921.38
  1244.9 1919.19  1249.4    1919  1267.4 1916.09  1424.7 1916.08  1434.8 1921.53
  1448.1 1943.43  1474.9 1973.33  1498.4 1993.12  1562.2 2069.35  1642.3 2137.64
    1659 2146.68 1669.442148.497  1679.1 2149.47  1709.2 2146.06  1789.5 2129.17
#Mann= 7 ,-1 , 0
       0      .1       0   217.7      .1       0 1154.74      .1       0
  1244.9      .1       0  1249.4     .04       0  1434.8      .1       0
 1669.44      .1       0
Bank Sta=1249.4,1434.8
XS Rating Curve= 0 ,0
Exp/Cntr=0.3,0.1

Type RM Length L Ch R = 1 ,164690  ,418.5,395.2,368
XS GIS Cut Line= 3
2180918.41604162371429.6471009712179999.45664173370666.004782752
2179559.39157699370566.774425017
#Sta/Elev= 30
       0  2137.8   19.46 2131.62    40.9 2121.52   91.22 2107.33  110.32 2099.65
  159.25  2073.7  243.12 2021.61  317.31 1983.07  345.63  1973.1  466.61 1936.08
  508.04 1930.44  564.51 1928.86  620.18 1921.29   636.7 1916.88  650.04 1914.47
  851.98 1914.55  867.59 1917.61  918.78 1925.04  964.91 1936.74  990.58 1951.56
 1012.63 1967.06 1080.88 2020.71  1126.1 2041.75 1159.98    2053 1202.53 2062.65
 1292.25 2087.71 1343.78 2095.58 1434.59 2101.03 1518.67 2099.22 1645.95 2091.76
#Mann= 3 , 0 , 0
       0      .1       0   636.7     .04       0  867.59      .1       0
Bank Sta=636.7,867.59
XS Rating Curve= 0 ,0
Exp/Cntr=0.3,0.1

Type RM Length L Ch R = 1 ,164295  ,1654.1,1517.8,1364.4
XS GIS Cut Line= 4
2181362.18469322370685.8207409532180860.74053751370781.712889229
2179992.71659306370371.708469165 2179660.1329205 370331.52525836
#Sta/Elev= 30
       0  2082.1      79  2071.6   122.4 2073.66   195.9 2073.69     226 2072.34
   256.3 2066.93   315.2 2050.16   352.9  2036.5   446.4 1985.29   510.5 1960.67
   575.7 1943.79   614.7  1929.3   676.7 1924.87   703.5 1917.73   710.8    1914
   890.7 1913.91   901.7 1916.91   977.9  1927.8  1018.9 1929.83  1102.7 1928.52
  1117.5 1930.04  1129.8 1933.83  1155.7 1946.91  1202.9 1976.07  1231.9 1986.73
  1311.7 2001.58  1516.9 2033.05  1666.3 2070.84  1723.3 2089.14  1805.5 2098.54
#Mann= 3 , 0 , 0
       0      .1       0   703.5     .04       0   901.7      .1       0
Bank Sta=703.5,901.7
XS Rating Curve= 0 ,0
Exp/Cntr=0.3,0.1

Type RM Length L Ch R = 1 ,162777  ,1323.3,1253.1,1181.7
XS GIS Cut Line= 2
2180322.16366615368938.0500754872179286.74690199370402.506935291
#Sta/Elev= 30
       0 2311.28     1.32311.867      45 2331.55      78 2340.64   102.3 2334.72
   126.5 2320.25   268.6 2199.41   316.2 2150.24   383.6 2085.09   455.9 2021.22
   576.5  1920.9   592.5 1912.87   600.5 1912.12   757.3 1912.12   797.5 1916.36
     850 1923.23   882.8 1923.48   950.2 1925.74 1010.921935.712  1090.8 1955.97
  1214.2 1993.17 1282.242019.507    1356 2051.66    1368 2066.86  1432.3 2090.27
  1524.7 2103.06 1620.062103.079  1685.5 2099.85 1783.882087.951  1793.5 2086.76
#Mann= 9 ,-1 , 0
       0      .1       0     1.3      .1       0   576.5     .04       0
   797.5      .1       0   882.8     .06       0 1010.92      .1       0
 1282.24      .1       0 1620.06     .12       0 1783.88      .1       0
Bank Sta=576.5,797.5
XS Rating Curve= 0 ,0
Exp/Cntr=0.3,0.1

Type RM Length L Ch R = 1 ,161524  ,1195.5,1154.8,1115.3
XS GIS Cut Line= 2
2178794.78092565368428.9224953212178663.20862965370299.537312336
#Sta/Elev= 30
       0  2133.6    67.9 2102.48     156 2053.67   176.5  2034.7   400.1 1927.67
   419.8 1927.31     433 1919.63   469.2 1918.77   495.5 1922.69   515.5 1918.63
     535 1912.83   633.6 1911.09   784.9 1911.09   817.8 1917.21   840.8 1914.91
   867.1 1923.61   950.1 1920.07  979.361922.853  1022.5 1924.48  1054.6 1932.03
 1080.271942.874    1213 2001.64  1257.9 2016.83  1428.1 2035.65 1540.922030.746
  1709.1 2014.66  1745.3 2014.14  1801.2 2026.12 1856.112032.691  1875.2 2034.83
#Mann= 7 ,-1 , 0
       0      .1       0   515.5     .04       0   817.8      .1       0
  979.36     .06       0 1080.27      .1       0 1540.92      .1       0
 1856.11      .1       0
Bank Sta=515.5,817.8
XS Rating Curve= 0 ,0
Exp/Cntr=0.3,0.1

Type RM Length L Ch R = 1 ,160369  ,2008.8,1907.4,1754.8
XS GIS Cut Line= 2
2177410.41155037368280.1885954972177919.53913053370528.358696681
#Sta/Elev= 30
       0 2385.88    10.1 2378.17    60.5 2330.13   107.6 2292.27   174.5 2244.06
   252.3 2191.42   339.7 2125.19   470.9 2044.67   616.71970.784   649.2 1958.56
   662.7 1950.64   686.2 1933.14   705.5  1914.7   722.5 1910.13   961.6 1910.15
   970.9 1914.67     999 1918.88  1017.91918.998    1264 1921.12 1398.641918.243
 1496.381916.786  1594.5 1916.61 1691.861924.996  1732.4 1933.02  1765.9 1932.31
  1785.1 1939.82  1819.8 1947.32  1893.8 1957.41  2122.6 1971.31  2305.1 1992.03
#Mann= 8 ,-1 , 0
       0      .1       0   616.7      .1       0   705.5     .04       0
   970.9      .1       0  1017.9     .05       0 1398.64      .1       0
 1496.38     .06       0 1691.86      .1       0
Bank Sta=705.5,970.9
XS Rating Curve= 0 ,0
Exp/Cntr=0.3,0.1

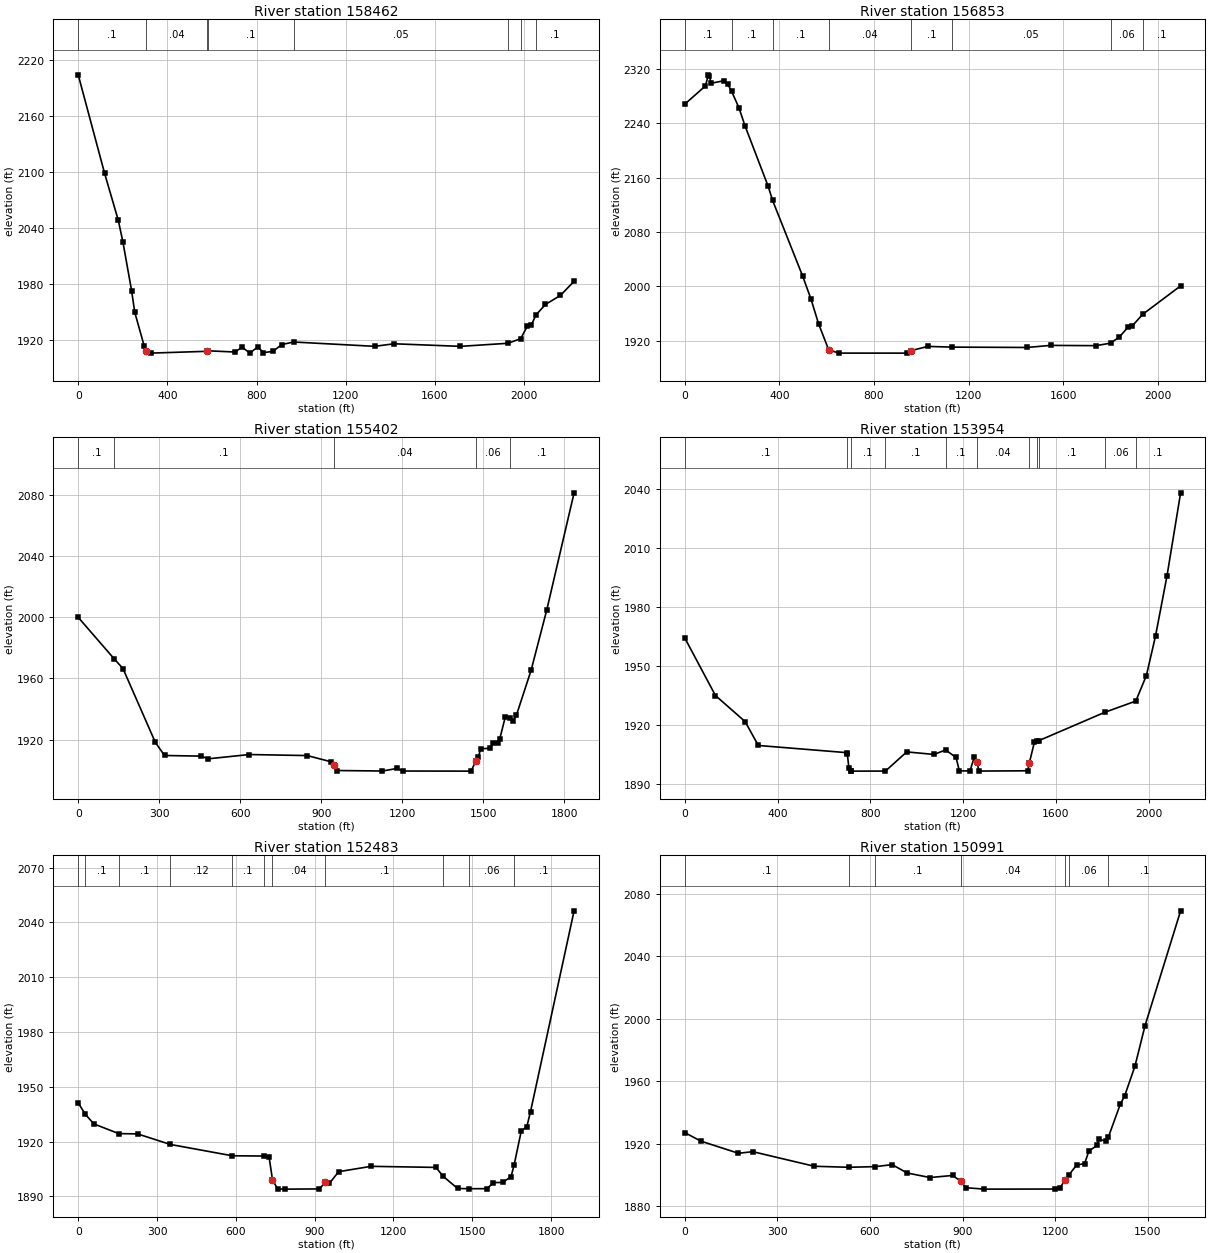
Type RM Length L Ch R = 1 ,158462  ,1695.4,1609,1470.9
XS GIS Cut Line= 2
2175775.54851716369777.3663500772177823.40423901370644.035665808
#Sta/Elev= 30
       0 2203.77   118.1 2098.52   179.8 2047.96   200.1 2025.31   239.3 1972.91
   253.5 1949.67   296.3 1913.24   304.9 1908.55   324.8 1905.91   577.7 1907.87
  582.17 1908.38   702.4 1907.11   734.5  1912.1   770.1 1906.11   805.2 1912.51
   830.4 1906.49   873.1 1907.73   912.6 1915.07  966.021917.819  1329.4 1913.19
  1416.3 1915.91  1714.2 1913.16 1927.411916.457 1984.121921.376  2013.4 1934.48
  2031.2 1935.83 2053.721947.056  2095.4 1958.04  2162.3 1967.64  2223.7 1982.84
#Mann= 8 ,-1 , 0
       0      .1       0   304.9     .04       0   577.7      .1       0
  582.17      .1       0  966.02     .05       0 1927.41      .1       0
 1984.12     .06       0 2053.72      .1       0
Bank Sta=304.9,577.7
XS Rating Curve= 0 ,0
Exp/Cntr=0.3,0.1

Type RM Length L Ch R = 1 ,156853  ,1185.9,1450.9,1539.6
XS GIS Cut Line= 2
2175824.47339789371751.8347508352177760.50082093370948.068853182
#Sta/Elev= 30
       0 2267.73      87  2294.4   100.4 2310.87     104 2309.28   111.5 2298.47
   164.5 2302.13   181.2 2297.64  198.262286.593   229.5 2262.16   254.6 2236.05
   352.6  2147.2   371.12126.621   498.6 2015.14   533.7 1981.45   565.7 1945.28
   608.3 1907.07     651 1902.13   939.9  1902.1   956.5  1905.8  1028.2 1911.95
 1128.461910.953  1446.7  1910.4  1546.2 1913.44    1738 1913.06 1799.961916.727
  1837.5 1925.79    1873 1939.98  1890.7 1941.56 1935.361958.941  2096.2 2000.91
#Mann= 8 ,-1 , 0
       0      .1       0  198.26      .1       0   371.1      .1       0
   608.3     .04       0   956.5      .1       0 1128.46     .05       0
 1799.96     .06       0 1935.36      .1       0
Bank Sta=608.3,956.5
XS Rating Curve= 0 ,0
Exp/Cntr=0.3,0.1

Type RM Length L Ch R = 1 ,155402  ,1259.1,1448.2,1549.7
XS GIS Cut Line= 2
2175951.67522517372336.0476330022177713.59988462372856.616282385
#Sta/Elev= 30
       0 1999.94  134.351972.622   165.9 1966.48   285.8 1918.26   319.8 1909.71
   456.6  1909.3   480.6 1907.53   634.1 1910.34   848.4 1909.66   935.6 1905.66
   946.7 1903.61   959.5  1899.9  1127.2 1899.57  1181.1 1901.25  1202.4 1899.56
  1455.6  1899.5  1472.7 1905.98    1483 1908.85  1490.9 1914.09    1524  1914.4
  1537.6 1917.58  1554.8 1918.16  1561.6 1920.43  1582.2  1934.8 1600.261934.497
  1609.5 1931.92  1623.2 1935.84    1678 1965.43  1736.1 2004.88  1837.2 2081.27
#Mann= 5 ,-1 , 0
       0      .1       0  134.35      .1       0   946.7     .04       0
  1472.7     .06       0 1600.26      .1       0
Bank Sta=946.7,1472.7
XS Rating Curve= 0 ,0
Exp/Cntr=0.3,0.1

Type RM Length L Ch R = 1 ,153954  ,1452.1,1471,1467.2
XS GIS Cut Line= 2
2175908.34462199372478.718693062  2176726.089057 374453.18709382
#Sta/Elev= 30
       0  1964.1   132.4 1934.82   260.2 1921.58     317 1909.44  697.541905.797
   700.5 1905.23   707.6 1897.87   714.7  1896.4  716.25  1896.4     8651896.427
   956.6 1906.17  1074.6 1904.88 1124.231907.177  1169.3 1903.33  1183.5 1896.52
  1229.6 1896.51  1247.4 1903.49  1258.3 1900.85  1268.7 1896.44  1478.2 1896.57
  1485.3 1900.65  1506.6 1910.98  1519.41911.812 1524.94 1911.84 1810.73 1926.32
 1943.951932.001  1989.6    1945  2028.9 1965.06  2078.4 1995.65  2137.1 2037.84
#Mann= 11 ,-1 , 0
       0      .1       0  697.54      .1       0  716.25      .1       0
     865      .1       0 1124.23      .1       0  1258.3     .04       0
  1485.3      .1       0  1519.4      .1       0 1524.94      .1       0
 1810.73     .06       0 1943.95      .1       0
Bank Sta=1258.3,1485.3
XS Rating Curve= 0 ,0
Exp/Cntr=0.3,0.1

Type RM Length L Ch R = 1 ,152483  ,1401.4,1491.4,1565.6
XS GIS Cut Line= 2
2174751.23236353372781.5870023222175446.27630402374536.670025219
#Sta/Elev= 30
       0 1941.25   27.091934.925    59.8 1929.69  154.341924.391   225.8 1924.24
  350.631918.464  586.081912.262  707.411912.115   726.8  1911.4   739.6 1899.09
   759.2 1894.06   787.5    1894   917.3  1894.1   941.2  1897.7   956.3 1897.18
   991.4 1903.55  1114.9 1906.48  1361.9 1905.89 1389.231901.019  1444.2 1894.35
 1489.21 1894.22    1556 1894.25  1580.7 1897.59    1616 1897.65  1647.8 1900.82
 1659.481907.321  1686.6 1925.82  1707.8 1928.23  1721.9 1936.49  1887.7 2046.35
#Mann= 11 ,-1 , 0
       0      .1       0   27.09      .1       0  154.34      .1       0
  350.63     .12       0  586.08      .1       0  707.41      .1       0
   739.6     .04       0   941.2      .1       0 1389.23      .1       0
 1489.21     .06       0 1659.48      .1       0
Bank Sta=739.6,941.2
XS Rating Curve= 0 ,0
Exp/Cntr=0.3,0.1

Type RM Length L Ch R = 1 ,150991  ,1560.6,1540,1509
XS GIS Cut Line= 2
2173830.97865463372898.0748135762173594.12010508374486.191973675
#Sta/Elev= 30
       0 1927.07    51.9 1921.61     174 1913.81   220.4 1914.84   419.5 1905.51
  530.971904.861     6171905.272   671.6 1906.54   720.4  1901.2   794.3 1898.29
   867.3 1899.63   893.8 1895.96   910.4 1891.78   970.1 1890.88    1199 1890.94
  1215.6 1891.75  1231.4 1896.79 1242.941899.696  1268.9 1906.27  1294.9 1907.22
  1308.5 1915.18    1335 1918.86  1341.6 1922.81  1364.8 1921.47 1372.061924.349
  1410.3 1945.19  1424.6 1950.61  1457.7 1969.47  1490.5 1995.48  1605.7 2068.94
#Mann= 7 ,-1 , 0
       0      .1       0  530.97     .12       0     617      .1       0
   893.8     .04       0  1231.4      .1       0 1242.94     .06       0
 1372.06      .1       0
Bank Sta=893.8,1231.4
XS Rating Curve= 0 ,0
Exp/Cntr=0.3,0.1