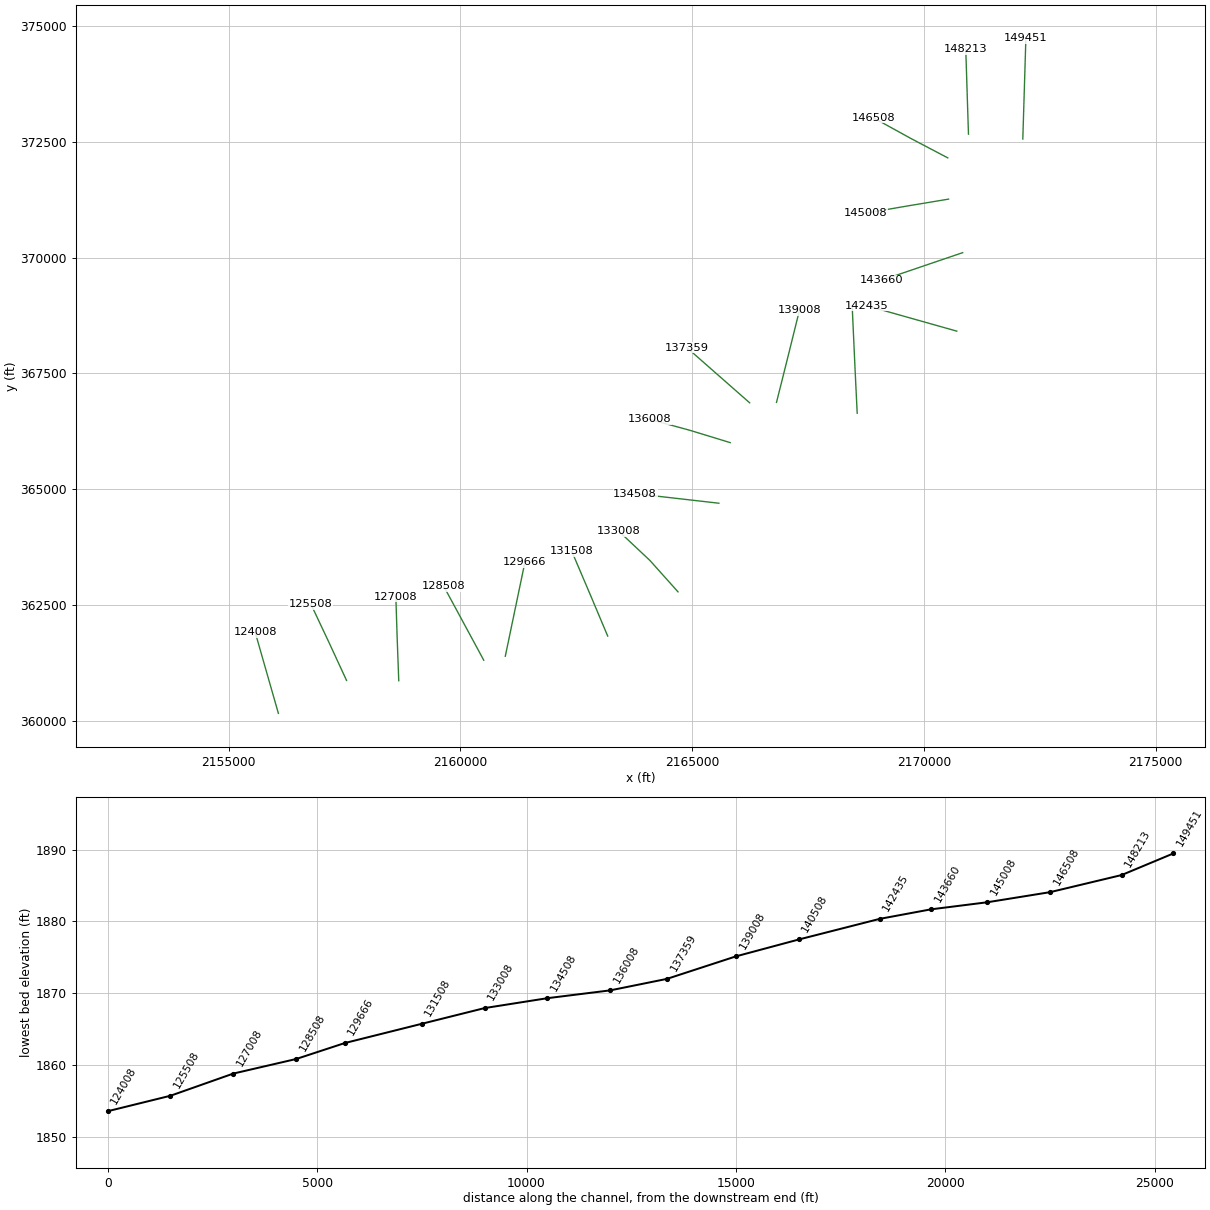
HEC-RAS study GRBRRV5.prj: GRBRRV5

--- GRBRRV5.g01 (geometry) --- (continued)

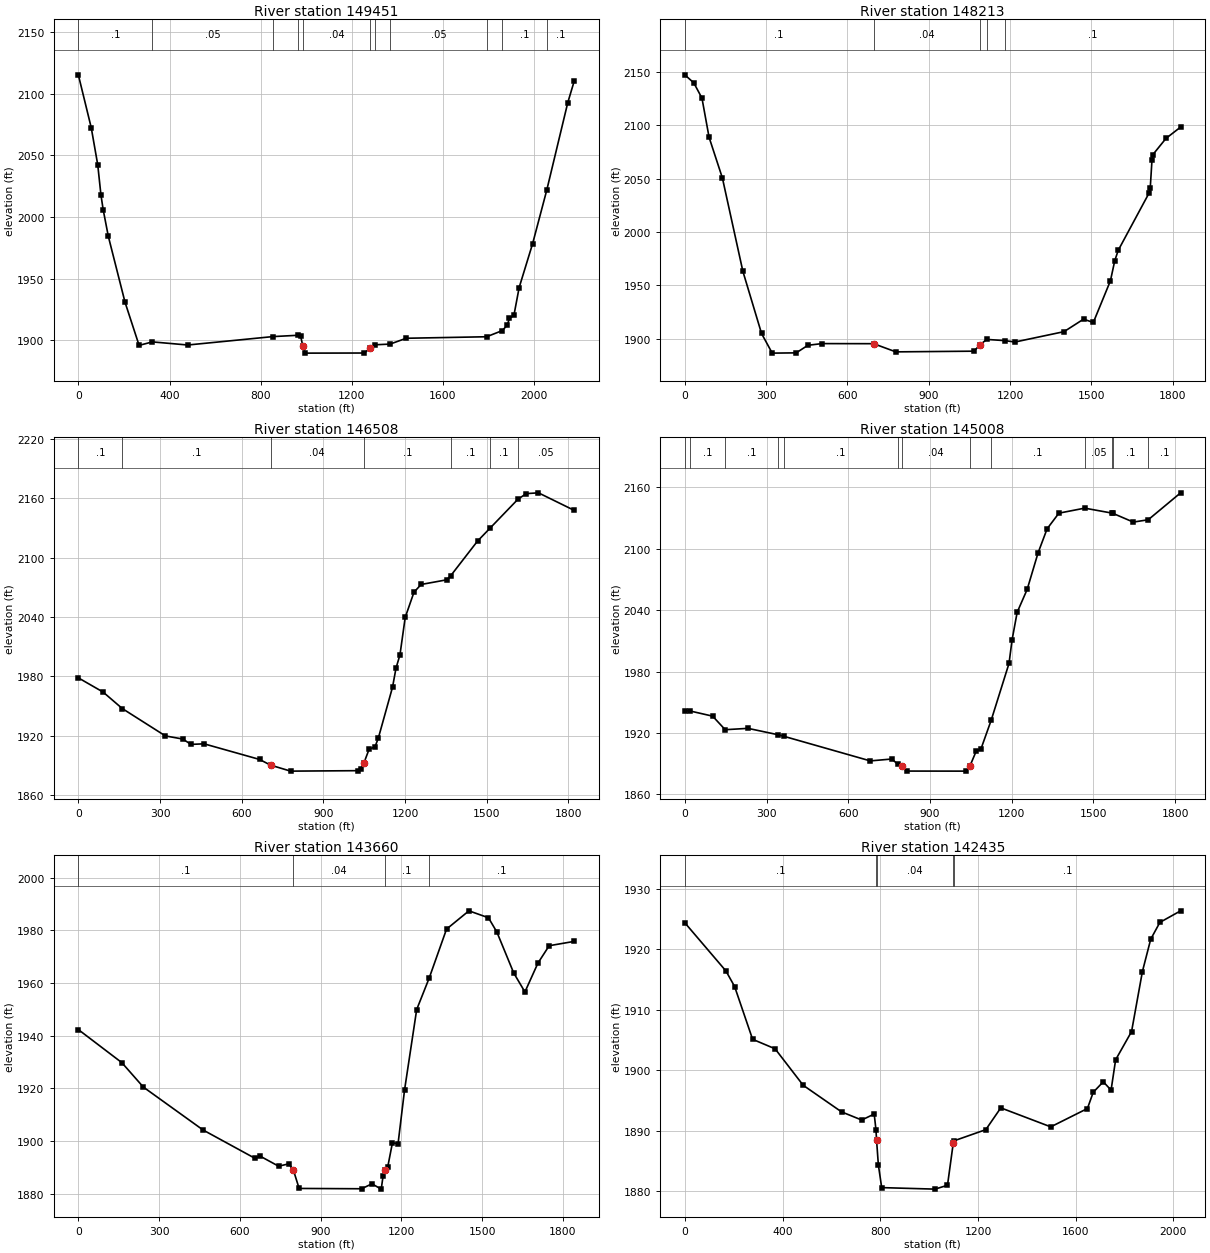
Type RM Length L Ch R = 1 ,149451  ,1239.9,1238.8,1249.6
XS GIS Cut Line= 2
2172134.13953736372564.1430879812172200.14929707374738.582231392
#Sta/Elev= 30
       0 2115.26    56.6  2072.4    85.2 2042.21    99.2 2017.77   109.1 2005.77
   131.6 1984.21   204.8 1930.79   266.6 1895.76  325.011898.584     480 1896.06
  854.031902.889  964.291903.955   975.6 1902.97   985.3 1895.03   995.3 1889.47
  1254.6 1889.56  1280.1 1893.36 1300.021896.237 1367.671896.786  1438.4 1901.53
 1791.381902.755 1860.341907.776  1881.6 1912.16  1891.4 1917.61  1911.1 1920.15
  1934.1 1942.69  1993.2 1978.34 2054.862021.475  2147.4 2092.71  2175.4 2110.03
#Mann= 11 ,-1 , 0
       0      .1       0  325.01     .05       0  854.03      .1       0
  964.29      .1       0   985.3     .04       0  1280.1      .1       0
 1300.02      .1       0 1367.67     .05       0 1791.38     .06       0
 1860.34      .1       0 2054.86      .1       0
Bank Sta=985.3,1280.1
XS Rating Curve= 0 ,0
Exp/Cntr=0.3,0.1

Type RM Length L Ch R = 1 ,148213  ,1442.5,1704.9,1841.8
XS GIS Cut Line= 2
2170961.49557073 372668.982118112170903.25166511  374497.8407548
#Sta/Elev= 30
       0 2147.18    33.1 2139.68    63.3 2125.38    89.6 2088.66   138.8 2050.47
   214.3 1963.13   283.2 1904.85   322.6 1886.45   411.2  1886.7   454.2 1893.79
   506.4 1895.38   696.8 1895.29   778.9 1887.63  1067.7 1888.28  1087.6 1893.89
 1114.211899.284 1179.971898.195  1218.7 1896.87  1399.5 1906.57  1471.5 1918.27
  1507.6 1915.16  1570.8 1954.27  1586.7 1973.01  1599.5 1982.76  1714.4 2036.93
  1717.7 2041.18  1724.2 2067.85  1727.5 2072.46  1775.8 2087.62  1829.8 2098.24
#Mann= 5 ,-1 , 0
       0      .1       0   696.8     .04       0  1087.6      .1       0
 1114.21      .1       0 1179.97      .1       0
Bank Sta=696.8,1087.6
XS Rating Curve= 0 ,0
Exp/Cntr=0.3,0.1

Type RM Length L Ch R = 1 ,146508  ,1383.3,1500,1589.9
XS GIS Cut Line= 3
     2170515.369      372156.676     2169709.065      372581.452
       2168912.5      373020.801
#Sta/Elev= 30
       0 1978.46      91 1964.06  161.471947.381   319.8 1919.69   383.7 1916.54
   413.6 1911.13   461.8  1911.7   665.4 1895.91   706.1 1890.13   779.5 1884.07
  1026.6 1884.53  1037.9    1886  1049.1 1892.48  1067.8 1906.19  1089.4 1908.64
  1101.6 1917.29    1154  1969.1  1166.7  1988.3  1181.2 2001.66  1200.5 2039.62
  1232.7  2065.1  1258.9 2072.94  1352.6 2077.64 1367.662081.809  1466.1 2116.83
 1511.192129.674 1614.092159.063  1644.7 2164.86  1689.8 2165.68    1821 2147.96
#Mann= 7 ,-1 , 0
       0      .1       0  161.47      .1       0   706.1     .04       0
  1049.1      .1       0 1367.66      .1       0 1511.19      .1       0
 1614.09     .05       0
Bank Sta=706.1,1049.1
XS Rating Curve= 0 ,0
Exp/Cntr=0.3,0.1

Type RM Length L Ch R = 1 ,145008  ,1328.4,1347.8,1378
XS GIS Cut Line= 3
     2170532.389      371266.134     2169634.774      371116.531
     2168738.032      370961.643
#Sta/Elev= 30
       0 1941.78   17.821941.553   102.2  1936.4  148.281923.156   231.9 1924.48
  343.351918.178  363.791916.706   680.9 1892.66   760.8 1894.53  781.341889.281
   797.3 1887.33     814 1882.72  1033.1 1882.66  1046.9 1887.83  1070.2 1902.55
  1086.9 1904.17 1125.131932.798  1190.1    1988  1201.4 2011.14    1220 2037.94
  1256.7 2060.31  1296.6 2095.94  1329.9 2119.57  1373.2 2134.86 1467.922139.762
 1568.032134.922  1572.4 2134.56  1646.2 2126.14 1701.032128.398    1820 2154.74
#Mann= 13 ,-1 , 0
       0      .1       0   17.82      .1       0  148.28      .1       0
  343.35      .1       0  363.79      .1       0  781.34      .1       0
   797.3     .04       0  1046.9      .1       0 1125.13      .1       0
 1467.92     .05       0 1568.03      .1       0  1572.4      .1       0
 1701.03      .1       0
Bank Sta=797.3,1046.9
XS Rating Curve= 0 ,0
Exp/Cntr=0.3,0.1

Type RM Length L Ch R = 1 ,143660  ,1289.3,1224.6,1076.1
XS GIS Cut Line= 2
2170837.24190539 370110.133197562169093.80766362369516.045360164
#Sta/Elev= 30
       0 1942.27   161.6 1929.71   241.5 1920.43   463.2 1904.14   657.3 1893.31
   674.6 1894.24     744 1890.38   782.1 1891.28   798.4 1889.06   820.2 1881.93
  1052.4 1881.81  1090.6 1883.69  1125.2 1881.67  1132.2 1886.76  1140.2 1888.82
  1149.5 1890.17  1166.8 1899.26  1187.7 1898.92  1211.9 1919.36  1256.9 1949.87
 1303.341961.827  1367.8 1980.42    1451 1987.37  1523.5 1984.74  1554.8 1979.31
  1617.4 1963.76    1659 1956.56  1707.3 1967.51  1749.1 1974.12  1841.9 1975.76
#Mann= 4 ,-1 , 0
       0      .1       0   798.4     .04       0  1140.2      .1       0
 1303.34      .1       0
Bank Sta=798.4,1140.2
XS Rating Curve= 0 ,0
Exp/Cntr=0.3,0.1

Type RM Length L Ch R = 1 ,142435  ,2089.5,1927.6,1730.4
XS GIS Cut Line= 2
2170708.52675689 368415.041397462168755.41445486368966.417037396
#Sta/Elev= 30
       0 1924.36  168.42 1916.39   203.9 1913.82  277.51  1905.1  369.56 1903.53
  484.62  1897.5  641.48 1893.11   724.1 1891.76  775.24 1892.75  782.38 1890.17
     785 1888.39  792.28 1884.34  805.92 1880.59  1024.1 1880.34 1075.23 1880.98
  1099.1 1888.03 1102.51 1888.33 1232.05 1890.17 1293.42 1893.77 1497.96 1890.63
 1647.96 1893.66 1671.82 1896.35 1712.87 1898.08 1744.77  1896.7 1763.38 1901.71
 1828.64 1906.38 1872.96 1916.29 1907.05 1921.64 1944.55 1924.42 2029.45 1926.33
#Mann= 5 ,-1 , 0
       0      .1       0  782.38      .1       0     785     .04       0
  1099.1      .1       0 1102.51      .1       0
Bank Sta=785,1099.1
XS Rating Curve= 0 ,0
Exp/Cntr=0.3,0.1

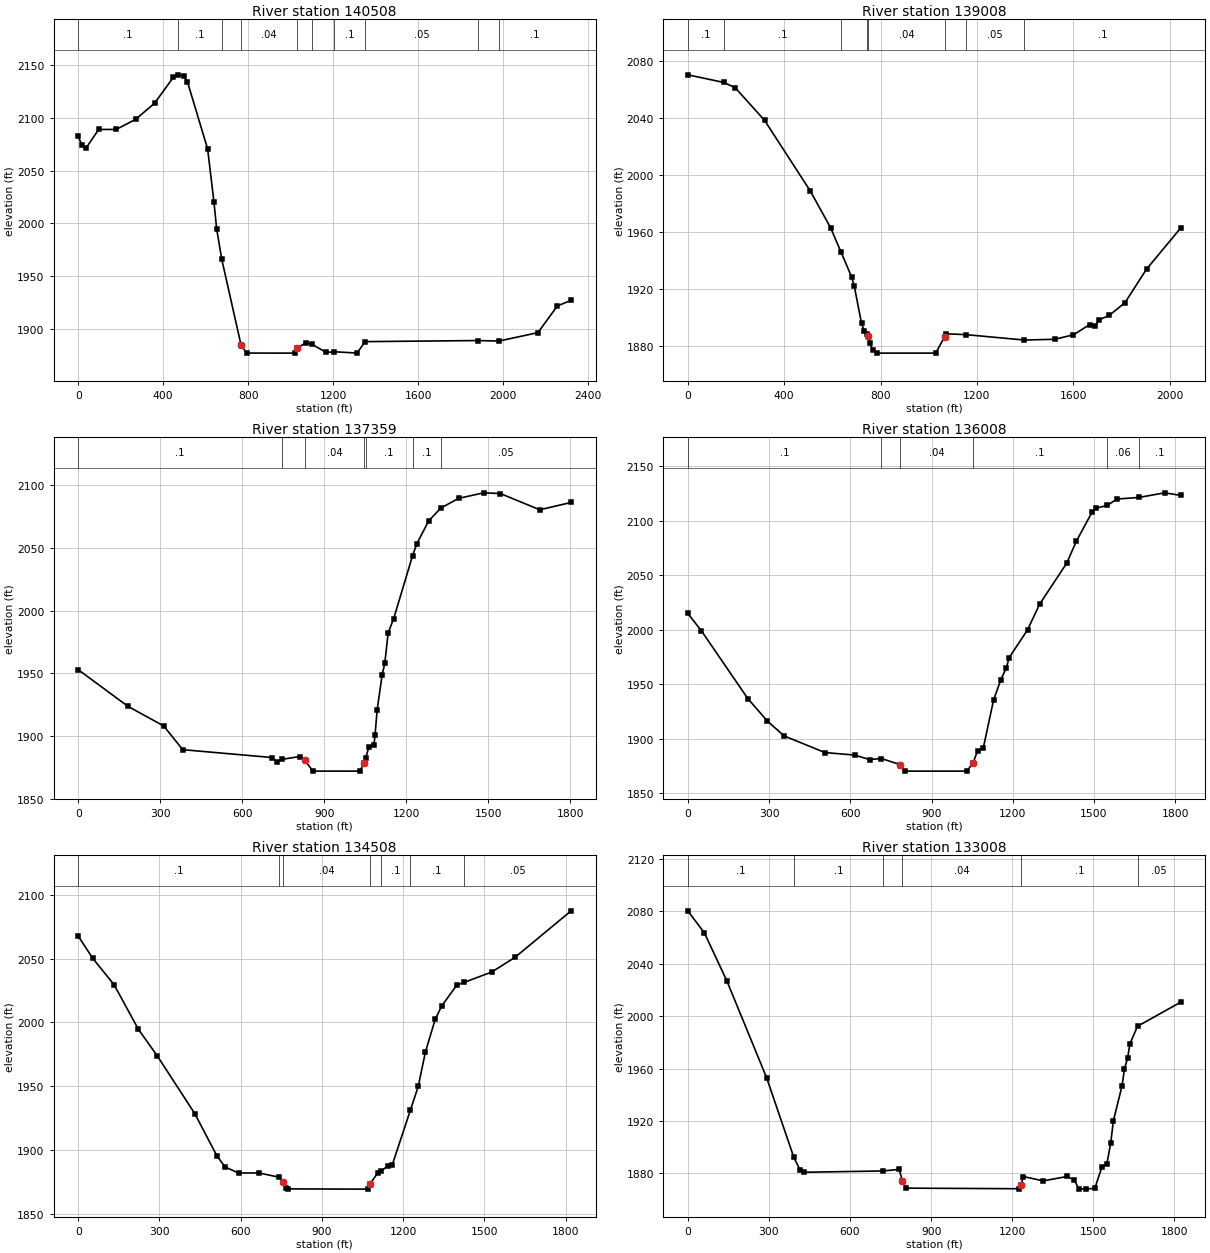
Type RM Length L Ch R = 1 ,140508  ,1542.9,1500,1462
XS GIS Cut Line= 3
     2168560.491      366641.879      2168516.37      367550.808
2168452.43542331368957.933071172
#Sta/Elev= 30
       0 2082.43    17.6 2073.97    37.3 2071.39    96.4 2088.86   178.6 2088.86
   270.5 2098.44   359.2 2113.67   447.6 2138.11  470.632140.494   497.1 2139.36
   513.8 2133.94   608.8 2070.49   638.4 2020.63   651.3 1994.91  675.071966.371
   766.5 1884.71   792.7 1877.53  1019.4 1877.47  1029.2 1882.23  1071.5 1887.32
 1098.391885.928  1167.2 1878.07 1203.44  1878.8  1311.7 1877.52 1349.561888.329
 1878.811889.356  1978.3 1888.87  2162.3 1896.82  2254.2 1922.11  2318.6 1927.36
#Mann= 10 ,-1 , 0
       0      .1       0  470.63      .1       0  675.07      .1       0
   766.5     .04       0  1029.2      .1       0 1098.39      .1       0
 1203.44      .1       0 1349.56     .05       0 1878.81     .07       0
  1978.3      .1       0
Bank Sta=766.5,1029.2
XS Rating Curve= 0 ,0
Exp/Cntr=0.3,0.1

Type RM Length L Ch R = 1 ,139008  ,1498.6,1648.4,1779.6
XS GIS Cut Line= 3
     2166819.098      366875.483     2167040.425      367758.157
2167313.52436056368860.864532369
#Sta/Elev= 30
       0 2070.59  149.552065.233   196.7 2061.53   318.4 2038.63   507.8 1989.15
   592.4 1963.22  635.521946.205   679.4 1928.82   690.5 1922.49   720.9 1896.08
   731.5 1890.88  742.671888.502     748 1887.24   755.1 1881.97   768.3 1877.09
   785.2 1875.12  1028.9 1875.14  1065.8 1886.59  1072.6 1888.71 1155.831888.084
 1396.121884.317  1522.1 1884.84  1599.9 1887.94  1667.5  1895.1  1691.1 1894.36
    1708 1898.61  1748.6 1901.56  1814.1 1910.49  1904.1 1934.15    2046 1963.06
#Mann= 8 ,-1 , 0
       0      .1       0  149.55      .1       0  635.52      .1       0
  742.67      .1       0     748     .04       0  1065.8      .1       0
 1155.83     .05       0 1396.12      .1       0
Bank Sta=748,1065.8
XS Rating Curve= 0 ,0
Exp/Cntr=0.3,0.1

Type RM Length L Ch R = 1 ,137359  ,1301.9,1351.6,1406.3
XS GIS Cut Line= 2
2166240.85420015366866.5063641892164886.14409889368057.270657009
#Sta/Elev= 30
       0 1952.94     182 1923.67     313 1908.01   382.5  1889.1   710.3 1882.81
   726.6 1879.39  745.071881.347     811 1883.65   829.3 1880.54     859    1872
  1029.4 1871.98  1047.4 1878.49 1051.481882.313  1063.6 1890.96  1082.2 1893.15
  1086.1 1900.42  1093.9 1920.79  1112.4 1949.06  1121.8 1957.89  1134.2 1982.28
  1154.3 1993.56 1223.542043.881    1239 2053.34  1282.7 2071.71    1327 2081.87
  1391.9  2089.6  1483.6 2094.02  1544.9 2093.44  1688.9  2080.5  1803.7 2086.35
#Mann= 7 ,-1 , 0
       0      .1       0  745.07      .1       0   829.3     .04       0
  1047.4      .1       0 1051.48      .1       0 1223.54      .1       0
    1327     .05       0
Bank Sta=829.3,1047.4
XS Rating Curve= 0 ,0
Exp/Cntr=0.3,0.1

Type RM Length L Ch R = 1 ,136008  ,1475,1500,1523.3
XS GIS Cut Line= 3
       2165820.6      366007.034     2164949.937      366273.484
     2164072.091      366512.897
#Sta/Elev= 30
       0 2015.02      50 1999.17   221.5 1936.95   293.6 1916.38   355.3 1902.72
   506.3 1887.43   616.1  1885.1     671    1881   714.71881.962   783.9 1876.34
   801.4 1870.38  1030.3 1870.38  1053.4  1877.9  1070.3 1889.27  1091.4 1891.93
  1129.1 1935.64  1155.8 1954.21  1176.4 1965.31  1186.6 1974.52  1254.6 2000.01
  1298.8 2023.45  1399.4 2061.27  1434.8 2081.35  1492.5 2107.86  1506.3 2111.57
 1549.252114.225  1584.5 2120.03  1665.92121.528  1761.3 2125.74  1820.4 2123.37
#Mann= 6 ,-1 , 0
       0      .1       0   714.7      .1       0   783.9     .04       0
  1053.4      .1       0 1549.25     .06       0  1665.9      .1       0
Bank Sta=783.9,1053.4
XS Rating Curve= 0 ,0
Exp/Cntr=0.3,0.1

Type RM Length L Ch R = 1 ,134508  ,1592.3,1500,1344.7
XS GIS Cut Line= 3
     2165576.724      364698.147     2164672.621      364801.583
     2163768.519      364905.019
#Sta/Elev= 30
       0 2067.79    53.6 2050.34   132.8 2029.52   222.3 1994.61   291.4 1973.99
   430.4 1928.54   512.6 1895.21   542.3 1886.69   591.9 1881.92   667.8 1881.97
  742.331878.629     757 1874.72   766.9  1870.3   773.5 1869.47  1069.8 1869.29
  1077.3 1873.31    1107 1882.32  1119.8 1883.47  1143.3 1887.72  1159.8 1888.44
 1226.211931.024  1255.6 1949.88    1282 1976.86  1318.3 2002.49  1342.4 2013.01
  1397.6 2029.18 1425.082031.439  1526.4 2039.53  1612.5 2051.02    1820 2087.56
#Mann= 7 ,-1 , 0
       0      .1       0  742.33      .1       0     757     .04       0
  1077.3      .1       0  1119.8      .1       0 1226.21      .1       0
 1425.08     .05       0
Bank Sta=757,1077.3
XS Rating Curve= 0 ,0
Exp/Cntr=0.3,0.1

Type RM Length L Ch R = 1 ,133008  ,1539.2,1500,1407.2
XS GIS Cut Line= 3
     2164694.275      362784.095     2164088.093      363461.841
     2163422.718      364088.564
#Sta/Elev= 30
       0 2080.44    61.5 2063.47     144 2027.11   291.5 1952.95   392.21892.086
   414.6 1882.75   430.9  1880.8  721.611881.773   781.8 1882.98   793.2 1874.41
   807.3 1868.66  1223.3 1868.22  1232.2 1871.42  1241.4 1877.52  1314.2 1874.21
  1402.8 1877.56  1429.8 1874.87  1445.7 1868.24  1472.1 1867.91  1505.6  1868.6
  1531.6 1884.89  1550.1 1887.42  1564.1 1902.88    1574 1920.07  1606.1 1946.87
  1615.1 1959.86  1626.7 1967.86  1634.8 1978.72 1663.431992.306  1823.3 2010.71
#Mann= 6 ,-1 , 0
       0      .1       0   392.2      .1       0  721.61      .1       0
   793.2     .04       0  1232.2      .1       0 1663.43     .05       0
Bank Sta=793.2,1232.2
XS Rating Curve= 0 ,0
Exp/Cntr=0.3,0.1

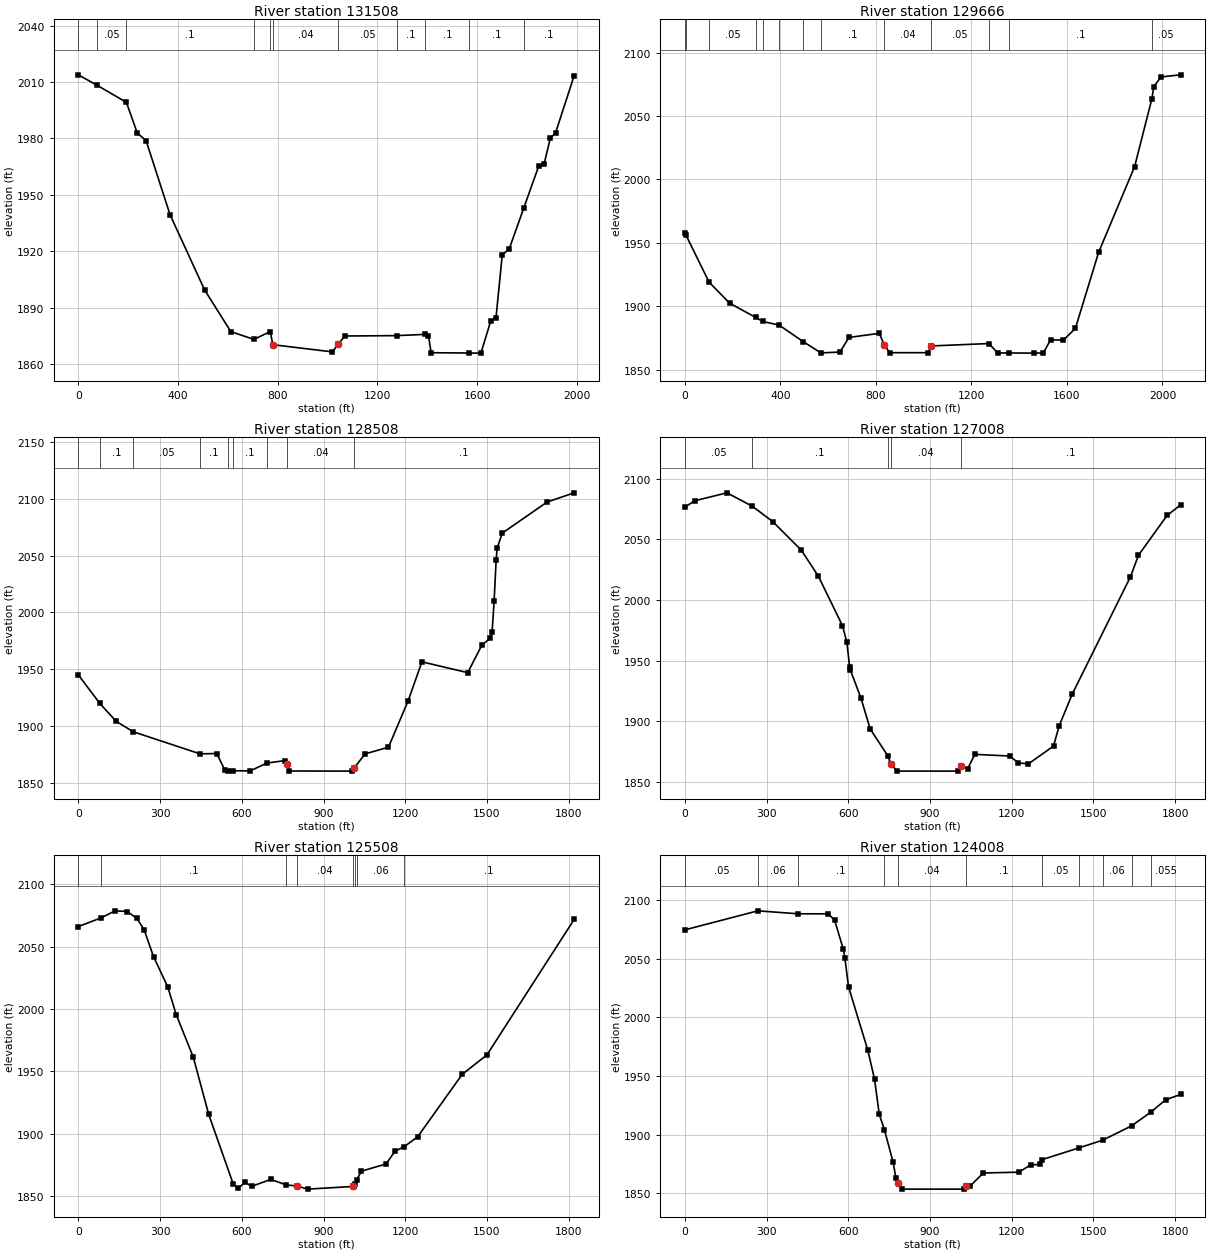
Type RM Length L Ch R = 1 ,131508  ,1902.5,1841.7,1776
XS GIS Cut Line= 3
     2163177.138      361828.809     2162824.329      362667.605
2162401.92127606363660.404445052
#Sta/Elev= 30
       0 2013.89   72.912008.496  192.871999.249   236.2 1982.95   271.8 1978.85
   367.9 1939.41   506.7 1899.32   611.8 1877.16  703.881873.043  770.031877.154
   780.2  1870.2  1019.5 1866.38  1040.9 1870.32  1069.4 1874.84 1277.68 1875.04
 1392.551875.716  1404.5 1874.94  1415.2 1865.94    15691865.771  1614.9 1865.72
  1654.1 1882.78  1675.4 1884.59  1700.5 1918.14  1727.9 1920.99  1786.41942.839
  1846.6 1965.27    1868 1966.21    1893 1979.99  1914.4 1983.05  1988.9 2013.43
#Mann= 11 ,-1 , 0
       0      .1       0   72.91     .05       0  192.87      .1       0
  703.88      .1       0  770.03      .1       0   780.2     .04       0
  1040.9     .05       0 1277.68      .1       0 1392.55      .1       0
    1569      .1       0  1786.4      .1       0
Bank Sta=780.2,1040.9
XS Rating Curve= 0 ,0
Exp/Cntr=0.3,0.1

Type RM Length L Ch R = 1 ,129666  ,1065.9,1158.3,1218.8
XS GIS Cut Line= 2
2160967.44498031361393.7478262862161391.18828465363426.146267479
#Sta/Elev= 30
       0 1957.96    3.88 1956.51  101.531919.056   187.8 1902.41  296.811891.216
  325.491888.041   395.21885.099  495.431872.153  569.951863.191   650.1  1863.9
     687 1875.38   814.4 1878.65   834.4 1869.81   857.9 1863.38  1018.8 1863.38
  1032.2 1868.69 1273.221870.583  1310.3 1863.18 1357.441863.133  1461.1 1863.03
  1501.4 1863.17  1531.5 1873.52  1585.1 1873.27  1635.4 1882.53    1733 1942.68
  1883.4 2010.12 1955.712063.659  1963.8  2073.3    1994 2080.89  2076.1 2082.55
#Mann= 13 ,-1 , 0
       0      .1       0    3.88      .1       0  101.53     .05       0
  296.81      .1       0  325.49     .05       0   395.2      .1       0
  495.43      .1       0  569.95      .1       0   834.4     .04       0
  1032.2     .05       0 1273.22      .1       0 1357.44      .1       0
 1955.71     .05       0
Bank Sta=834.4,1032.2
XS Rating Curve= 0 ,0
Exp/Cntr=0.3,0.1

Type RM Length L Ch R = 1 ,128508  ,1566.2,1500,1450.8
XS GIS Cut Line= 3
     2160502.859      361307.587     2160070.139      362108.121
      2159637.42      362908.654
#Sta/Elev= 30
       0 1945.22   79.151920.147   138.9 1904.48  201.651895.335  446.66 1875.98
   508.1 1876.22   537.9 1861.78  549.421861.149  569.16 1861.12   631.2 1861.03
  691.661867.863     758 1870.05   764.9 1866.75   772.9 1860.94  1004.1 1860.81
  1011.8 1863.38  1052.6 1875.94  1138.4 1881.81  1210.3 1922.32  1261.2  1956.7
  1429.3 1947.21  1481.4 1971.47  1511.3 1977.23  1518.8 1982.93  1526.3 2010.45
  1533.7 2046.28  1537.4 2056.53  1556.1 2069.65  1721.1 2096.97    1820 2104.99
#Mann= 9 ,-1 , 0
       0      .1       0   79.15      .1       0  201.65     .05       0
  446.66      .1       0  549.42      .1       0  569.16      .1       0
  691.66      .1       0   764.9     .04       0  1011.8      .1       0
Bank Sta=764.9,1011.8
XS Rating Curve= 0 ,0
Exp/Cntr=0.3,0.1

Type RM Length L Ch R = 1 ,127008  ,1455.6,1500,1538
XS GIS Cut Line= 3
      2158668.63      360864.615     2158634.867      361773.986
     2158605.449      362683.523
#Sta/Elev= 30
       0 2076.48      37 2081.83   154.8 2088.34   247.72077.288   322.6 2064.63
   427.7 2041.06     490 2019.67   578.7 1978.79   595.1 1964.89   604.9 1945.06
   608.2  1941.9   646.6 1919.03   680.5 1893.61  745.331871.315     756 1864.79
   778.9 1858.82  1002.2 1858.78  1015.3 1862.82  1038.3 1860.73  1064.5 1872.59
  1192.6 1871.24  1224.6 1865.53  1261.5 1864.82  1353.4 1879.41  1373.8 1895.96
  1422.3 1922.39  1635.7 2018.98  1665.3 2036.88  1770.3 2069.67    1820  2078.4
#Mann= 5 ,-1 , 0
       0     .05       0   247.7      .1       0  745.33      .1       0
     756     .04       0  1015.3      .1       0
Bank Sta=756,1015.3
XS Rating Curve= 0 ,0
Exp/Cntr=0.3,0.1

Type RM Length L Ch R = 1 ,125508  ,1519.4,1500,1478.1
XS GIS Cut Line= 3
     2157542.134      360870.746     2157160.572      361696.925
     2156772.611      362520.075
#Sta/Elev= 30
       0 2066.03   82.45 2072.88   135.1 2078.62   179.7 2078.07   214.6 2072.59
   241.5  2063.5   276.1 2041.87     328 2017.84   359.2  1995.5   421.9 1961.42
   478.4 1915.66   568.8 1859.61   586.9 1856.29   612.3 1861.27     636 1857.85
   706.4 1863.52  762.571859.076   802.6 1858.18   842.2 1855.69  1009.9 1857.84
 1015.311860.057 1022.521863.373    1039 1870.04  1129.7 1875.87  1162.4 1886.12
 1196.171889.673  1245.8 1897.68    1409 1947.62  1499.7 1963.17    1820 2071.74
#Mann= 8 ,-1 , 0
       0     .05       0   82.45      .1       0  762.57      .1       0
   802.6     .04       0  1009.9      .1       0 1015.31      .1       0
 1022.52     .06       0 1196.17      .1       0
Bank Sta=802.6,1009.9
XS Rating Curve= 0 ,0
Exp/Cntr=0.3,0.1

Type RM Length L Ch R = 1 ,124008  ,1521.5,1500,1476
XS GIS Cut Line= 3
     2156071.258      360159.549     2155821.265      361034.536
     2155571.272      361909.524
#Sta/Elev= 30
       0 2074.48  268.222090.705   414.32088.194     526 2088.13   549.9 2082.83
   581.5 2058.23   587.4 2050.92   601.1 2025.79   671.8  1971.9   696.6 1947.09
   713.7 1917.37   732.81904.101   764.9 1876.26   775.1 1862.69   781.9 1858.87
     799 1853.53  1024.2 1853.53    1031 1856.11  1048.1 1856.39  1095.8 1867.27
  1225.5 1867.98  1269.9 1874.16    1304  1874.6 1312.65 1878.75 1445.391888.577
 1533.351895.193 1640.771907.541 1712.641919.517  1764.6  1929.6    1820 1934.24
#Mann= 11 ,-1 , 0
       0     .05       0  268.22     .06       0   414.3      .1       0
   732.8      .1       0   781.9     .04       0    1031      .1       0
 1312.65     .05       0 1445.39    .055       0 1533.35     .06       0
 1640.77      .1       0 1712.64    .055       0
Bank Sta=781.9,1031
XS Rating Curve= 0 ,0
Exp/Cntr=0.3,0.1