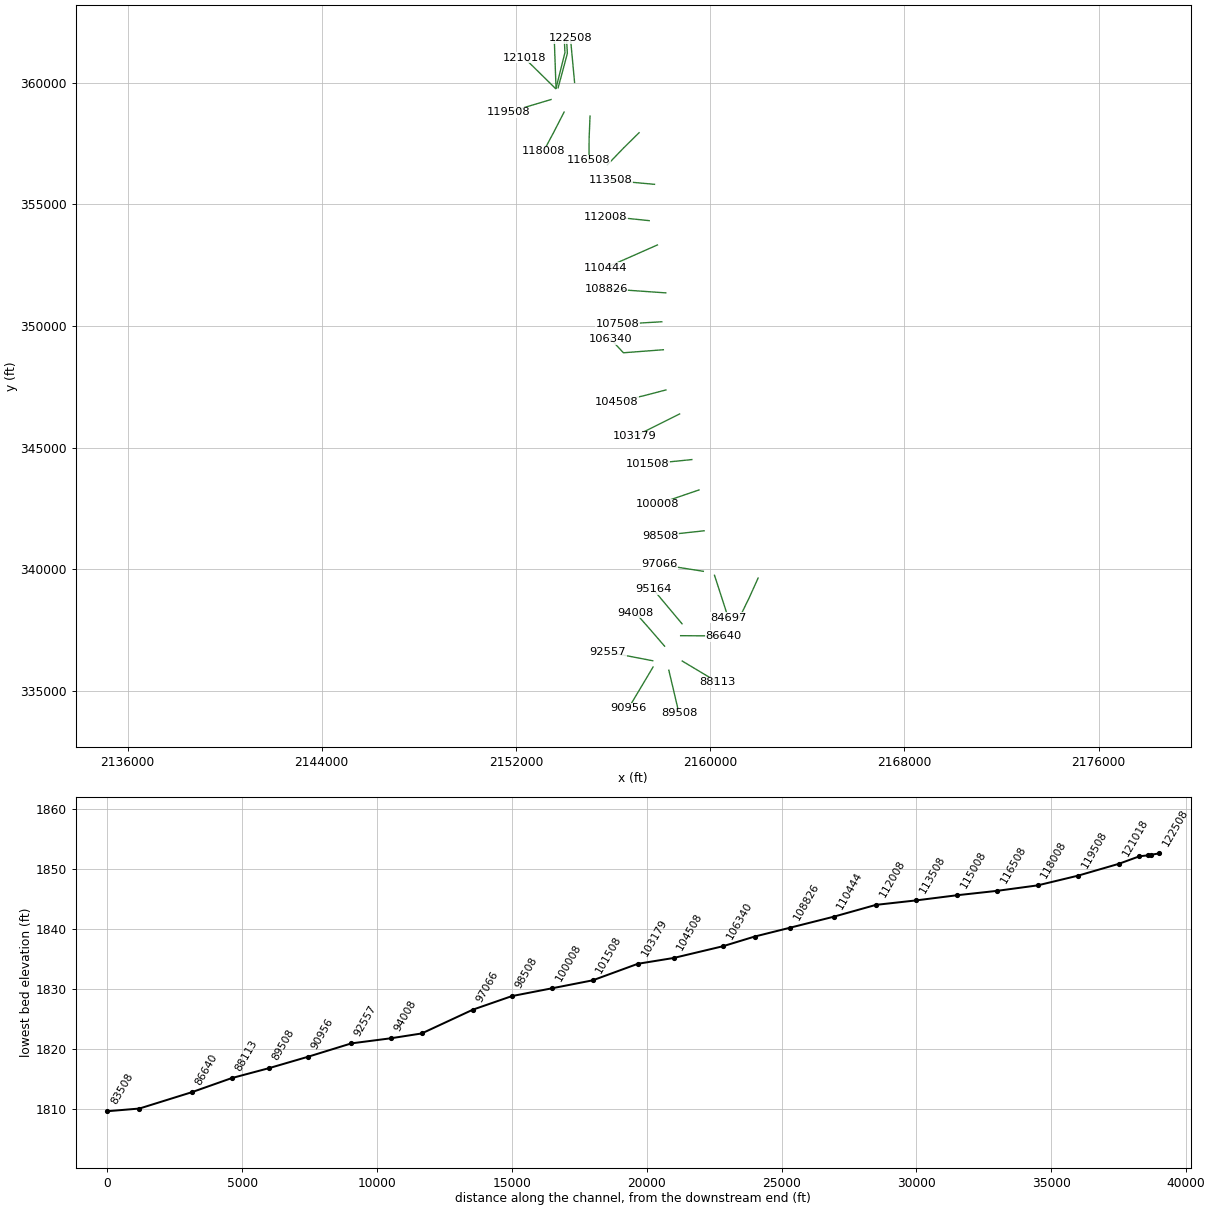
HEC-RAS study GRBRRV5.prj: GRBRRV5

--- GRBRRV5.g01 (geometry) --- (continued)

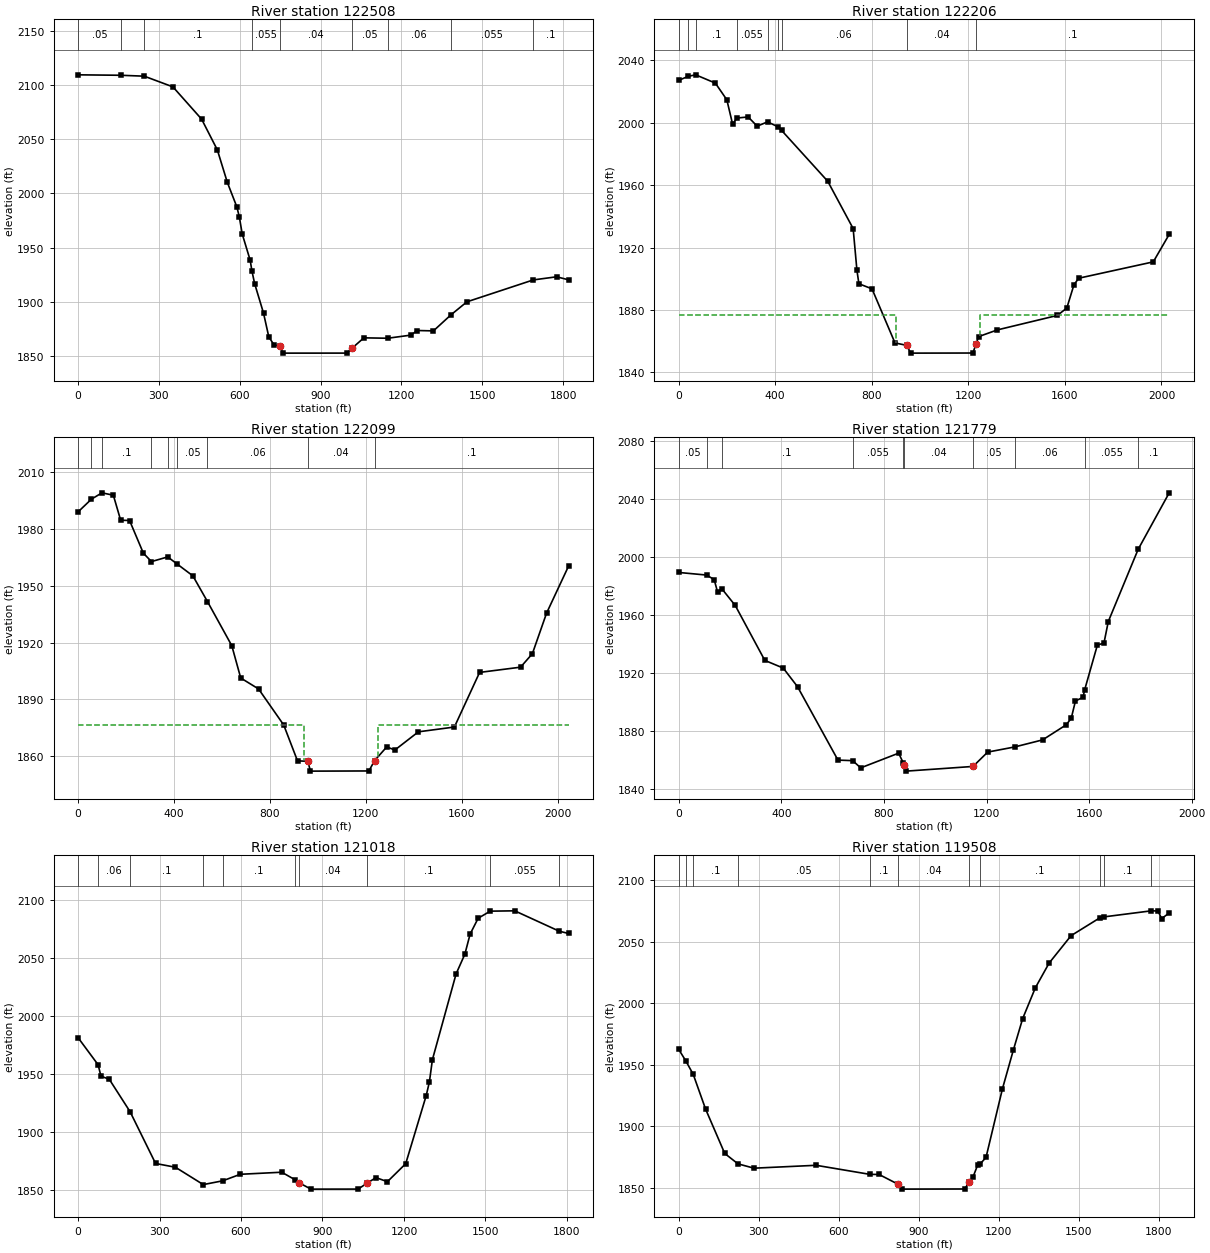
Type RM Length L Ch R = 1 ,122508  ,364.5,301.5,264.5
XS GIS Cut Line= 3
     2154416.905      360009.773     2154332.227      360915.825
     2154247.548      361821.876
#Sta/Elev= 30
       0 2109.61   158.3  2109.2   245.7 2108.36     352 2098.47   458.4 2068.67
   516.7  2040.3   553.8 2010.28   589.1 1987.64   598.3 1978.46     609 1962.67
   638.6 1938.34   645.2 1928.29   655.1 1916.79   688.1 1889.51   707.8 1867.43
   727.6    1860   747.4 1859.08   760.6 1852.54   997.8 1852.56  1017.6  1857.3
  1060.4 1866.66    1149 1866.29  1235.1 1869.18  1258.2 1873.44  1318.5 1873.08
  1383.3 1887.84  1442.7 1899.92  1689.1 1920.17  1775.5 1923.04    1820 1920.27
#Mann= 9 ,-1 , 0
       0     .05       0   158.3      .1       0   245.7      .1       0
   645.2    .055       0   747.4     .04       0  1017.6     .05       0
    1149     .06       0  1383.3    .055       0  1689.1      .1       0
Bank Sta=747.4,1017.6
XS Rating Curve= 0 ,0
Exp/Cntr=0.5,0.3

Type RM Length L Ch R = 1 ,122206  ,101.2,107.4,107.8
XS GIS Cut Line= 3
2153740.20587099359790.3434389892154119.62228969361198.606833556
2154087.03437643361771.223023743
#Sta/Elev= 30
       0 2027.22   39.75 2029.83   70.45 2030.77  151.88 2025.46  199.45 2014.76
  223.23 1999.19  241.56 2003.07  287.79 2003.75  325.17 1997.84  368.11 2000.62
  410.11 1997.52  426.26 1995.14  617.38 1962.54  722.71 1932.19   738.4  1905.4
   746.5 1896.81  800.86 1893.52     896 1858.86  945.53 1857.26  960.56 1852.31
 1218.79 1852.38 1232.38 1858.44 1242.58  1862.9 1320.26 1867.21 1568.43 1876.47
 1607.86 1881.22 1637.45 1896.16 1657.16 1900.34 1966.05 1910.83 2032.02 1928.46
#Mann= 9 ,-1 , 0
       0     .05       0   39.75      .1       0   70.45      .1       0
  241.56    .055       0  368.11    .025       0  410.11     .05       0
  426.26     .06       0  945.53     .04       0 1232.38      .1       0
#XS Ineff= 2 , 0
          900.59  1876.6 1247.25          1876.6
Permanent Ineff=
       F       F
Bank Sta=945.53,1232.38
XS Rating Curve= 0 ,0
Exp/Cntr=0.5,0.3

Type RM Length L Ch R = 1 ,122099  ,270.9,319.7,347.7
XS GIS Cut Line= 3
2153654.10313154359777.908471268 2154019.5533017361232.726027638
 2153993.9485127361777.409720743
#Sta/Elev= 30
       0 1988.87   55.78  1995.6   99.75 1998.93  147.11 1997.67  177.56 1984.49
  214.77 1984.34  272.27 1967.11   306.1 1962.68  373.86 1965.15  414.35 1961.27
  478.62 1955.17  539.51 1941.61  640.99 1918.36  678.21 1901.32  752.63 1895.54
  857.49 1876.55     915 1857.63  957.84 1857.41  969.12 1852.22 1212.68 1852.31
 1236.36 1857.75  1287.1    1865 1320.93 1863.34 1419.03 1872.94 1569.18 1875.47
 1674.29 1904.26 1845.08 1907.02 1894.34 1914.13 1953.47 1935.49  2045.3 1960.32
#Mann= 9 ,-1 , 0
       0     .05       0   55.78      .1       0   99.75      .1       0
   306.1    .055       0  373.86    .025       0  414.35     .05       0
  539.51     .06       0  957.84     .04       0 1236.36      .1       0
#XS Ineff= 2 , 0
             942  1876.6 1251.06          1876.6
Permanent Ineff=
       F       F
Bank Sta=957.84,1236.36
XS Rating Curve= 0 ,0
Exp/Cntr=0.5,0.3

Type RM Length L Ch R = 1 ,121779  ,655.5,761.1,851.4
XS GIS Cut Line= 2
2153652.58566114359762.6585659072153585.08212653361673.706907956
#Sta/Elev= 30
       0 1989.43   108.8 1987.62   138.3  1984.5   151.5 1975.91   167.7 1978.25
   220.4 1966.62   335.7 1928.63   407.5 1923.32   463.3 1910.43   620.9 1859.68
   678.2 1859.31   709.6 1854.31   857.3 1864.47   875.9 1857.63   877.9 1856.24
   886.8 1852.06  1147.4  1855.3  1204.6 1865.22  1310.3  1868.8  1418.7 1873.66
  1510.6 1884.07  1530.3  1888.6  1546.7 1900.55  1576.2 1903.13  1582.8  1908.4
    1632 1939.11    1658 1940.72  1674.7 1955.48  1791.2 2005.44  1912.2 2044.48
#Mann= 10 ,-1 , 0
       0     .05       0   108.8      .1       0   167.7      .1       0
   678.2    .055       0   875.9      .1       0   877.9     .04       0
  1147.4     .05       0  1310.3     .06       0  1582.8    .055       0
  1791.2      .1       0
Bank Sta=877.9,1147.4
XS Rating Curve= 0 ,0
Exp/Cntr=0.3,0.1

Type RM Length L Ch R = 1 ,121018  ,1382.5,1510.3,1655.7
XS GIS Cut Line= 2
2153630.58738865359759.9082594092152340.59273809361024.016729686
#Sta/Elev= 30
       0 1981.57   73.781958.188    84.3 1948.36     115 1945.62  191.651917.599
   285.4 1872.96   358.5  1869.7  461.011854.729  532.541857.983   597.3 1863.62
   749.9 1865.41  798.081859.025   813.2 1856.35   857.7 1850.81  1031.1 1850.84
  1062.6 1855.72  1096.8 1860.74    1139 1857.24  1206.4 1872.77  1281.8 1931.52
  1293.6 1943.31  1304.7 1962.59    1392 2036.69  1424.2 2053.65  1443.6 2071.03
  1473.2 2084.68 1517.552090.796  1607.9 2091.08 1771.942073.467  1806.1 2071.53
#Mann= 10 ,-1 , 0
       0      .1       0   73.78     .06       0  191.65      .1       0
  461.01      .1       0  532.54      .1       0  798.08      .1       0
   813.2     .04       0  1062.6      .1       0 1517.55    .055       0
 1771.94     .06       0
Bank Sta=813.2,1062.6
XS Rating Curve= 0 ,0
Exp/Cntr=0.3,0.1

Type RM Length L Ch R = 1 ,119508  ,1411.4,1500,1602.2
XS GIS Cut Line= 3
     2153448.101      359306.137     2152553.547      359039.987
     2151687.196      358777.182
#Sta/Elev= 30
       0 1962.52   26.821953.053   54.571942.126   100.7 1913.99   172.6 1877.84
  222.231869.397   282.1 1865.87   515.1 1868.22  716.44 1860.86   751.1 1860.76
   823.4  1852.7   836.6 1848.84    1073 1848.94  1086.8 1854.38  1102.6 1858.36
    1121 1868.63 1129.591869.255  1151.9 1874.59  1213.6  1930.5  1254.7 1962.15
  1289.3 1987.49    1337 2012.61  1388.5 2032.66  1470.8 2054.96 1579.662069.595
 1594.392070.234 1771.572075.146  1796.4 2075.03  1810.2 2068.84  1838.6 2073.37
#Mann= 11 ,-1 , 0
       0     .06       0   26.82      .1       0   54.57      .1       0
  222.23     .05       0  716.44      .1       0   823.4     .04       0
  1086.8      .1       0 1129.59      .1       0 1579.66    .055       0
 1594.39      .1       0 1771.57     .06       0
Bank Sta=823.4,1086.8
XS Rating Curve= 0 ,0
Exp/Cntr=0.3,0.1

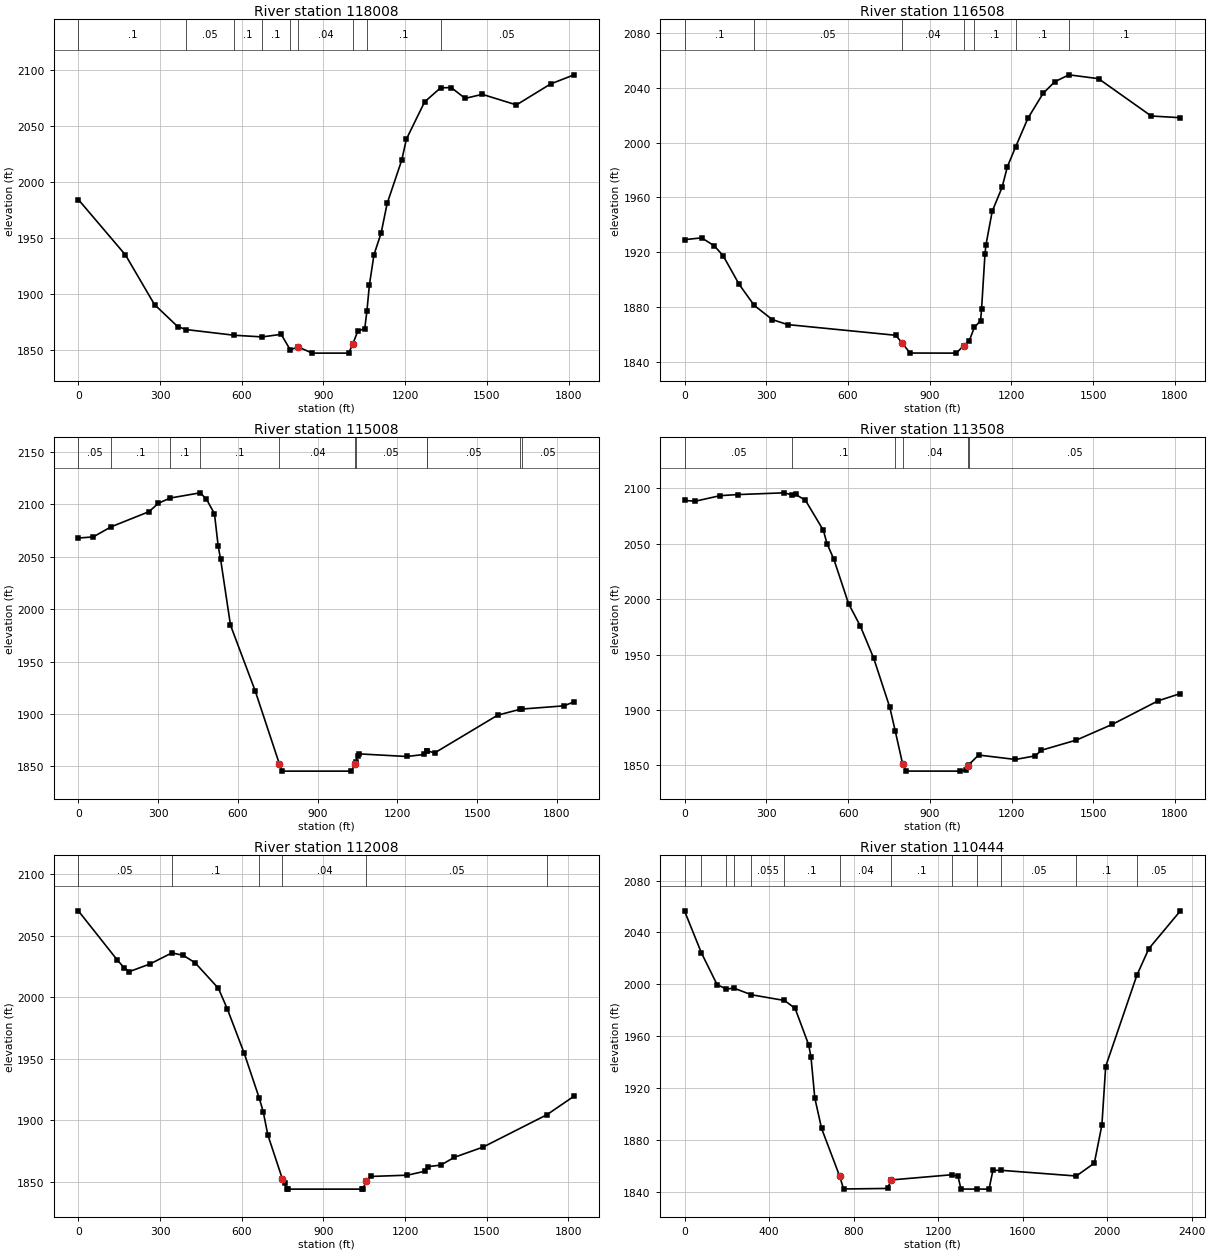
Type RM Length L Ch R = 1 ,118008  ,1449.9,1500,1546.5
XS GIS Cut Line= 3
     2153985.785      358791.217      2153568.57       357981.95
     2153140.417      357179.234
#Sta/Elev= 30
       0 1984.29   173.1 1934.82   279.7 1890.55   364.6 1870.94   396.21868.239
  572.381863.171  675.161861.693   744.8 1863.98  777.941850.259   807.5 1852.67
   859.2 1847.23   992.7 1847.22  1007.5 1855.21  1026.1 1866.82  1051.7 1869.14
 1059.511884.473  1068.7    1908  1085.6 1935.07  1111.7 1954.29    1134 1980.81
  1187.5 2019.44  1204.6 2038.17  1271.5 2071.41 1330.052083.938  1369.4 2084.15
  1420.2 2074.53  1483.3 2078.14  1608.6  2068.7    1734 2087.39  1820.2 2095.55
#Mann= 9 ,-1 , 0
       0      .1       0   396.2     .05       0  572.38      .1       0
  675.16      .1       0  777.94      .1       0   807.5     .04       0
  1007.5      .1       0 1059.51      .1       0 1330.05     .05       0
Bank Sta=807.5,1007.5
XS Rating Curve= 0 ,0
Exp/Cntr=0.3,0.1

Type RM Length L Ch R = 1 ,116508  ,1599.2,1500,1396.2
XS GIS Cut Line= 3
     2155053.524      358624.677     2155016.035      357715.582
     2155011.999      356804.843
#Sta/Elev= 30
       0 1929.19    62.4 1930.49   108.4 1924.71   141.2 1917.45   200.3 1896.44
  255.45 1881.16   321.8  1870.8   377.6 1867.16     775 1859.34   797.7 1853.98
   827.5 1846.38   997.5 1846.31    1025 1851.83  1044.6 1855.11 1063.941865.102
  1086.7    1870  1090.3 1878.45  1102.9 1918.82  1106.2 1925.08  1129.4 1949.84
  1165.5 1967.32  1185.3 1982.54 1215.29 1996.86  1260.6 2017.85  1316.4 2036.02
  1359.1 2044.48 1411.11 2049.55  1519.8 2046.75  1713.4 2019.48  1820.6 2018.22
#Mann= 7 ,-1 , 0
       0      .1       0  255.45     .05       0   797.7     .04       0
    1025      .1       0 1063.94      .1       0 1215.29      .1       0
 1411.11      .1       0
Bank Sta=797.7,1025
XS Rating Curve= 0 ,0
Exp/Cntr=0.3,0.1

Type RM Length L Ch R = 1 ,115008  ,1611.8,1500,1373.6
XS GIS Cut Line= 3
     2157074.243      357942.143     2156432.131      357310.734
     2155763.269      356617.133
#Sta/Elev= 30
       0 2067.98      56 2069.03  122.472078.581     266 2093.16   300.8 2101.12
  345.192106.125   458.32111.108   481.6 2105.05   511.9 2091.22   525.8 2060.48
   535.1 2047.55   572.2 1984.83   665.7 1921.69   755.5 1852.82   767.1 1845.57
    1026 1845.57  1042.1 1852.77  1043.91854.334  1050.1 1860.29  1056.3 1862.01
  1235.7 1859.53  1299.4 1861.44 1309.911864.339  1311.91864.902  1339.9 1862.95
  1576.8 1898.96 1661.53  1904.6 1666.911904.778  1825.1 1907.83  1864.1 1911.63
#Mann= 11 ,-1 , 0
       0     .05       0  122.47      .1       0  345.19      .1       0
   458.3      .1       0   755.5     .04       0  1042.1      .1       0
  1043.9     .05       0 1309.91      .1       0  1311.9     .05       0
 1661.53      .1       0 1666.91     .05       0
Bank Sta=755.5,1042.1
XS Rating Curve= 0 ,0
Exp/Cntr=0.3,0.1

Type RM Length L Ch R = 1 ,113508  ,1499.4,1500,1502.6
XS GIS Cut Line= 3
     2157710.443      355820.298     2156804.213      355903.039
     2155897.982      355985.781
#Sta/Elev= 30
       0 2089.19    38.2 2088.44   130.4  2093.5   194.3 2094.45   364.3 2096.04
  394.872094.143   407.1 2094.62   443.4 2089.29   509.3 2062.12   522.4 2050.22
   547.5 2036.16   601.5 1996.05   644.7 1975.79   693.8 1946.78   753.1 1902.26
  772.951881.043   799.8 1851.54   812.4 1844.76    1010 1844.72  1033.1 1845.88
  1039.7 1849.28 1042.791850.461  1079.2 1859.25  1214.3 1855.25  1286.8 1858.49
  1309.8 1863.59  1438.3 1872.78  1570.1 1886.96  1738.1  1908.2    1820 1914.79
#Mann= 6 ,-1 , 0
       0     .05       0  394.87      .1       0  772.95      .1       0
   799.8     .04       0  1039.7      .1       0 1042.79     .05       0
Bank Sta=799.8,1039.7
XS Rating Curve= 0 ,0
Exp/Cntr=0.3,0.1

Type RM Length L Ch R = 1 ,112008  ,1481.5,1564.2,1631
XS GIS Cut Line= 3
     2157491.801      354327.005     2156586.234      354421.271
     2155678.864      354489.324
#Sta/Elev= 30
       0 2070.24   141.6 2030.66     168 2023.91   187.8 2020.84   263.7 2027.09
  343.682036.051     385 2034.07   428.6 2028.06   514.4 2007.24   547.4 1990.31
   609.1 1954.45  664.211918.068   679.3 1906.54   695.8 1888.12   749.5 1852.11
   758.5 1848.84   765.1 1844.14   768.4 1843.97  1041.8 1843.97  1045.1 1844.11
  1057.7 1850.93  1074.7 1854.28  1208.3 1855.31    1272 1858.49  1285.3 1862.29
  1331.3 1863.52  1380.7 1869.83    1486 1878.12 1720.311904.414  1820.4 1919.54
#Mann= 6 ,-1 , 0
       0     .05       0  343.68      .1       0  664.21      .1       0
   749.5     .04       0  1057.7     .05       0 1720.31      .1       0
Bank Sta=749.5,1057.7
XS Rating Curve= 0 ,0
Exp/Cntr=0.3,0.1

Type RM Length L Ch R = 1 ,110444  ,1670.8,1618,1548.3
XS GIS Cut Line= 2
2157829.02786277353328.3174295982155682.11122416352380.996898412
#Sta/Elev= 30
       0 2056.19   79.282024.146   153.2 1999.77  197.751996.204  231.651997.095
  316.221991.882  472.461987.482   522.6 1981.45   587.1  1953.2   597.9 1943.83
   615.8 1912.44   647.9 1888.84   733.3 1852.12   752.1 1842.11   960.1 1842.53
   977.5 1849.08 1264.24 1853.09  1293.6 1851.94  1307.9 1842.05 1382.451842.022
  1440.6    1842    1459 1856.42  1496.41856.534 1853.621852.109  1939.1 1862.04
  1974.9 1891.39  1992.8 1936.55 2140.592006.998  2197.2 2027.46  2346.6 2056.63
#Mann= 13 ,-1 , 0
       0      .1       0   79.28      .1       0  197.75      .1       0
  231.65      .1       0  316.22    .055       0  472.46      .1       0
   733.3     .04       0   977.5      .1       0 1264.24      .1       0
 1382.45      .1       0  1496.4     .05       0 1853.62      .1       0
 2140.59     .05       0
Bank Sta=733.3,977.5
XS Rating Curve= 0 ,0
Exp/Cntr=0.3,0.1

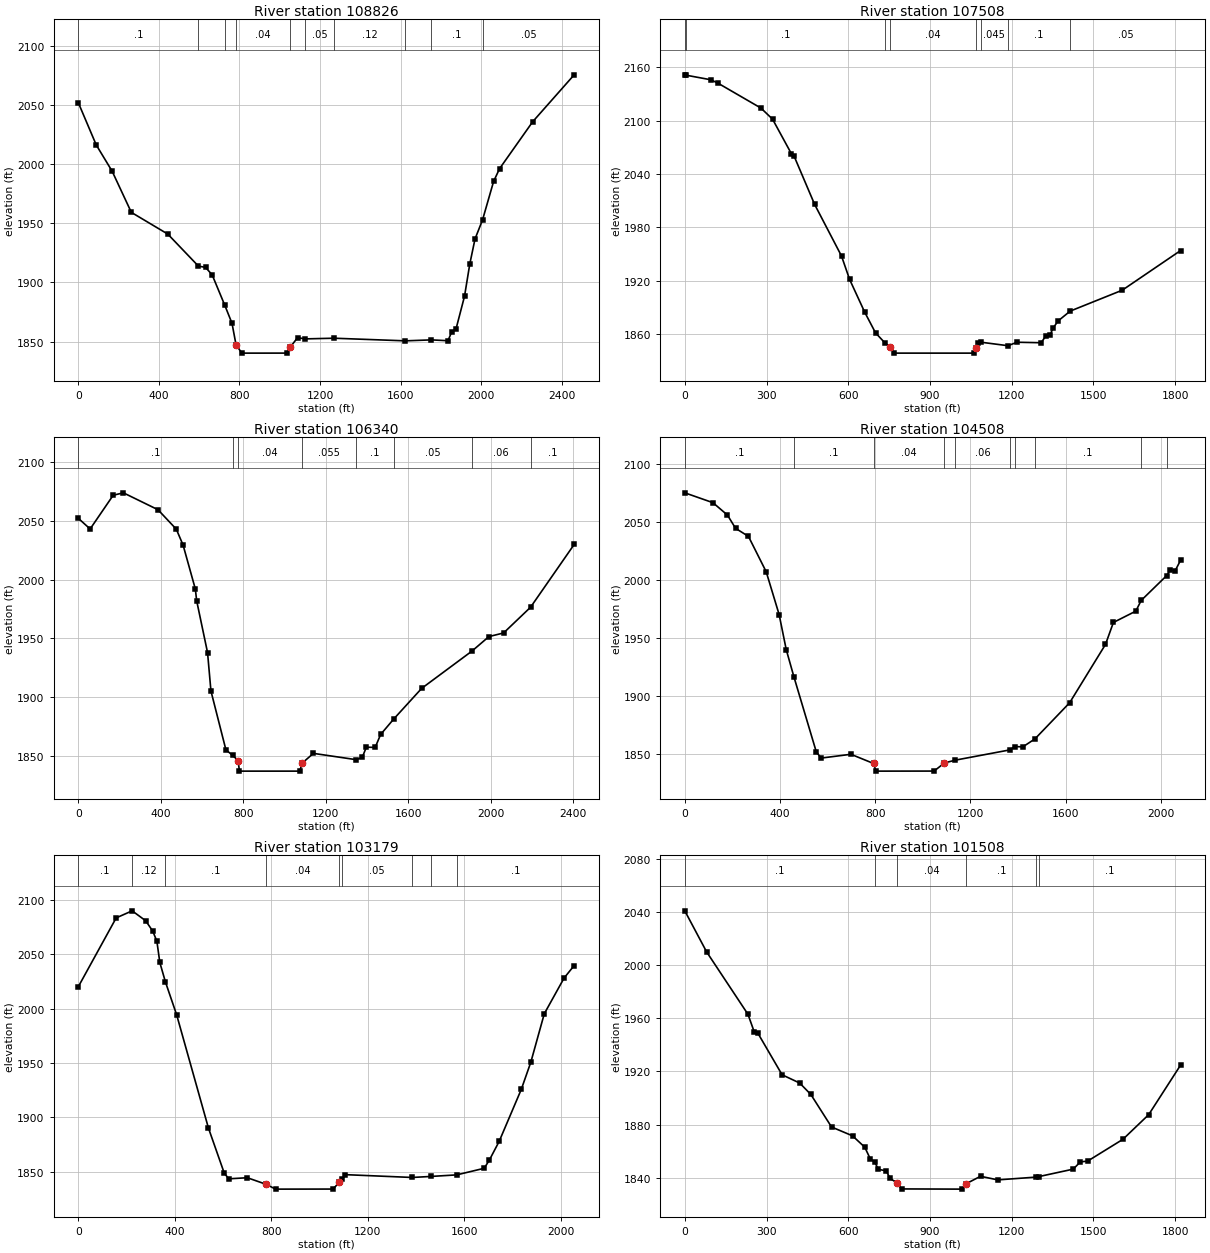
Type RM Length L Ch R = 1 ,108826  ,1295.7,1317.8,1339.4
XS GIS Cut Line= 2
2158174.55464527351357.6751410652155718.50416158351529.302765227
#Sta/Elev= 30
       0 2051.94    88.9 2016.24   167.9    1994   263.2 1959.21   444.1 1940.86
  596.391913.741   631.6 1912.73   664.5 1906.37  726.151881.081   763.1 1865.39
   782.9 1847.35   811.6 1840.17  1036.2 1840.19  1052.6 1845.26  1088.7  1853.3
 1125.121852.204 1269.311852.786 1623.831850.556 1752.971851.369  1835.3 1850.66
    1855 1858.46  1874.8 1860.21  1917.5 1888.21  1943.8  1915.6  1969.7 1936.72
 2007.161952.889  2062.2 1985.49  2091.8 1996.23  2256.1 2035.87    2462 2075.54
#Mann= 10 ,-1 , 0
       0      .1       0  596.39      .1       0  726.15      .1       0
   782.9     .04       0  1052.6      .1       0 1125.12     .05       0
 1269.31     .12       0 1623.83     .05       0 1752.97      .1       0
 2007.16     .05       0
Bank Sta=782.9,1052.6
XS Rating Curve= 0 ,0
Exp/Cntr=0.3,0.1

Type RM Length L Ch R = 1 ,107508  ,1165.7,1168,1170.8
XS GIS Cut Line= 3
     2158010.419       350170.48     2157101.971      350117.355
     2156193.523      350064.231
#Sta/Elev= 30
       0 2151.52     3.82151.163    95.4 2145.97   121.7 2142.15   279.4 2114.16
   322.1 2101.69   391.1 2062.92   401.1 2060.19   476.6 2005.83   575.2 1947.87
   604.8 1921.65   660.6 1884.57   700.1 1861.49  734.071850.343   751.9    1846
   769.1  1838.7  1061.6 1838.69  1070.2 1844.75    1078 1850.19 1086.04    1851
 1186.32 1847.03  1219.3 1850.92    1308 1850.38  1324.5 1857.68  1340.9 1858.93
  1350.8  1866.4  1370.5 1874.93 1414.571885.921  1605.8 1909.43    1820 1954.02
#Mann= 8 ,-1 , 0
       0     .05       0     3.8      .1       0  734.07      .1       0
   751.9     .04       0  1070.2      .1       0 1086.04    .045       0
 1186.32      .1       0 1414.57     .05       0
Bank Sta=751.9,1070.2
XS Rating Curve= 0 ,0
Exp/Cntr=0.3,0.1

Type RM Length L Ch R = 1 ,106340  ,1804.7,1832,1852.9
XS GIS Cut Line= 3
2158073.94534834349019.9885361062156428.68743397348895.706463438
2155913.80456148349446.098499542
#Sta/Elev= 30
       0 2052.12    57.2 2043.05     169 2071.74   218.4  2073.8   386.2 2059.42
     475 2042.86   507.9 2029.31   567.2 1991.96   573.7 1981.94   626.4  1937.9
   642.8  1905.3   715.4 1855.21  748.43 1850.43   774.4 1846.11     781 1837.09
  1073.8 1837.09  1084.5 1843.84  1139.6 1852.19 1347.741846.815  1376.5 1848.86
  1396.3 1857.48    1439 1857.24  1465.4 1868.26 1528.841881.388  1664.5  1907.5
 1908.531939.239  1990.4 1951.53  2061.5  1954.6 2192.231976.483  2403.6 2029.88
#Mann= 8 ,-1 , 0
       0      .1       0  748.43      .1       0   774.4     .04       0
  1084.5    .055       0 1347.74      .1       0 1528.84     .05       0
 1908.53     .06       0 2192.23      .1       0
Bank Sta=774.4,1084.5
XS Rating Curve= 0 ,0
Exp/Cntr=0.3,0.1

Type RM Length L Ch R = 1 ,104508  ,1299.8,1328.6,1365.3
XS GIS Cut Line= 3
     2158180.558       347367.42     2157280.461       347132.67
2156156.74524254346874.902672761
#Sta/Elev= 30
       0 2074.94   118.2 2066.45   179.3 2055.75   213.2 2044.37   267.4  2037.4
     342  2006.9   396.3 1970.05   426.2 1939.81   458.21916.546   552.2 1851.89
   572.6 1846.37     698 1849.64     793 1841.72   803.1 1835.13  1047.3 1835.18
  1090.6 1842.15  1136.11844.576 1367.591853.499 1385.261856.318    1420 1856.02
 1471.03 1862.89  1616.8 1894.03  1767.4  1944.3  1800.7 1963.25  1894.7 1972.98
 1917.521982.238 2024.75 2003.67  2039.4 2008.33  2059.6 2007.58  2083.1 2016.94
#Mann= 10 ,-1 , 0
       0      .1       0   458.2      .1       0     793     .04       0
  1090.6      .1       0  1136.1     .06       0 1367.59      .1       0
 1385.26     .06       0 1471.03      .1       0 1917.52      .1       0
 2024.75     .06       0
Bank Sta=793,1090.6
XS Rating Curve= 0 ,0
Exp/Cntr=0.3,0.1

Type RM Length L Ch R = 1 ,103179  ,1716.2,1671.4,1613.1
XS GIS Cut Line= 2
2158742.70126318346380.474040381 2156902.1429489345463.153980207
#Sta/Elev= 30
       0 2020.04     157 2083.21  223.232089.701   279.4 2080.57   308.8 2071.01
   325.8 2061.76     338 2042.27  361.022024.554   407.7 1994.27   539.6 1890.28
   605.6 1848.62   624.3 1843.63   700.9 1844.62   778.4 1838.63   818.2 1834.16
  1056.5 1834.22  1082.9  1840.6 1094.961843.286  1107.8 1847.45 1384.541844.871
 1461.941845.801 1569.081847.234  1683.4  1853.3  1705.3 1861.04  1745.7 1878.12
  1837.3  1925.8  1876.9 1950.81  1932.6  1995.2    2015 2028.08  2056.5 2039.45
#Mann= 9 ,-1 , 0
       0      .1       0  223.23     .12       0  361.02      .1       0
   778.4     .04       0  1082.9      .1       0 1094.96     .05       0
 1384.54     .06       0 1461.94    .045       0 1569.08      .1       0
Bank Sta=778.4,1082.9
XS Rating Curve= 0 ,0
Exp/Cntr=0.3,0.1

Type RM Length L Ch R = 1 ,101508  ,1462.6,1500,1528.7
XS GIS Cut Line= 3
     2159248.257      344505.493     2158342.966      344413.037
     2157437.675      344320.581
#Sta/Elev= 30
       0 2040.97    80.2 2010.02   231.9 1963.04     255 1949.71   268.1 1948.88
   357.2  1917.5   421.8 1911.29   462.7 1902.67   538.6 1878.21   615.7 1871.54
   660.6 1862.97   680.4 1854.39  698.081851.491   710.1 1846.34   739.7 1845.14
   752.9 1839.57   778.1 1836.19   795.8 1831.56  1016.8 1831.41  1033.3 1835.54
  1085.5 1841.08  1148.7 1838.37 1290.34 1840.47 1298.751840.813  1425.7 1846.46
  1452.1 1851.95  1478.5 1852.49  1608.2 1868.92  1702.7 1887.47    1820 1924.85
#Mann= 6 ,-1 , 0
       0      .1       0  698.08      .1       0   778.1     .04       0
  1033.3      .1       0 1290.34      .1       0 1298.75      .1       0
Bank Sta=778.1,1033.3
XS Rating Curve= 0 ,0
Exp/Cntr=0.3,0.1

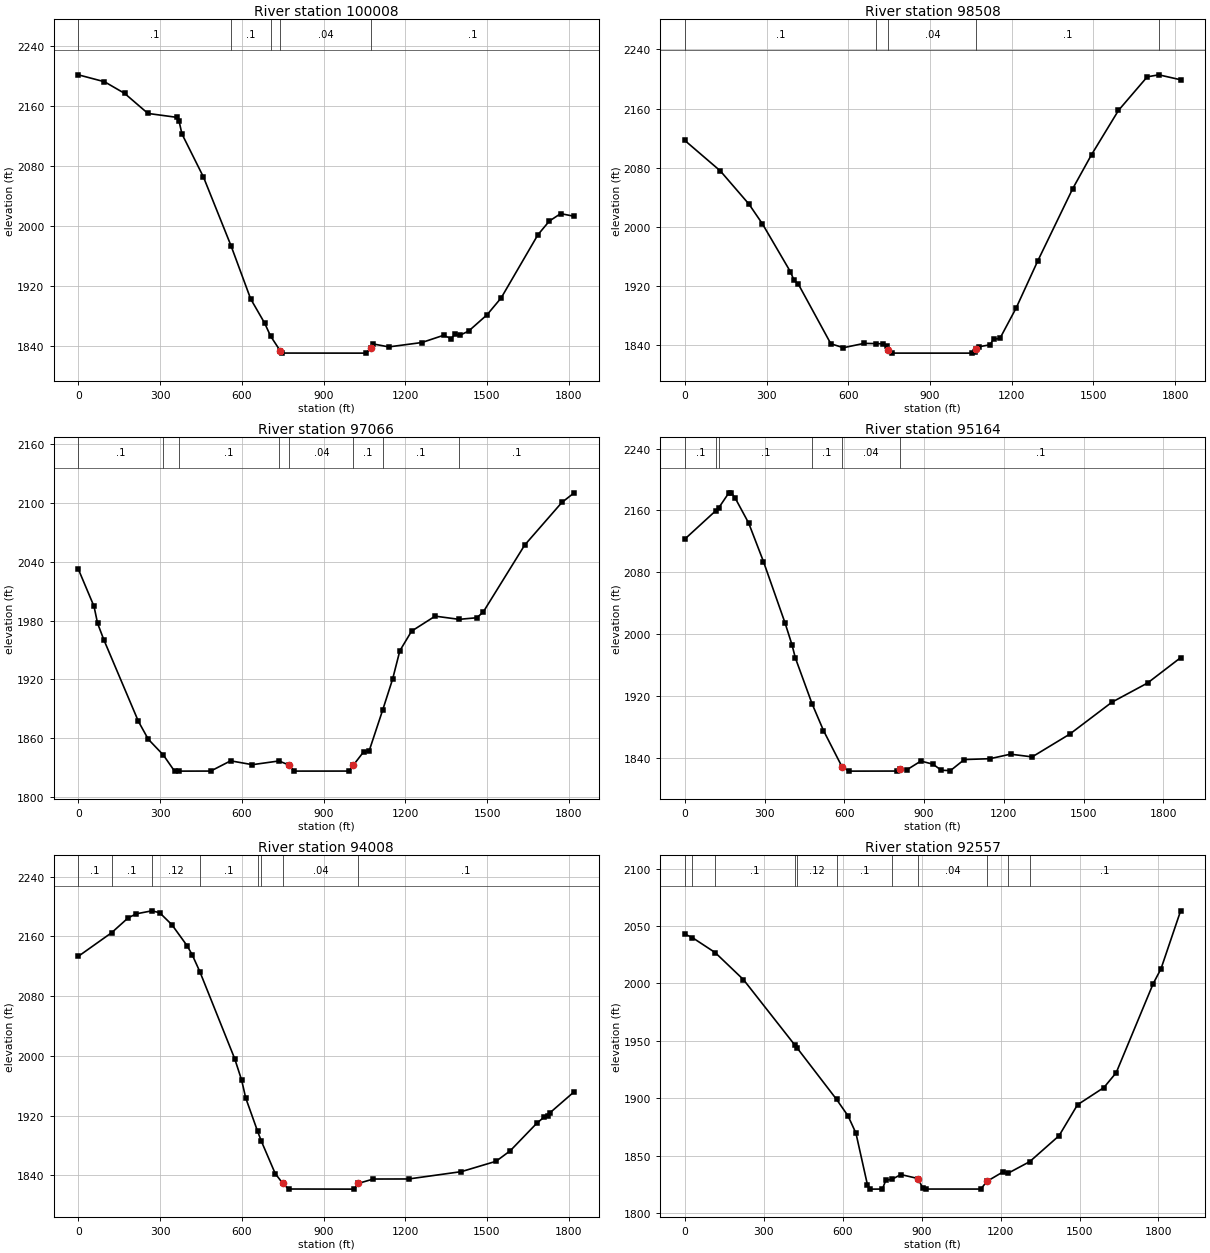
Type RM Length L Ch R = 1 ,100008  ,1535.7,1500,1461.6
XS GIS Cut Line= 3
     2159544.833      343257.351     2158683.624       342963.38
     2157822.414       342669.41
#Sta/Elev= 30
       0 2201.82      96 2192.58   169.9 2177.02   255.5 2150.24     363 2144.96
   369.9 2139.66   380.3 2122.89   459.4  2065.2  560.891973.127   632.5 1902.58
   684.2 1869.95  705.44 1853.01   740.8 1833.32   747.8 1830.18  1056.3 1830.09
  1073.2 1836.47  1080.6 1842.46  1139.5 1838.41  1260.9 1844.25  1340.6  1853.9
  1368.3 1849.53  1382.2    1855  1399.5  1853.8  1432.4 1859.46  1500.1 1881.25
  1552.1 1903.86    1687 1988.22  1728.9 2006.49  1770.5 2016.43    1820 2012.86
#Mann= 5 ,-1 , 0
       0      .1       0  560.89      .1       0  705.44      .1       0
   740.8     .04       0  1073.2      .1       0
Bank Sta=740.8,1073.2
XS Rating Curve= 0 ,0
Exp/Cntr=0.3,0.1

Type RM Length L Ch R = 1 ,98508   ,1475.3,1441.8,1403.9
XS GIS Cut Line= 3
     2159753.899      341576.858     2158849.131      341479.422
     2157944.362      341381.985
#Sta/Elev= 30
       0 2116.77   130.1 2075.63   235.7 2030.46   285.2 2003.68   387.5  1939.1
   400.7 1927.62   417.2  1921.9     536 1841.46   582.2 1836.12   658.1 1841.99
  702.621841.684   727.4 1841.33   740.6 1838.12   747.2  1833.5   760.3 1828.81
    1054 1828.78  1063.9 1830.08  1070.5  1834.3  1080.4 1837.46    1120 1840.01
  1133.2 1847.65  1156.6 1848.59  1216.2 1889.83  1294.9 1953.11  1423.6  2051.3
  1492.9 2097.45  1591.9 2157.49  1697.5 2202.94 1739.942205.635    1820 2198.95
#Mann= 5 ,-1 , 0
       0      .1       0  702.62      .1       0   747.2     .04       0
  1070.5      .1       0 1739.94      .1       0
Bank Sta=747.2,1070.5
XS Rating Curve= 0 ,0
Exp/Cntr=0.3,0.1

Type RM Length L Ch R = 1 ,97066   ,1959.5,1901.9,1801.1
XS GIS Cut Line= 2
 2159720.6828112339912.1839773682157923.03140296340195.014465599
#Sta/Elev= 30
       0 2032.36    57.5 1994.46    70.8 1977.02    93.5 1960.45   220.6 1877.14
   256.7 1859.03  312.141842.887   353.1 1826.53  370.651826.538   485.9 1826.59
     559 1837.02   638.7  1833.1  736.321836.882   774.8 1832.55   791.5 1826.56
     994 1826.59  1009.6 1832.72  1047.1  1846.2  1067.2 1846.99 1117.051888.813
  1153.5 1920.31    1180 1949.19  1223.2  1969.2  1309.6 1984.46 1397.551981.209
  1462.3 1982.83  1485.6 1988.46  1638.2 2056.88  1774.5 2100.28  1819.8 2110.13
#Mann= 8 ,-1 , 0
       0      .1       0  312.14      .1       0  370.65      .1       0
  736.32      .1       0   774.8     .04       0  1009.6      .1       0
 1117.05      .1       0 1397.55      .1       0
Bank Sta=774.8,1009.6
XS Rating Curve= 0 ,0
Exp/Cntr=0.3,0.1

Type RM Length L Ch R = 1 ,95164   ,1156.8,1156.3,1159.3
XS GIS Cut Line= 2
2158843.42892398337755.0022874762157644.99465182339183.535939894
#Sta/Elev= 30
       0 2122.84  116.242159.503  127.332163.165   165.3 2182.49   174.7 2182.74
   188.8 2176.39   240.2  2143.6   295.8 2093.85   377.3 2014.02   402.9 1986.32
   415.8 1969.05  478.771909.635   521.6 1875.07   591.3 1828.14   617.1 1822.56
   796.9 1822.66   810.4 1825.31   836.7  1824.6   887.8 1835.59   933.7 1831.52
   964.4  1823.7     999 1823.22  1051.1 1837.54  1148.1 1838.66  1224.9  1844.5
  1306.4 1840.98  1447.8 1870.48  1606.3 1911.77  1740.3 1936.59  1864.7  1969.4
#Mann= 6 ,-1 , 0
       0      .1       0  116.24      .1       0  127.33      .1       0
  478.77      .1       0   591.3     .04       0   810.4      .1       0
Bank Sta=591.3,810.4
XS Rating Curve= 0 ,0
Exp/Cntr=0.3,0.1

Type RM Length L Ch R = 1 ,94008   ,1354.8,1450.2,1531.3
XS GIS Cut Line= 3
     2158123.697      336836.059     2157528.083      337524.124
     2156926.013       338206.47
#Sta/Elev= 30
       0 2133.38  122.49 2165.07     183 2184.92   213.3  2190.3  269.822194.274
   298.5 2191.74   343.6 2175.59     400 2147.17     418 2135.41   446.12112.771
   574.2  1996.1   599.6  1967.4   614.3 1943.92  658.241898.928  671.851885.877
   722.7  1842.6   750.1 1829.59   771.5 1821.91  1012.7 1821.75  1027.3 1829.35
  1082.7 1835.27  1212.5 1835.35  1406.2 1845.18  1533.3 1859.03  1585.2 1873.04
  1683.6 1910.23  1710.7 1918.42  1722.3 1919.25  1730.2 1923.63    1820 1952.09
#Mann= 8 ,-1 , 0
       0      .1       0  122.49      .1       0  269.82     .12       0
   446.1      .1       0  658.24      .1       0  671.85      .1       0
   750.1     .04       0  1027.3      .1       0
Bank Sta=750.1,1027.3
XS Rating Curve= 0 ,0
Exp/Cntr=0.3,0.1

Type RM Length L Ch R = 1 ,92557   ,1477.3,1601.7,1731
XS GIS Cut Line= 2
2157635.40717764336235.3876303742155785.02466142336590.124174934
#Sta/Elev= 30
       0  2042.9   28.742039.888  115.442026.841   222.9  2003.3  418.731946.164
  427.761943.502  576.511899.083   620.4 1884.64   650.3 1869.63   693.9 1824.81
   703.9 1820.91   750.7 1820.96     764 1828.66  788.681829.602   820.8 1833.61
   885.7 1830.16   904.3  1821.9   916.6 1820.98  1124.8 1820.97  1148.2 1827.69
  1208.3  1835.8 1228.84 1834.81 1310.751844.848  1422.1 1867.38  1492.3 1894.36
  1592.5 1909.33  1639.3 1922.28  1779.6 1999.68  1809.6  2012.8  1884.1  2063.2
#Mann= 11 ,-1 , 0
       0      .1       0   28.74      .1       0  115.44      .1       0
  418.73      .1       0  427.76     .12       0  576.51      .1       0
  788.68      .1       0   885.7     .04       0  1148.2      .1       0
 1228.84      .1       0 1310.75      .1       0
Bank Sta=885.7,1148.2
XS Rating Curve= 0 ,0
Exp/Cntr=0.3,0.1

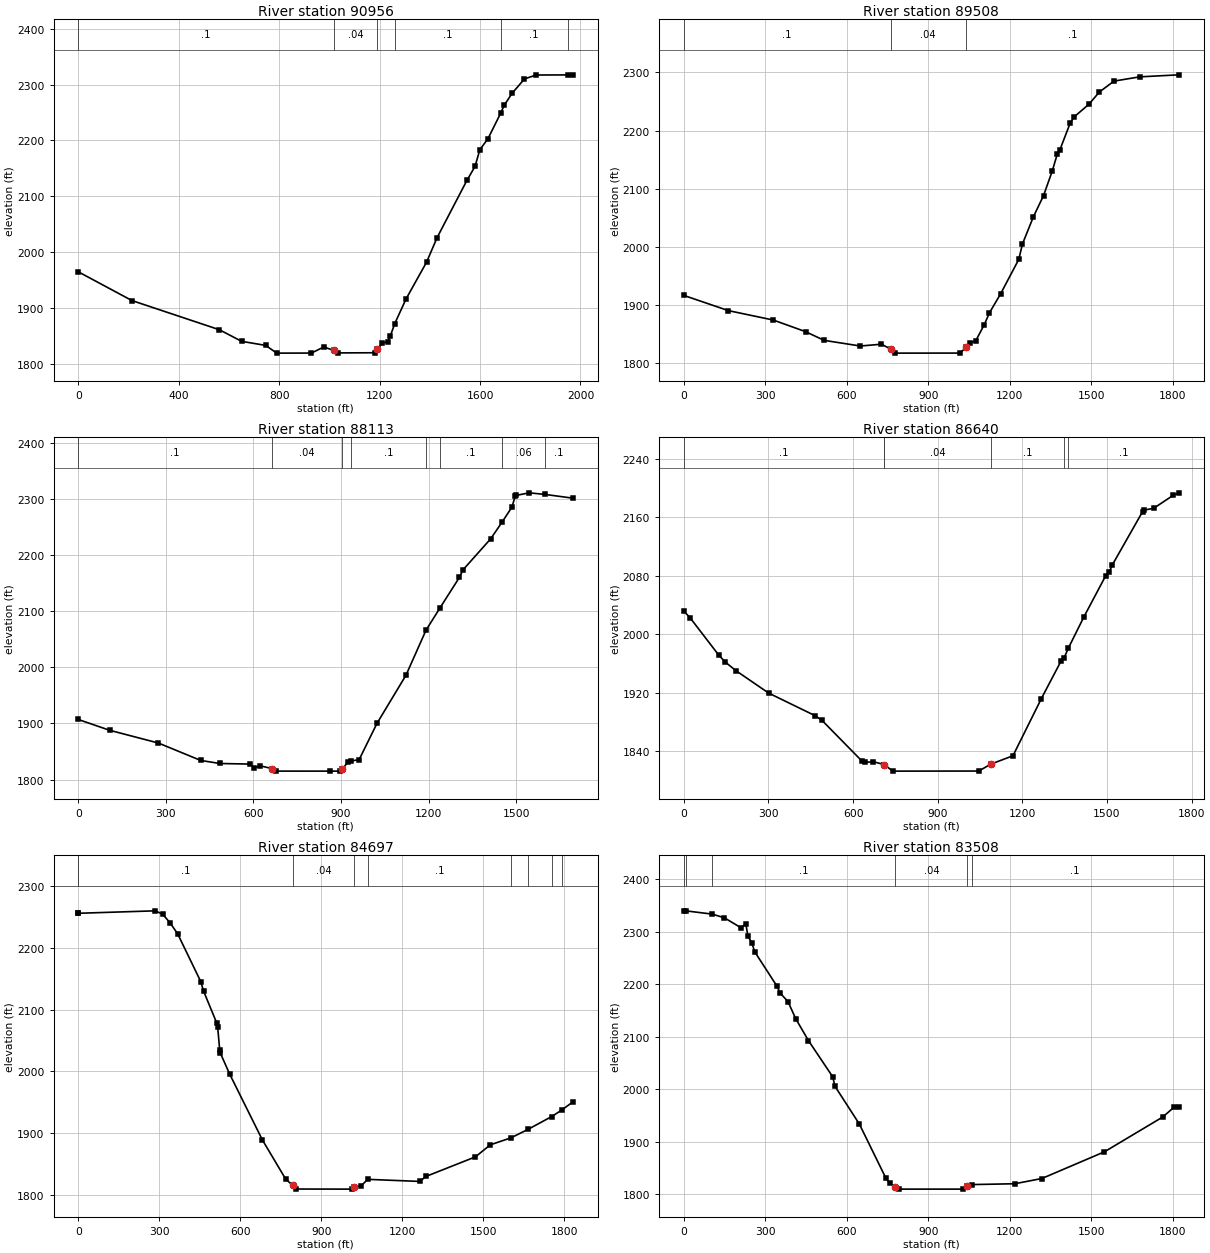
Type RM Length L Ch R = 1 ,90956   ,1368.4,1448.1,1528.5
XS GIS Cut Line= 2
2157649.78838891335976.525827587 2156638.3098632334284.336635293
#Sta/Elev= 30
       0 1964.43   213.4 1912.94     562 1860.59   650.5 1839.84   746.2 1832.53
   790.6 1818.69   928.7 1818.81   977.9 1829.78  1016.6 1823.67  1035.2 1819.07
  1180.4 1819.36  1191.2 1825.78    1211 1836.44  1231.9 1839.34  1242.3 1848.95
 1260.61 1871.78  1305.1 1915.58  1386.9 1981.54  1428.9 2025.58  1547.6 2128.14
  1580.1 2153.24  1599.2 2183.22  1631.5  2202.9 1681.852248.351    1696 2262.62
  1727.1 2283.97  1776.7 2309.99  1823.1  2317.1 1949.492317.269  1971.4 2317.43
#Mann= 6 ,-1 , 0
       0      .1       0  1016.6     .04       0  1191.2      .1       0
 1260.61      .1       0 1681.85      .1       0 1949.49     .05       0
Bank Sta=1016.6,1191.2
XS Rating Curve= 0 ,0
Exp/Cntr=0.3,0.1

Type RM Length L Ch R = 1 ,89508   ,1272.3,1394.4,1483.8
XS GIS Cut Line= 3
     2158299.275      335844.712      2158510.24       334956.77
     2158716.659      334071.486
#Sta/Elev= 30
       0 1916.13   164.1 1889.94   329.3 1873.73   448.5 1853.67   516.2 1838.78
   649.7 1829.04   727.2 1832.15     761 1823.88   777.8 1816.79  1017.1 1816.88
  1037.3 1826.53  1054.2 1834.62  1074.4  1838.1  1105.7 1865.87  1124.9 1886.29
  1165.4 1918.51  1232.7 1978.22  1246.2 2004.74  1286.6 2051.63  1323.7 2087.93
  1355.4 2129.57  1374.2 2159.18  1384.3 2167.16  1421.4 2212.32  1436.2 2223.37
  1490.9 2245.31  1529.3 2266.31  1583.1 2285.08  1677.4 2292.38  1821.7 2295.89
#Mann= 3 , 0 , 0
       0      .1       0     761     .04       0  1037.3      .1       0
Bank Sta=761,1037.3
XS Rating Curve= 0 ,0
Exp/Cntr=0.3,0.1

Type RM Length L Ch R = 1 ,88113   ,1395.8,1473.3,1532.8
XS GIS Cut Line= 2
2158850.93016743336223.324528489 2160307.0278081335353.548871124
#Sta/Elev= 30
       0 1907.14   107.3 1887.94   274.4 1865.19   419.6 1834.15   485.3 1828.72
   587.8 1827.68     603 1821.12   623.9  1824.5   664.2  1819.6   676.7 1815.15
   864.1 1815.12   897.3 1815.16   904.9 1818.75   924.1 1831.48  934.921833.165
   962.3 1835.58  1023.4 1900.14  1122.8 1985.98 1191.512066.316 1239.152105.752
    1306 2160.42  1317.7 2173.45  1413.2 2229.18 1452.862259.439  1485.8 2285.46
  1497.3 2305.31  1499.7 2306.27  1544.5 2311.02 1599.062308.198  1696.1  2301.4
#Mann= 8 ,-1 , 0
       0      .1       0   664.2     .04       0   904.9      .1       0
  934.92      .1       0 1191.51      .1       0 1239.15      .1       0
 1452.86     .06       0 1599.06      .1       0
Bank Sta=664.2,904.9
XS Rating Curve= 0 ,0
Exp/Cntr=0.3,0.1

Type RM Length L Ch R = 1 ,86640   ,2101.4,1943.5,1754
XS GIS Cut Line= 2
2158785.90407892337266.0411044332160540.41185337337251.659893167
#Sta/Elev= 30
       0 2031.55    21.7 2022.76   123.4 1971.62   146.4 1962.12   184.4 1950.26
   300.6 1919.53   464.6 1888.74   489.8 1882.18     632 1826.29   642.7 1824.75
   671.3 1825.62   710.4  1821.8   711.1 1821.63   740.2 1812.78  1045.4  1812.9
    1088 1822.31  1166.7 1833.82  1267.5 1912.11  1337.4 1963.57 1347.571967.374
 1362.521980.582  1417.2 2023.06  1494.9 2079.68    1508 2085.06  1517.8 2094.12
  1626.1 2167.66  1632.7 2169.86  1665.5  2172.3  1734.4 2189.95  1754.6 2193.42
#Mann= 6 ,-1 , 0
       0      .1       0   710.4      .1       0   711.1     .04       0
    1088      .1       0 1347.57      .1       0 1362.52      .1       0
Bank Sta=711.1,1088
XS Rating Curve= 0 ,0
Exp/Cntr=0.3,0.1

Type RM Length L Ch R = 1 ,84697   ,1271.1,1188.9,1086.4
XS GIS Cut Line= 2
2160180.88157172339749.1969163542160746.54254818338004.276616085
#Sta/Elev= 30
       0 2255.33     .56 2255.33   285.4 2259.28     313 2253.69   340.6 2239.61
   368.2 2222.19   453.7 2145.18   464.7 2129.24     513 2078.24   516.5 2071.64
     524 2034.89   526.8 2029.24   560.4 1996.28     682 1889.63   768.2 1826.52
   794.9 1815.93   806.2 1810.22  1013.1 1810.06  1023.5 1813.33  1047.2 1815.07
 1072.751825.835  1264.9 1822.49  1289.7 1830.78  1471.8 1862.16  1526.7 1881.55
 1603.211892.816 1665.621906.318 1753.841927.083 1792.191937.861  1834.3  1951.4
#Mann= 9 ,-1 , 0
       0      .1       0     .56      .1       0   794.9     .04       0
  1023.5      .1       0 1072.75      .1       0 1603.21      .1       0
 1665.62      .1       0 1753.84      .1       0 1792.19      .1       0
Bank Sta=794.9,1023.5
XS Rating Curve= 0 ,0
Exp/Cntr=0.3,0.1

Type RM Length L Ch R = 1 ,83508   ,1443.5,1367.3,1287.9
XS GIS Cut Line= 3
     2161976.986       339633.41     2161601.896       338805.57
      2161198.53      337985.163
#Sta/Elev= 30
       0 2339.58    6.482339.676  104.68 2333.41   149.3 2326.38   210.6 2307.43
   228.6 2314.61   235.8 2291.39   250.2 2279.17     261 2261.71   343.3 2195.96
   354.6 2183.09   383.4  2166.9   412.3 2134.01   459.1 2092.39   548.7 2023.25
   556.3 2005.73   646.4 1933.63   743.6 1831.05     758 1820.75   779.3 1814.61
   794.1 1809.62    1030 1809.61  1044.6 1815.22 1059.991818.258  1218.9 1819.86
  1318.8 1829.84  1549.1  1880.7  1763.8 1946.97    1805 1965.38  1823.1 1966.81
#Mann= 6 ,-1 , 0
       0      .1       0    6.48     .05       0  104.68      .1       0
   779.3     .04       0  1044.6      .1       0 1059.99      .1       0
Bank Sta=779.3,1044.6
XS Rating Curve= 0 ,0
Exp/Cntr=0.3,0.1