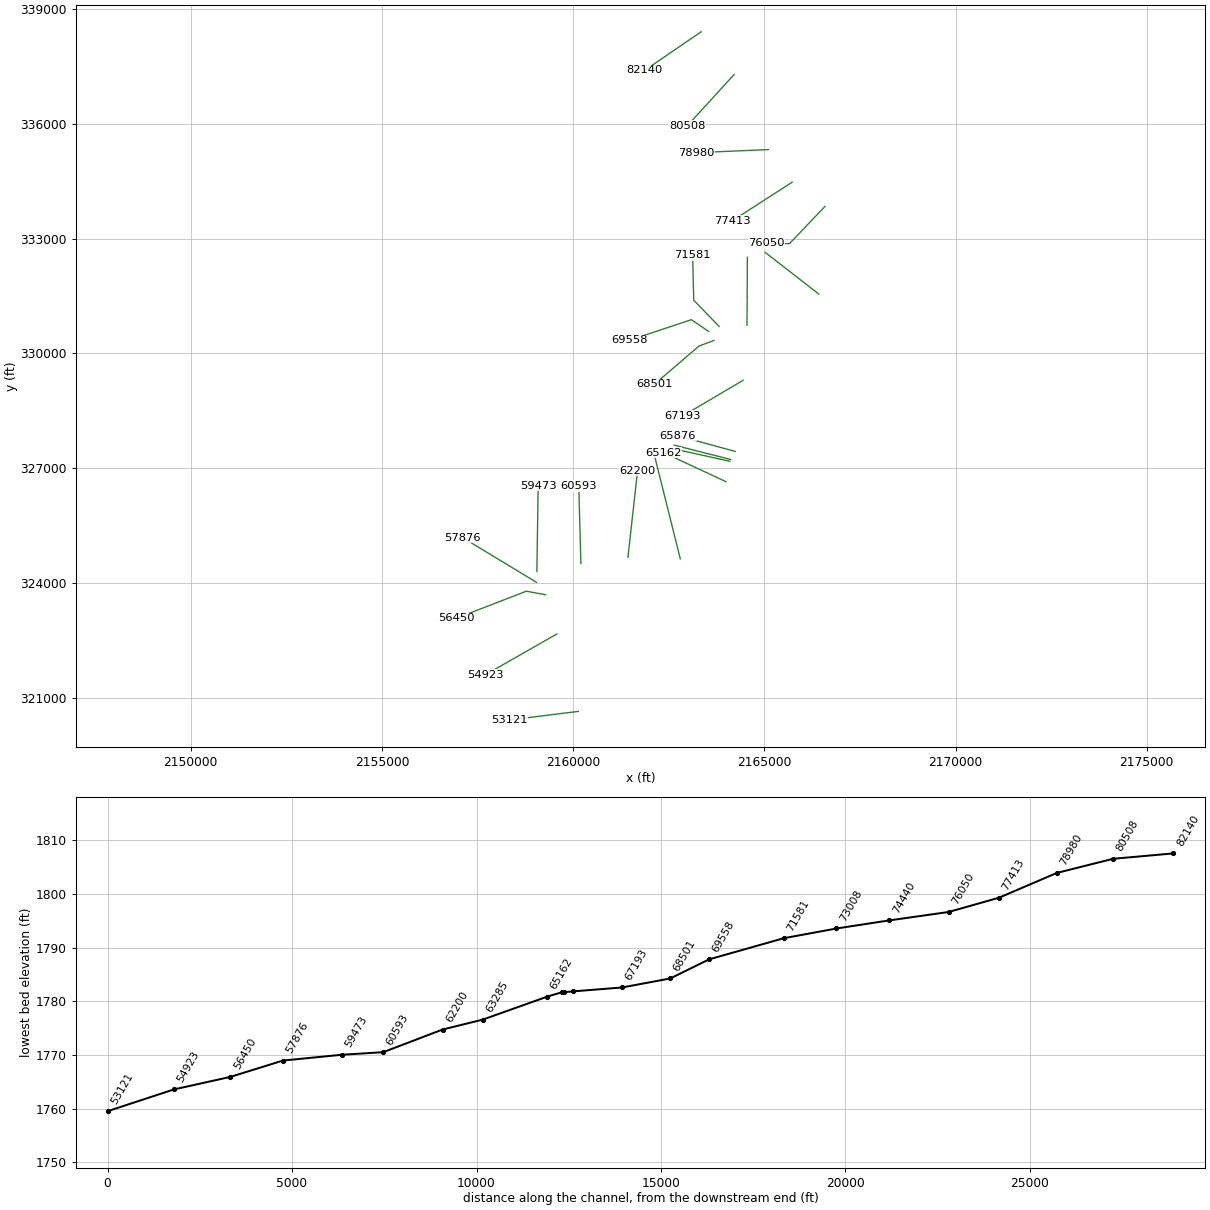
HEC-RAS study GRBRRV5.prj: GRBRRV5

--- GRBRRV5.g01 (geometry) --- (continued)

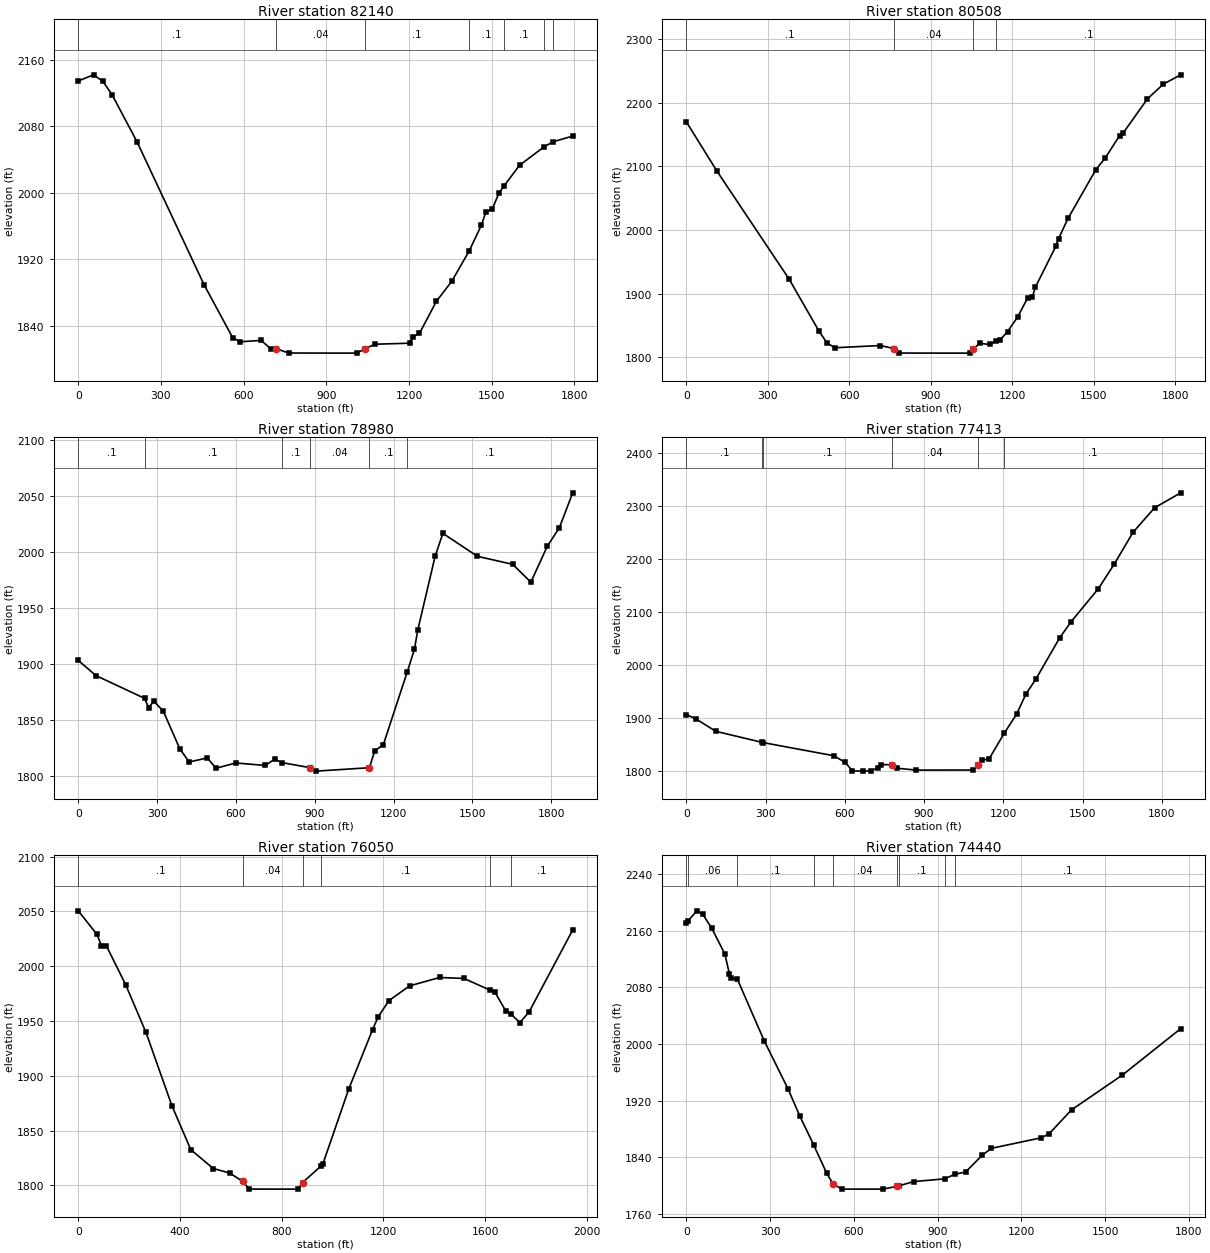
Type RM Length L Ch R = 1 ,82140   ,1597.2,1632.7,1665.5
XS GIS Cut Line= 2
2163348.01946961338412.7049212772161867.28734667337400.693758117
#Sta/Elev= 30
       0 2134.29    55.3 2141.66    89.5  2133.8   122.9 2117.62   213.2 2061.23
   456.3 1889.71   560.4 1825.91   587.8 1821.22   663.3 1822.84     700 1812.32
     716 1813.05   763.2 1807.69    1011 1807.56  1040.8  1813.1  1077.1 1818.26
  1202.2 1819.48    1214 1827.01  1237.6 1831.21    1299 1869.75  1354.8 1893.78
 1417.921930.208  1462.1 1961.09  1478.4 1976.62  1501.8 1980.55  1525.6 1999.37
 1542.852007.647  1601.2 2033.26  1689.22055.049 1722.352061.308  1793.5 2068.11
#Mann= 7 ,-1 , 0
       0      .1       0     716     .04       0  1040.8      .1       0
 1417.92      .1       0 1542.85      .1       0  1689.2      .1       0
 1722.35      .1       0
Bank Sta=716,1040.8
XS Rating Curve= 0 ,0
Exp/Cntr=0.3,0.1

Type RM Length L Ch R = 1 ,80508   ,1620,1527.3,1407.9
XS GIS Cut Line= 3
     2164208.008      337292.811     2163593.899      336621.268
      2162979.79      335949.725
#Sta/Elev= 30
       0 2169.96     112 2093.04   378.7 1922.74   489.2 1840.61     518 1822.62
     547 1815.02   714.9 1818.48   764.2 1813.76   782.8 1806.66  1044.9 1806.56
  1055.2  1812.9    1080 1821.87  1118.4 1820.13 1141.791826.251  1156.1 1827.63
  1182.8 1840.51  1219.4 1863.01  1256.5 1893.19  1273.9  1894.7    1285 1909.99
  1360.6 1974.59  1370.3 1986.24  1405.1 2017.99  1507.3 2094.38  1542.9 2113.47
  1594.8    2148  1607.2 2151.59  1697.7 2205.94  1756.3 2229.07    1820 2243.62
#Mann= 4 ,-1 , 0
       0      .1       0   764.2     .04       0  1055.2      .1       0
 1141.79      .1       0
Bank Sta=764.2,1055.2
XS Rating Curve= 0 ,0
Exp/Cntr=0.3,0.1

Type RM Length L Ch R = 1 ,78980   ,1518.8,1567.3,1635
XS GIS Cut Line= 2
 2165108.6754782335331.8398699062163228.56220455335251.463280141
#Sta/Elev= 30
       0 1902.84    67.5 1889.29  252.171868.967   267.9 1860.73   287.6 1866.34
   323.3 1857.65     387 1823.59   422.2 1812.09   491.2 1815.74     524 1806.45
   599.5 1811.23   711.2 1808.98   747.3 1814.55  775.261811.526   881.5 1807.04
   904.9 1803.92  1108.2 1806.97  1128.2 1822.07  1161.1 1827.56 1252.131892.612
  1279.3 1912.63  1292.4 1930.26  1358.1 1995.86  1387.6 2016.38    1519  1995.9
  1653.6 1988.69  1722.6 1972.76    1785 2004.85    1831 2021.41  1881.8 2052.61
#Mann= 6 ,-1 , 0
       0      .1       0  252.17      .1       0  775.26      .1       0
   881.5     .04       0  1108.2      .1       0 1252.13      .1       0
Bank Sta=881.5,1108.2
XS Rating Curve= 0 ,0
Exp/Cntr=0.3,0.1

Type RM Length L Ch R = 1 ,77413   ,1286.2,1363.5,1395
XS GIS Cut Line= 2
2165727.22575596334479.1490915252164154.64030402333465.705133613
#Sta/Elev= 30
       0 1906.15    35.5 1898.27   111.6 1874.47  287.671853.532  291.041853.148
   558.5 1828.34   601.5 1815.66   628.8 1799.95   668.8  1799.3   699.1 1800.15
   726.4 1805.76   738.1 1811.76   777.1 1811.22     796 1804.83     870 1801.25
    1086 1801.39    1105 1811.11  1120.6 1820.36  1145.3 1821.91 1202.991870.646
  1250.3 1907.23  1285.3 1944.77    1323 1973.11  1412.4 2050.41  1456.3 2081.42
  1559.2 2143.62  1620.2 2190.65  1690.4 2250.06  1772.4 2296.51  1870.9 2324.65
#Mann= 6 ,-1 , 0
       0      .1       0  287.67      .1       0  291.04      .1       0
   777.1     .04       0    1105      .1       0 1202.99      .1       0
Bank Sta=777.1,1105
XS Rating Curve= 0 ,0
Exp/Cntr=0.3,0.1

Type RM Length L Ch R = 1 ,76050   ,1778.8,1609.7,1438.7
XS GIS Cut Line= 3
2166586.90580301333846.620276415 2165657.3330692332871.617296216
2165059.75059747332878.606564892
#Sta/Elev= 30
       0 2050.47    73.7 2028.89      91 2018.78     110 2018.82   186.1 1983.25
   265.8 1939.89   368.4 1872.68   442.6 1832.62   530.9 1815.44   595.9 1811.31
   646.9 1803.62   672.4 1796.69     865 1796.64   882.3 1802.64  954.881817.759
   962.5 1819.87  1063.6 1887.78  1157.4 1942.01  1179.8 1953.95  1222.5 1968.68
  1303.4 1982.05  1421.9 1989.69  1517.3 1988.78  1619.81978.079  1638.5 1976.43
  1681.1 1959.28 1702.261956.236  1736.9 1948.52  1773.1 1958.28  1944.7    2033
#Mann= 6 ,-1 , 0
       0      .1       0   646.9     .04       0   882.3      .1       0
  954.88      .1       0  1619.8     .06       0 1702.26      .1       0
Bank Sta=646.9,882.3
XS Rating Curve= 0 ,0
Exp/Cntr=0.3,0.1

Type RM Length L Ch R = 1 ,74440   ,1534,1432.1,1326.8
XS GIS Cut Line= 2
2166422.65798914331554.1401509312165024.80425409332640.971429933
#Sta/Elev= 30
       0 2170.47    5.12 2173.34    37.8 2188.26    58.9 2183.58    91.5 2163.47
   138.4 2127.15   154.7 2098.86   159.4 2093.51  183.462091.301   278.7 2005.01
   364.1    1937   407.2 1897.84  455.761857.987   503.1 1817.43   525.2 1802.67
   556.5 1795.07   704.2 1795.07   753.3 1798.91  760.661799.646   814.8 1805.74
  925.521809.604  961.731816.038  1000.1 1819.19  1059.5 1842.82  1092.3 1852.69
    1272 1867.65  1300.4 1873.62  1379.8  1907.1  1561.4 1956.11  1770.6  2021.8
#Mann= 9 ,-1 , 0
       0      .1       0    5.12     .06       0  183.46      .1       0
  455.76      .1       0   525.2     .04       0   753.3      .1       0
  760.66      .1       0  925.52     .06       0  961.73      .1       0
Bank Sta=525.2,753.3
XS Rating Curve= 0 ,0
Exp/Cntr=0.3,0.1

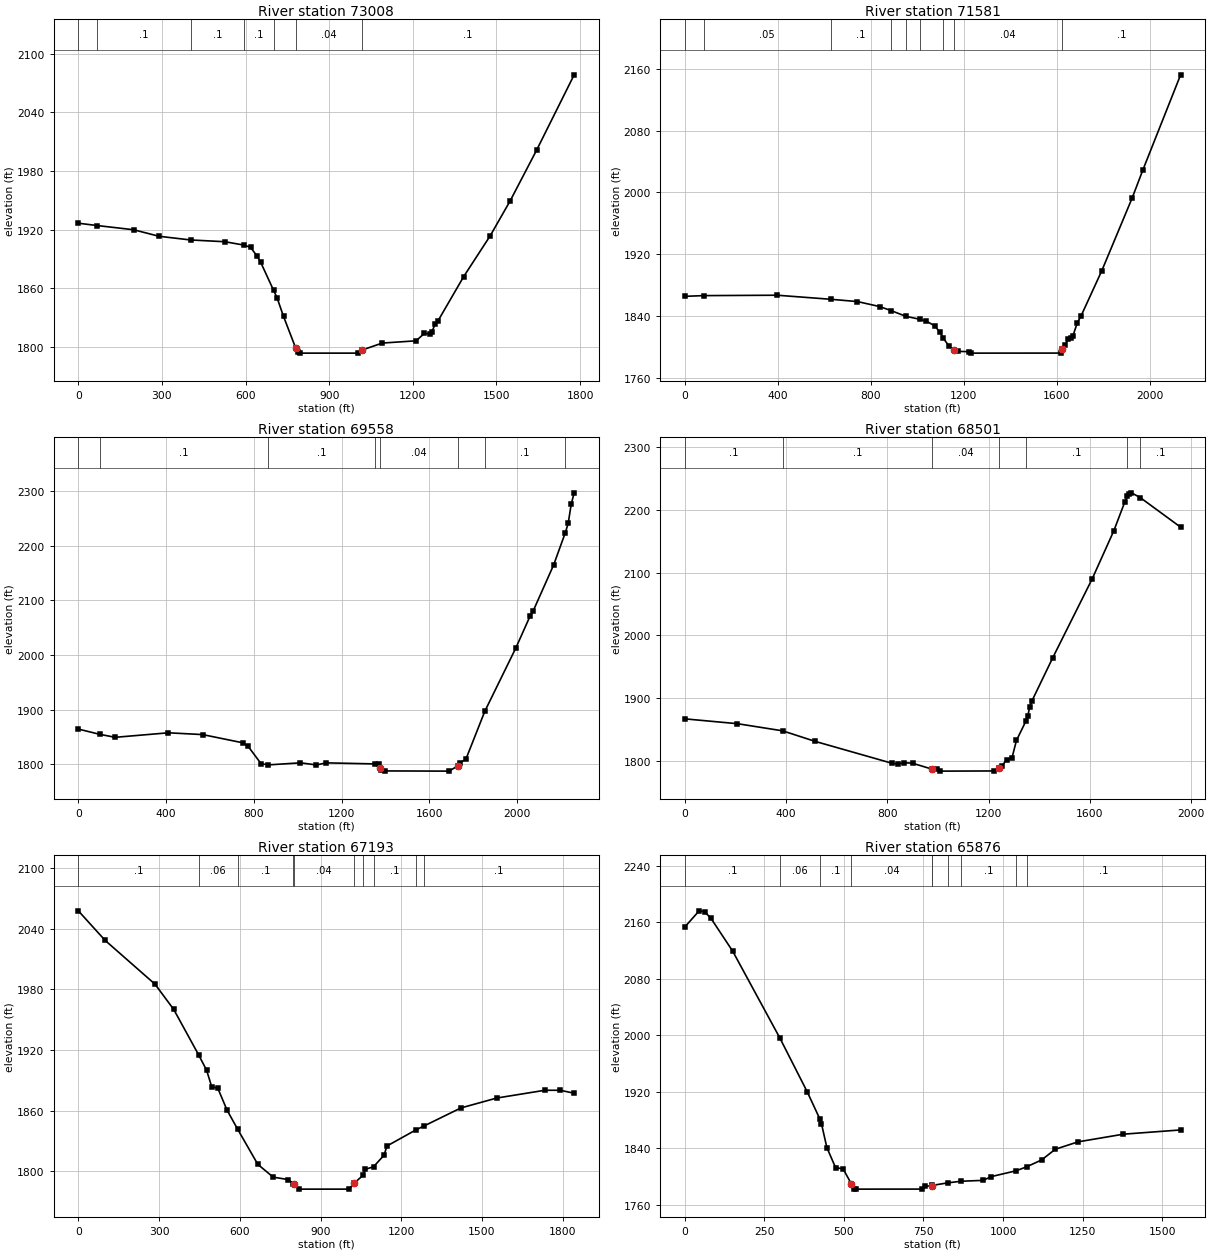
Type RM Length L Ch R = 1 ,73008   ,1410.5,1426.8,1462.1
XS GIS Cut Line= 2
2164546.03934984330736.3957159262164556.52325285332515.164593778
#Sta/Elev= 30
       0 1926.44   67.57 1924.06     198 1919.77   289.9 1913.06  402.971909.305
   526.1  1907.5  594.671904.031     618 1901.75     641 1892.87   654.1 1886.54
  700.641857.678   713.1 1850.03   736.1 1831.11   779.6 1798.92   788.6 1794.36
   795.2 1793.56  1005.1 1793.56  1017.9 1796.73  1090.5 1803.85  1211.8 1806.16
  1241.4 1813.76    1261 1813.33  1267.6 1814.86  1280.7 1823.66  1290.6  1826.7
  1382.4 1871.81  1477.6 1913.58  1549.8 1949.62  1644.9 2001.64  1778.8 2078.22
#Mann= 7 ,-1 , 0
       0     .06       0   67.57      .1       0  402.97      .1       0
  594.67      .1       0  700.64      .1       0   779.6     .04       0
  1017.9      .1       0
Bank Sta=779.6,1017.9
XS Rating Curve= 0 ,0
Exp/Cntr=0.3,0.1

Type RM Length L Ch R = 1 ,71581   ,1636.4,2023.4,2393.8
XS GIS Cut Line= 3
2163817.90226171330705.4508415992163153.92173756331392.728927999
2163122.85832123332569.255821667
#Sta/Elev= 30
       0 1865.31   81.731866.217   397.3 1866.73  626.981861.497   742.6 1858.51
   838.4 1852.02  887.431846.793  949.881839.514 1012.911835.413  1038.7 1833.19
  1074.8 1827.09  1097.8 1818.57 1112.041811.036  1137.1 1800.46  1157.3 1796.36
  1173.2 1794.03  1222.5 1793.65  1232.3 1791.75  1616.3 1791.81  1624.2 1796.56
    1636 1801.95  1649.1 1810.17  1662.5 1811.05  1668.8 1813.59  1688.5 1831.29
  1704.9 1840.26  1793.6  1898.5    1925 1993.27  1970.8 2029.39  2132.6 2152.12
#Mann= 9 ,-1 , 0
       0      .1       0   81.73     .05       0  626.98      .1       0
  887.43      .1       0  949.88     .12       0 1012.91      .1       0
 1112.04      .1       0  1157.3     .04       0  1624.2      .1       0
Bank Sta=1157.3,1624.2
XS Rating Curve= 0 ,0
Exp/Cntr=0.3,0.1

Type RM Length L Ch R = 1 ,69558   ,983.4,1056.6,1117.2
XS GIS Cut Line= 3
2163546.09736879330573.4313221782163091.79490489330884.065485522
2161468.73140142330344.338626711
#Sta/Elev= 30
       0 1864.64   97.951855.021   168.1 1849.58   410.5 1857.83     567 1854.56
   748.8 1839.64   774.5 1832.91   833.2 1801.43  866.411799.197    1013    1803
  1085.6 1799.12  1130.6 1802.93 1352.541800.984  1369.1 1800.33  1375.3 1793.67
  1379.5 1789.86  1396.8 1788.18  1690.4 1787.81  1729.5 1797.17  1739.1 1803.07
  1766.8 1809.23 1853.371897.097    1995 2012.89  2060.6 2071.75  2074.2  2080.7
  2167.4 2164.64 2220.232223.161  2233.5 2240.22  2247.3 2275.27  2260.8 2296.24
#Mann= 8 ,-1 , 0
       0      .1       0   97.95      .1       0  866.41      .1       0
 1352.54     .12       0  1375.3     .04       0  1729.5      .1       0
 1853.37      .1       0 2220.23      .1       0
Bank Sta=1375.3,1729.5
XS Rating Curve= 0 ,0
Exp/Cntr=0.3,0.1

Type RM Length L Ch R = 1 ,68501   ,1315.3,1307.9,1276.1
XS GIS Cut Line= 3
2163681.99981525330340.4556996692163289.82418403 330192.90447208
2162121.06314444329191.109295294
#Sta/Elev= 30
       0 1867.38     208 1859.68  386.331848.333   514.7 1831.57   817.2 1796.88
   840.5 1795.45   866.1 1797.62   899.4 1796.81   977.8 1787.26   994.5 1786.97
  1007.5 1784.24  1222.1 1784.52  1240.8 1788.67  1252.4 1792.05  1270.9 1802.61
  1292.7 1805.84  1309.9 1832.98 1346.731863.386  1354.8 1871.71  1361.7  1885.5
  1371.7 1896.41  1452.5 1963.92  1608.4 2089.46  1694.5 2166.47  1737.7 2212.17
 1748.51 2221.27    1755 2224.95  1764.3 2226.89 1799.062219.289  1958.4 2172.27
#Mann= 7 ,-1 , 0
       0      .1       0  386.33      .1       0   977.8     .04       0
  1240.8      .1       0 1346.73      .1       0 1748.51      .1       0
 1799.06      .1       0
Bank Sta=977.8,1240.8
XS Rating Curve= 0 ,0
Exp/Cntr=0.3,0.1

Type RM Length L Ch R = 1 ,67193   ,1393.6,1317.2,1207.8
XS GIS Cut Line= 2
2164447.58993911329300.0490846712162861.02594982328363.487082187
#Sta/Elev= 30
       0 2057.77    99.3  2028.6   284.9 1985.23   354.6  1960.2   446.71915.463
   476.6 1900.16   495.5  1883.9   518.4 1882.24   552.7 1860.61  591.771841.905
     667 1807.03   724.1 1794.42   780.8 1791.95  799.121787.692   800.3 1787.32
   819.4 1782.56    1006 1782.56  1025.1  1788.5 1057.581796.159    1067  1802.2
  1096.91804.692  1135.6 1815.99    1147 1825.24 1255.031841.232 1283.161844.826
  1421.3 1862.82  1554.7 1872.64  1733.7 1880.33  1790.9  1880.3  1842.4  1877.4
#Mann= 10 ,-1 , 0
       0      .1       0   446.7     .06       0  591.77      .1       0
  799.12      .1       0   800.3     .04       0  1025.1      .1       0
 1057.58      .1       0  1096.9      .1       0 1255.03      .1       0
 1283.16      .1       0
Bank Sta=800.3,1025.1
XS Rating Curve= 0 ,0
Exp/Cntr=0.3,0.1

Type RM Length L Ch R = 1 ,65876   ,243.7,246.5,249
XS GIS Cut Line= 2
2164238.24443263327438.0578899072162735.29217192327848.998947805
#Sta/Elev= 30
       0 2153.33    45.1 2176.26    62.1 2175.11    82.5 2165.43   150.5 2119.07
     299 1995.78   385.2  1919.3   424.6 1881.03   429.4 1874.76   446.4 1840.77
   473.7 1812.41   497.5  1810.5   523.8 1789.04   531.5 1782.31   538.3 1781.84
   745.1 1781.89   755.8 1785.64   775.8 1786.96   776.4 1787.04   827.9 1790.82
   867.9 1793.02   937.4 1794.25   963.4 1799.61  1041.6  1807.9  1074.6 1813.53
  1121.7 1823.31  1164.1 1838.33  1235.5 1848.82  1378.4 1859.72  1558.1 1865.72
#Mann= 10 ,-1 , 0
       0      .1       0     299     .06       0   424.6      .1       0
   523.8     .04       0   775.8      .1       0   776.4      .1       0
   827.9      .1       0   867.9      .1       0  1041.6      .1       0
  1074.6      .1       0
Bank Sta=523.8,775.8
XS Rating Curve= 0 ,0
Exp/Cntr=0.5,0.3

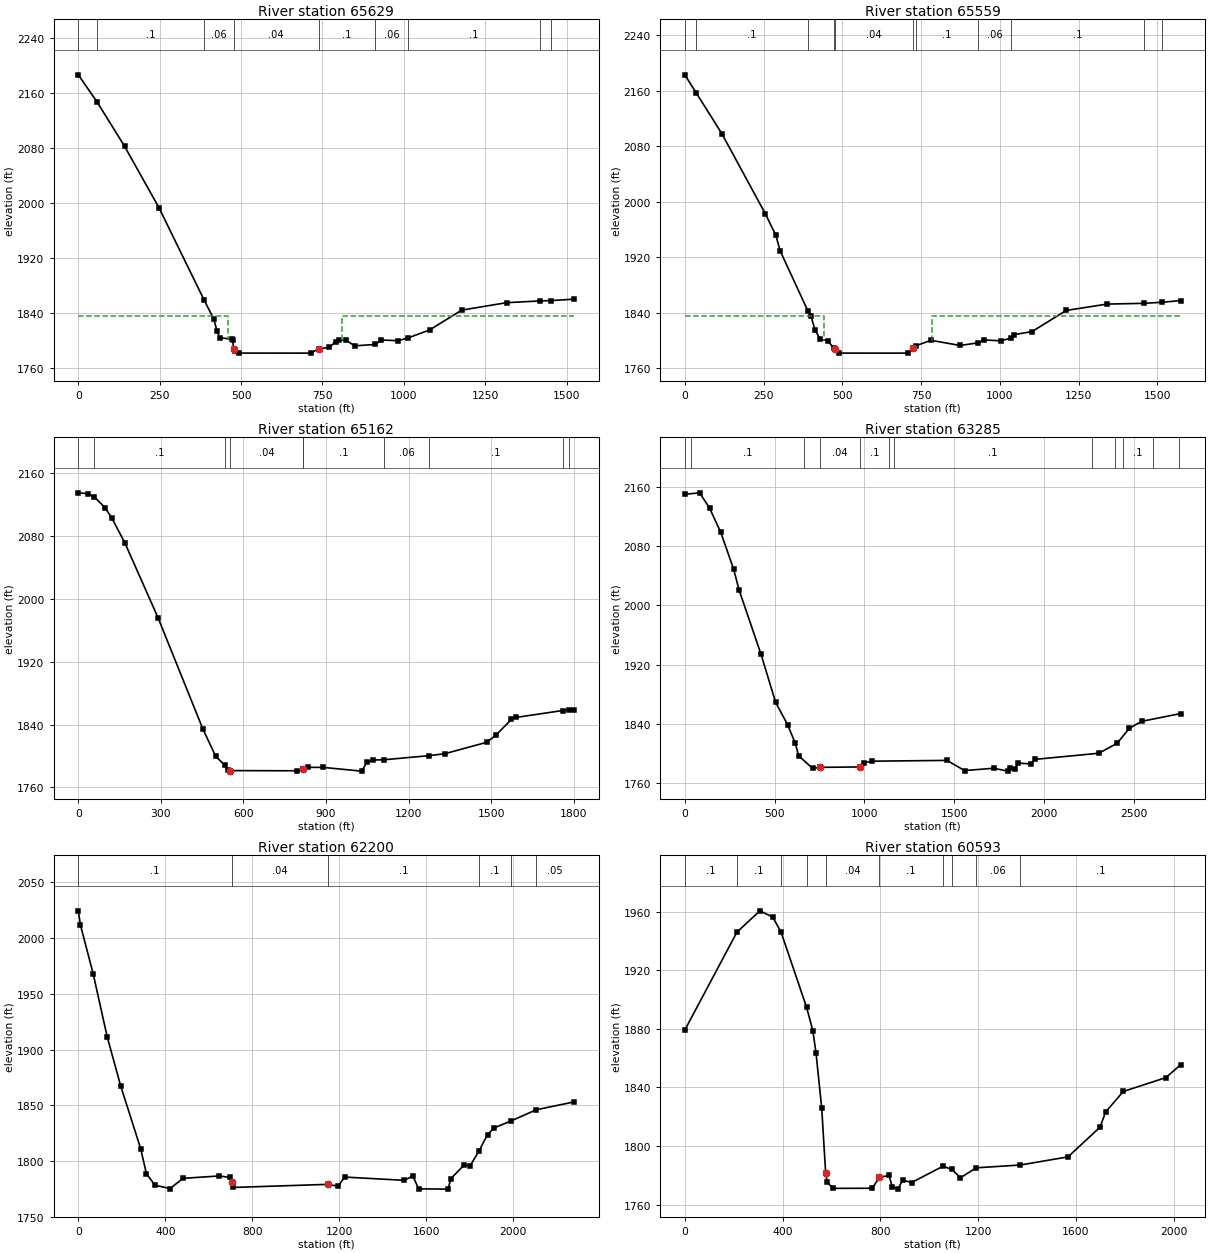
Type RM Length L Ch R = 1 ,65629   ,67.3,70.1,73.8
XS GIS Cut Line= 2
2164119.07970581327227.3239974292162642.60178512327602.461128073
#Sta/Elev= 30
       0 2186.42    57.3 2147.13     142 2082.58     248 1992.93   385.7  1859.6
   416.2 1831.14   426.3 1813.45   434.2 1804.25     472 1801.79   473.7 1800.91
   477.4  1788.2   480.5 1785.24     494 1781.75     714 1781.69   738.4 1787.92
   771.6 1790.06   790.5 1798.31   802.1 1800.57   822.4 1800.44   849.4 1792.31
     912 1794.27   930.7 1800.77   981.5 1799.79  1011.6 1803.54  1079.3  1815.4
  1177.8 1844.23  1316.6 1855.11  1419.4 1857.59  1451.2 1858.07  1523.4 1860.14
#Mann= 9 ,-1 , 0
       0      .1       0    57.3      .1       0   385.7     .06       0
   477.4     .04       0   738.4      .1       0     912     .06       0
  1011.6      .1       0  1419.4      .1       0  1451.2     .06       0
#XS Ineff= 2 , 0
          459.27    1835  810.19            1835
Permanent Ineff=
       F       F
Bank Sta=477.4,738.4
XS Rating Curve= 0 ,0
Exp/Cntr=0.5,0.3

Type RM Length L Ch R = 1 ,65559   ,424.6,397.3,368.9
XS GIS Cut Line= 2
2164093.06815276327181.2657368772162556.43165702327520.645576427
#Sta/Elev= 30
       0 2182.79      37 2156.21   117.6    2098   255.4 1982.74     289 1951.58
   302.4 1929.34   390.7  1842.5   399.9 1835.55   413.3 1815.52   429.3 1801.85
   453.6 1799.57   473.3 1788.61   476.6 1787.45   490.6 1781.69     709 1781.66
   723.7 1789.02   732.5 1792.18   781.5 1800.13   873.6 1792.71   931.6  1796.5
   950.9 1800.68  1003.5 1799.36  1033.9 1803.21  1045.7 1808.31  1102.1 1812.73
  1210.8 1843.22  1340.6 1852.36  1458.5 1853.43  1515.3    1855  1573.7 1857.41
#Mann= 11 ,-1 , 0
       0      .1       0      37      .1       0   390.7     .06       0
   473.3      .1       0   476.6     .04       0   723.7      .1       0
   732.5      .1       0   931.6     .06       0  1033.9      .1       0
  1458.5      .1       0  1515.3     .06       0
#XS Ineff= 2 , 0
           440.3    1835  785.41            1835
Permanent Ineff=
       F       F
Bank Sta=476.6,723.7
XS Rating Curve= 0 ,0
Exp/Cntr=0.5,0.3

Type RM Length L Ch R = 1 ,65162   ,1885.6,1746.1,1602.2
XS GIS Cut Line= 2
2163993.97876884326647.7866247182162361.70939202327409.320752991
#Sta/Elev= 30
       0 2135.33    35.5 2134.26    57.2 2130.41    97.5  2116.2   121.9 2103.05
   169.5 2071.23   289.8 1976.02   451.8 1835.05   498.9 1799.74   531.7 1788.36
   542.3 1782.56   551.4 1781.52   795.8 1781.28   816.4 1783.02   817.5  1783.2
   832.8 1785.65     889 1785.61  1028.7 1780.84  1049.2  1792.3  1070.9 1794.96
  1110.7 1795.35  1274.7 1800.55  1331.6 1803.04  1483.6 1817.57  1516.7 1826.63
  1573.4 1846.74  1588.6 1849.15  1759.3 1858.03  1780.8 1859.11  1801.2 1859.31
#Mann= 10 ,-1 , 0
       0      .1       0    57.2      .1       0   531.7     .06       0
   551.4     .04       0   816.4      .1       0   817.5      .1       0
  1110.7     .06       0  1274.7      .1       0  1759.3      .1       0
  1780.8     .06       0
Bank Sta=551.4,816.4
XS Rating Curve= 0 ,0
Exp/Cntr=0.3,0.1

Type RM Length L Ch R = 1 ,63285   ,1139.1,1084.5,1030.8
XS GIS Cut Line= 2
2162801.61414855324630.4013443972162132.31159935327307.611541226
#Sta/Elev= 30
       0 2149.54    82.8 2151.51   137.6 2131.01   199.8 2098.51   272.1 2048.42
   302.6  2020.2   424.4 1933.87   505.5 1869.22   573.2 1838.59   613.8 1814.61
     634 1797.16   711.8 1780.17   752.4 1781.65   975.5 1782.18   995.8 1787.96
  1043.2 1789.97  1459.1 1791.02  1557.2 1777.32  1719.5 1780.45  1797.3 1776.56
  1807.5 1781.23  1837.9 1779.61  1854.8 1787.42  1925.9 1786.25  1949.5  1792.4
  2304.6 1800.65  2406.1 1814.06  2473.7 1834.19  2542.7 1843.63  2759.6 1854.12
#Mann= 12 ,-1 , 0
       0      .1       0   35.27      .1       0  662.28      .1       0
   752.4     .04       0   975.5      .1       0 1138.58     .12       0
 1165.41      .1       0 2266.24     .06       0 2396.62      .1       0
 2438.52      .1       0 2606.15     .06       0 2749.14      .1       0
Bank Sta=752.4,975.5
XS Rating Curve= 0 ,0
Exp/Cntr=0.3,0.1

Type RM Length L Ch R = 1 ,62200   ,1482.3,1607.3,1623.4
XS GIS Cut Line= 2
 2161432.9646662324671.8713612272161685.24024244326937.203066237
#Sta/Elev= 30
       0 2024.49     9.3 2012.08    68.8 1967.52   132.5 1911.56   194.2 1867.65
   286.6 1810.96     313 1788.58   352.7 1778.15     422 1775.27   481.4 1784.39
   646.5 1786.53   699.3 1785.21     706 1781.18   712.5 1776.23    1148 1779.01
  1194.4 1777.31  1224.2 1785.56  1498.1  1782.6  1537.8 1786.58  1564.2 1774.97
  1699.5 1774.72  1712.7 1784.19  1772.1 1796.09  1801.9 1795.91 1842.261809.079
  1881.1  1823.7  1910.8 1829.62 1990.621836.046  2105.11845.945  2279.3 1853.02
#Mann= 6 ,-1 , 0
       0      .1       0     706     .04       0    1148      .1       0
 1842.26      .1       0 1990.62     .06       0  2105.1     .05       0
Bank Sta=706,1148
XS Rating Curve= 0 ,0
Exp/Cntr=0.3,0.1

Type RM Length L Ch R = 1 ,60593   ,1126.3,1119.4,1114.8
XS GIS Cut Line= 2
2160202.42575211324505.2648307832160146.33902817326533.015619283
#Sta/Elev= 30
       0 1879.05  213.111945.863   307.2 1960.46   359.8 1956.17  393.831945.912
  498.221894.623   523.9 1878.59     537 1863.17     560  1826.1   576.4 1781.19
   582.9 1775.05   605.9 1771.03   766.7 1771.09   796.3 1778.53   835.7 1779.85
   848.7 1771.94   871.8  1770.5   891.5 1776.71   927.6 1774.97 1056.471786.145
 1093.161783.902  1127.8 1778.27 1192.32 1785.05  1372.41786.956  1567.8 1792.51
  1698.8 1812.79  1721.8 1823.19    1794 1837.16    1968 1846.61  2028.5 1855.34
#Mann= 10 ,-1 , 0
       0      .1       0  213.11      .1       0  393.83      .1       0
  498.22     .12       0   576.4     .04       0   796.3      .1       0
 1056.47      .1       0 1093.16      .1       0 1192.32     .06       0
  1372.4      .1       0
Bank Sta=576.4,796.3
XS Rating Curve= 0 ,0
Exp/Cntr=0.3,0.1

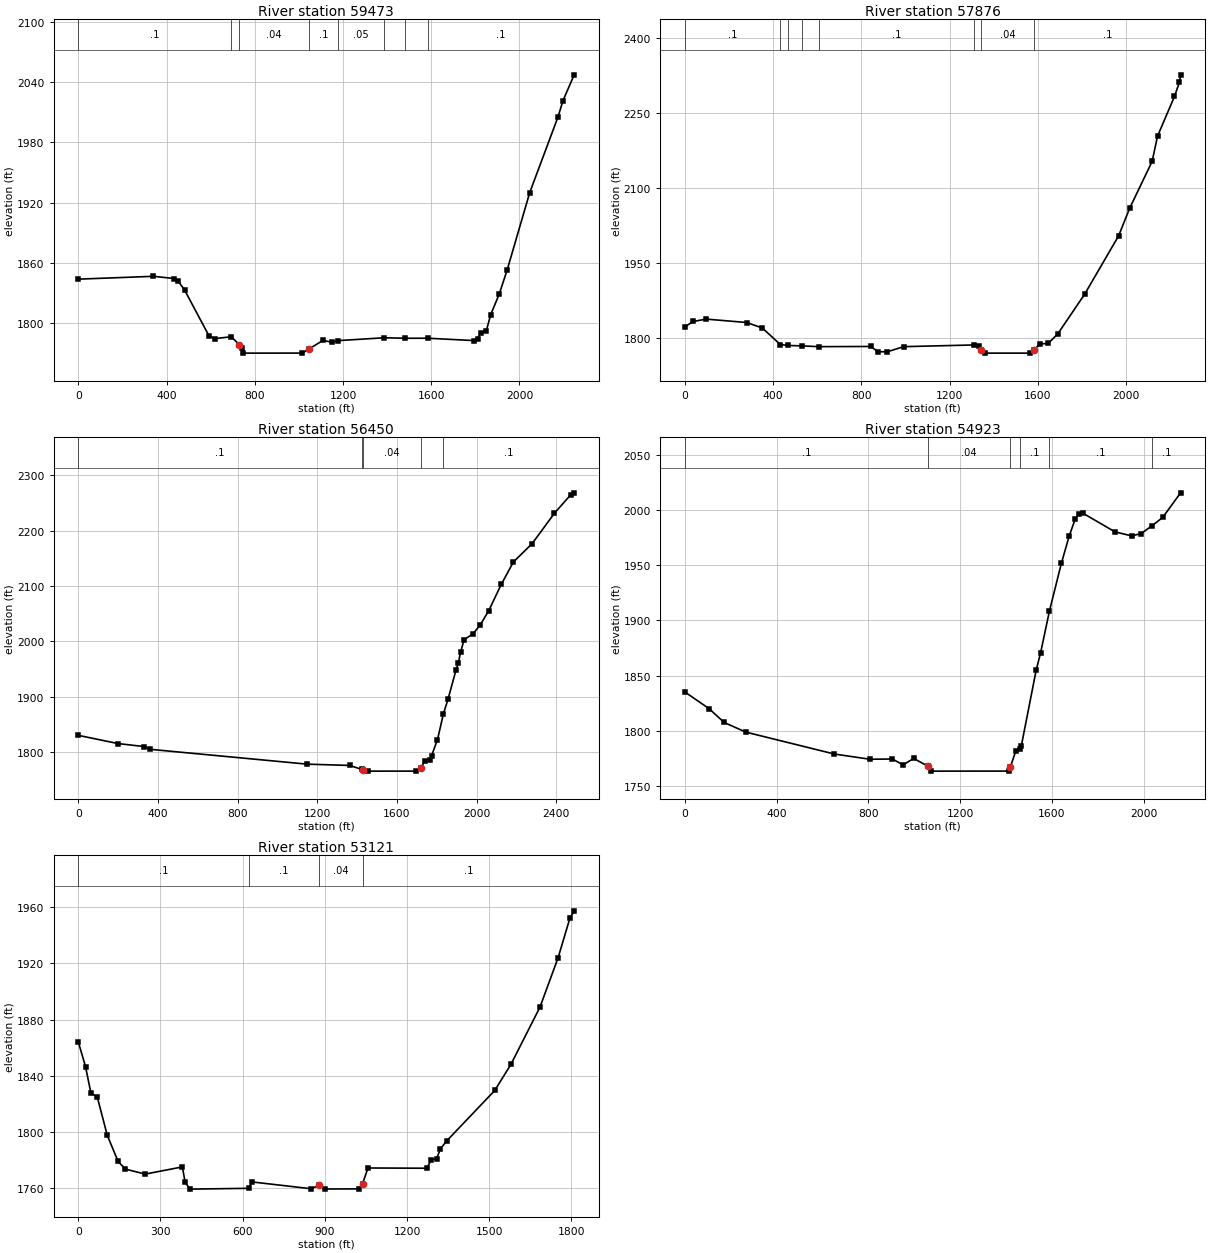
Type RM Length L Ch R = 1 ,59473   ,1437.5,1597.5,1712.3
XS GIS Cut Line= 2
 2159050.4907297324298.1753885532159085.00563674326545.958709423
#Sta/Elev= 30
       0 1843.71   340.4 1846.53   435.5 1844.31   451.9 1841.92   481.5 1832.97
     593 1786.97     619  1784.5  693.541786.311   729.4 1778.54   740.7  1774.7
   747.2 1770.02  1016.3 1770.06  1046.1 1774.16  1108.2  1782.6  1150.8 1780.97
 1175.82 1782.45 1387.441785.332 1482.651784.819 1585.281784.863    1794 1782.52
  1810.4 1784.11  1823.5 1790.02  1849.7 1792.19  1869.4 1808.19  1908.8 1829.16
  1944.5 1853.03  2046.6 1929.97  2174.6 2005.19  2197.5 2021.57    2248 2047.22
#Mann= 8 ,-1 , 0
       0      .1       0  693.54      .1       0   729.4     .04       0
  1046.1      .1       0 1175.82     .05       0 1387.44     .06       0
 1482.65     .05       0 1585.28      .1       0
Bank Sta=729.4,1046.1
XS Rating Curve= 0 ,0
Exp/Cntr=0.3,0.1

Type RM Length L Ch R = 1 ,57876   ,1302.1,1426,1537.3
XS GIS Cut Line= 2
2159038.90518897324015.5732698472157117.21927698325179.480974274
#Sta/Elev= 30
       0  1821.4    37.2 1832.22    97.8 1836.97   280.4 1830.19     351 1819.28
  432.891786.172  467.531784.292  530.741783.411  607.041781.897   841.9 1782.25
   876.4 1771.72   917.5 1771.62   991.5 1781.88 1310.02 1785.28  1332.9 1783.62
  1344.4 1775.86  1362.5 1768.94    1563 1768.94  1582.2 1775.45  1608.6 1786.98
  1647.4 1788.68  1689.8 1807.37  1811.6 1886.65  1965.8 2003.62  2015.6 2058.64
  2117.4 2152.34  2142.2 2203.06  2218.9 2282.49  2241.6 2311.31  2246.7 2325.67
#Mann= 8 ,-1 , 0
       0      .1       0  432.89      .1       0  467.53      .1       0
  530.74      .1       0  607.04      .1       0 1310.02      .1       0
  1344.4     .04       0  1582.2      .1       0
Bank Sta=1344.4,1582.2
XS Rating Curve= 0 ,0
Exp/Cntr=0.3,0.1

Type RM Length L Ch R = 1 ,56450   ,1503.9,1527.4,1549.5
XS GIS Cut Line= 3
2159281.59232734323688.6885528592158776.40685563323782.791728961
2156933.96572351323069.588710078
#Sta/Elev= 30
       0 1830.46   198.5 1815.66     332 1810.16   358.7 1805.31  1149.6 1778.46
  1362.7 1776.15 1422.131769.125  1428.6 1768.64    1454 1765.89  1697.7 1765.91
  1718.8 1770.89  1739.9 1784.53  1764.5 1786.73  1773.6 1793.82  1803.2 1822.65
 1833.391869.854    1856 1895.41  1896.9 1949.22    1908 1960.86  1919.3  1980.6
  1936.9 2002.92  1982.6 2013.87  2017.8 2029.71  2059.7 2054.78  2123.3 2102.69
  2184.4 2143.27  2278.3  2176.3  2390.7  2231.3  2471.6 2264.29  2489.5 2268.05
#Mann= 5 ,-1 , 0
       0      .1       0 1422.13      .1       0  1428.6     .04       0
  1718.8      .1       0 1833.39      .1       0
Bank Sta=1428.6,1718.8
XS Rating Curve= 0 ,0
Exp/Cntr=0.3,0.1

Type RM Length L Ch R = 1 ,54923   ,1826.4,1801.6,1747
XS GIS Cut Line= 2
2159573.80745313322663.4592132142157696.69672982 321593.65468489
#Sta/Elev= 30
       0 1835.22     106 1820.06   171.5 1807.58   266.4 1798.84   651.5 1779.04
   806.4 1774.32   904.5 1774.52   951.4  1769.2   997.1 1775.05  1059.7 1768.01
  1074.5 1763.56  1410.6 1763.59  1418.1 1766.93  1442.1 1781.67 1461.351783.419
  1466.2 1786.12  1531.1 1854.93  1550.4 1870.59 1588.98 1908.49  1640.9 1951.56
  1674.9 1976.26  1701.3 1991.72  1716.3 1996.63  1735.6 1996.87    1875 1980.02
  1947.2 1976.43    1989 1978.57 2036.261985.649  2082.7 1993.18  2160.6  2015.4
#Mann= 6 ,-1 , 0
       0      .1       0  1059.7     .04       0  1418.1      .1       0
 1461.35      .1       0 1588.98      .1       0 2036.26      .1       0
Bank Sta=1059.7,1418.1
XS Rating Curve= 0 ,0
Exp/Cntr=0.3,0.1

Type RM Length L Ch R = 1 ,53121   ,1155,1186.4,1194.7
XS GIS Cut Line= 2
2160132.79826285320638.8352047022158336.06588143320416.099785517
#Sta/Elev= 30
       0 1864.04    26.2 1846.65      46 1827.71    69.1 1825.02   105.5 1797.84
   145.2 1779.16   171.6 1773.72   244.4 1770.18   379.9 1775.29   389.8 1764.53
   407.6 1759.49  622.111760.066   634.5  1764.6   849.4 1759.78   879.4 1762.21
   898.9  1759.6  1024.6 1759.64  1037.8 1763.32  1057.6 1774.52  1272.5 1774.34
    1289 1780.46  1308.3  1781.1  1322.1 1788.13  1345.2 1793.81  1520.5  1829.6
    1580 1848.31  1685.8 1888.92  1751.9 1923.98  1794.9 1952.05  1810.5 1957.31
#Mann= 4 ,-1 , 0
       0      .1       0  622.11      .1       0   879.4     .04       0
  1037.8      .1       0
Bank Sta=879.4,1037.8
XS Rating Curve= 0 ,0
Exp/Cntr=0.3,0.1