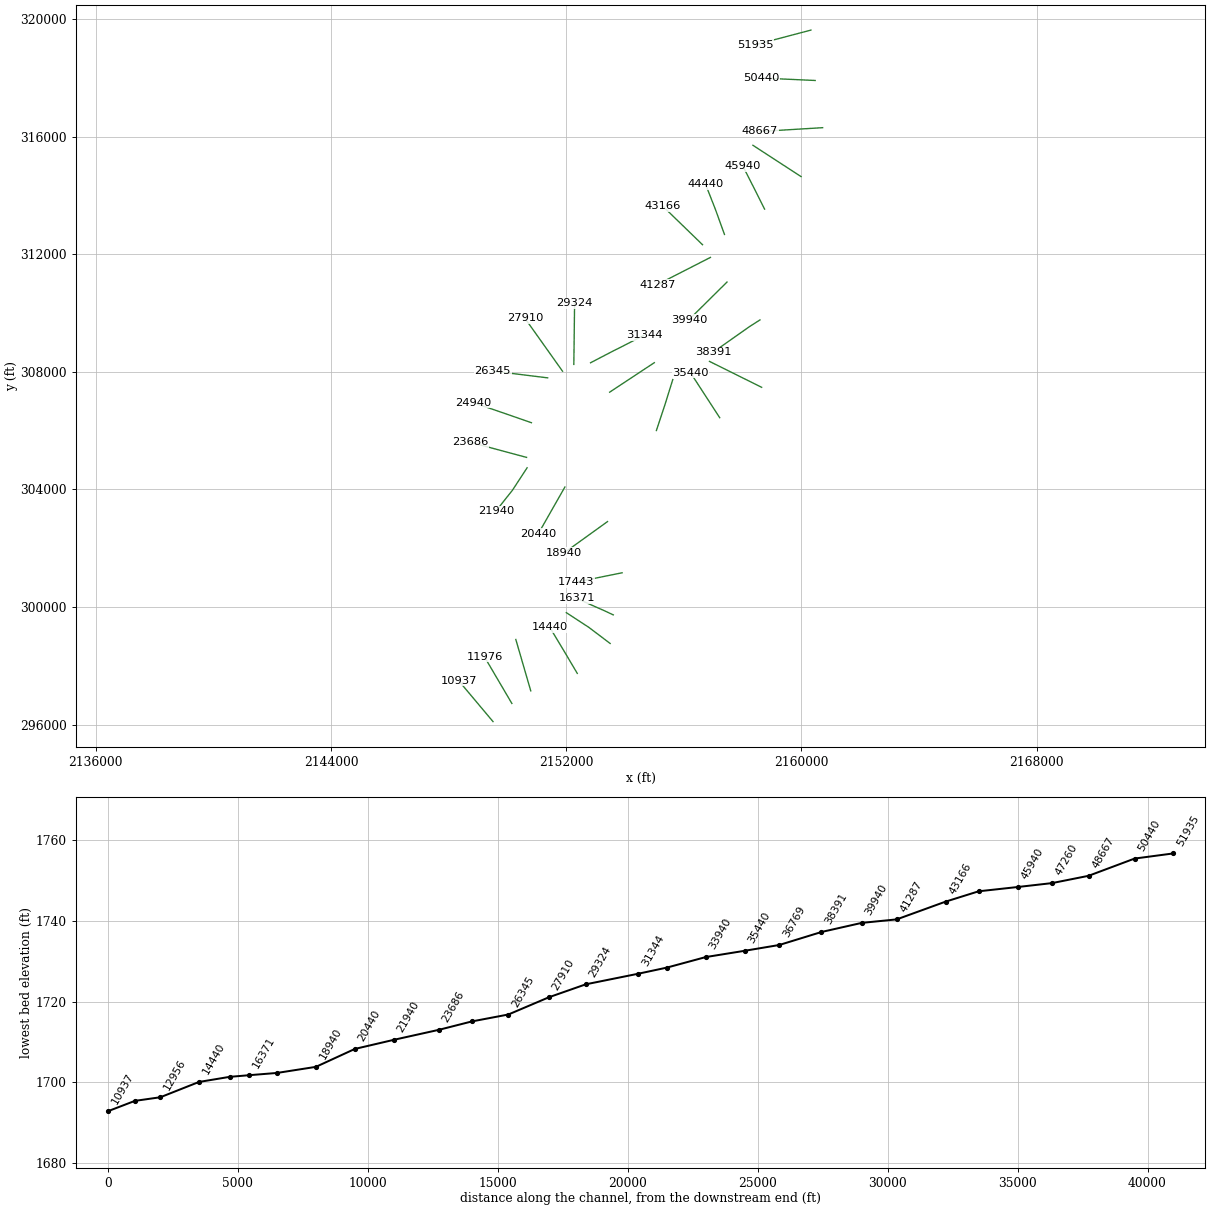
HEC-RAS study GRBRRV5.prj: GRBRRV5

--- GRBRRV5.g01 (geometry) --- (continued)

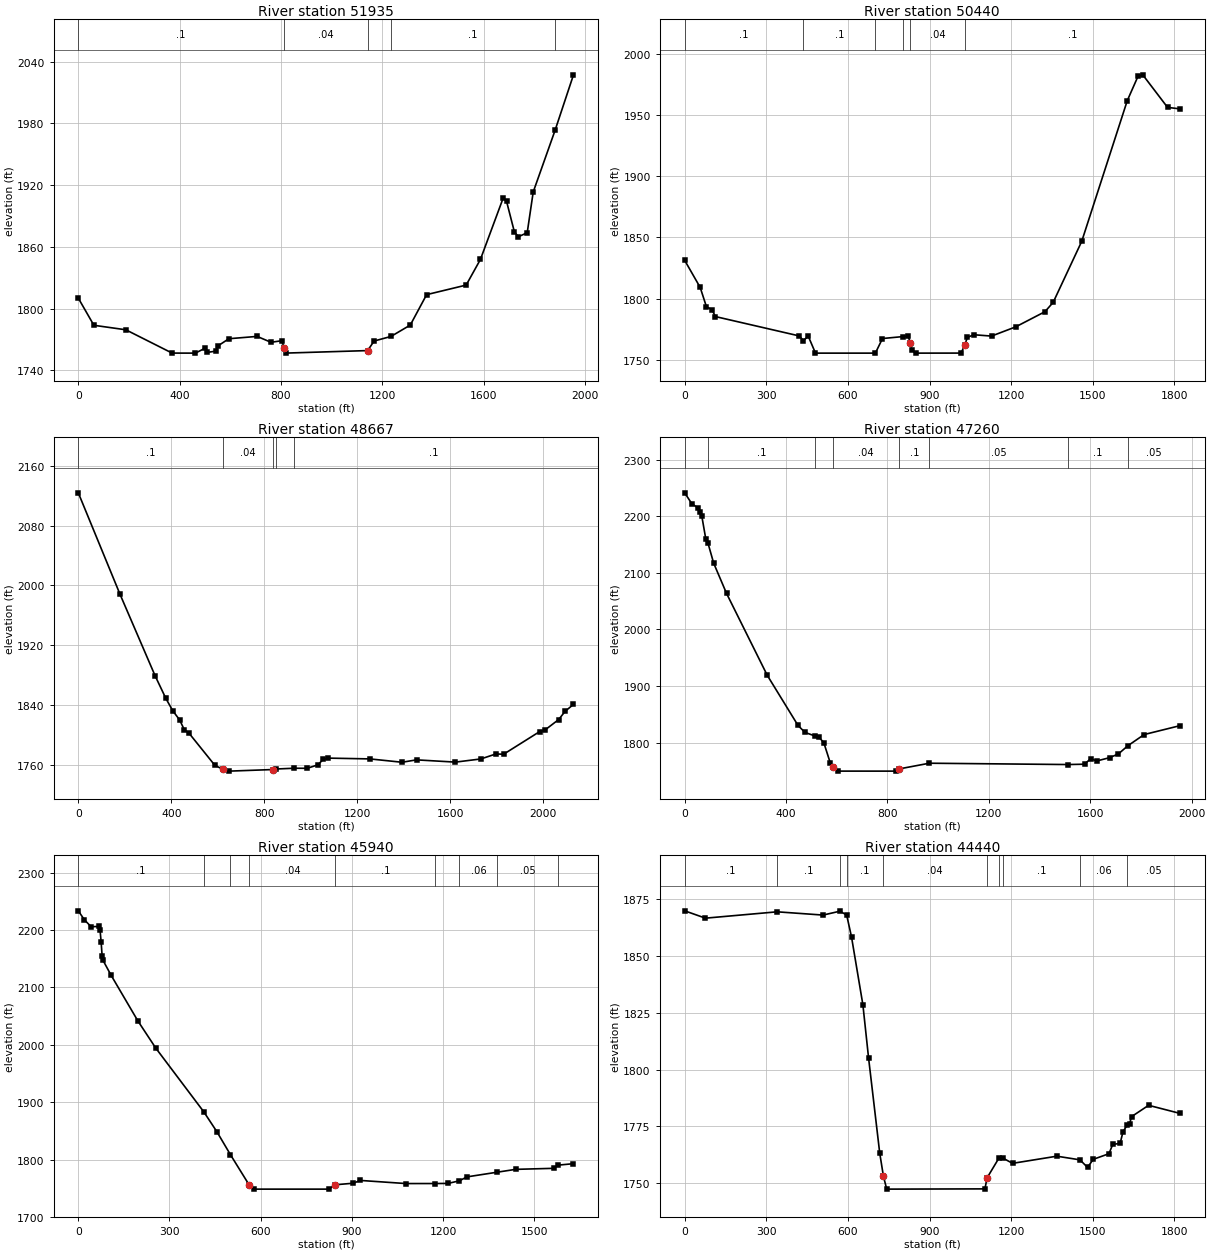
Type RM Length L Ch R = 1 ,51935   ,1530.1,1494.8,1453.7
XS GIS Cut Line= 2
2160323.74221019 319624.403109082158434.20340411319126.329589214
#Sta/Elev= 30
       0  1810.2    61.5 1783.82   187.5 1779.46   370.2 1756.82   461.8 1756.78
   499.2 1761.42   509.3  1757.5   543.3 1758.74     550 1763.63   594.2 1770.77
   705.7 1773.02   760.4 1767.31   804.5 1768.88   811.3 1761.37   818.1 1756.81
  1141.7 1759.25  1167.4 1768.55 1233.641772.957  1310.1 1784.04  1374.5 1813.58
  1530.6 1822.87  1586.9 1847.81  1676.5 1907.31  1690.1 1904.08  1720.9 1874.52
  1736.8 1869.82  1771.5 1873.76  1795.2 1913.31 1881.291973.085  1954.1 2027.09
#Mann= 5 ,-1 , 0
       0      .1       0   811.3     .04       0  1141.7      .1       0
 1233.64      .1       0 1881.29      .1       0
Bank Sta=811.3,1141.7
XS Rating Curve= 0 ,0
Exp/Cntr=0.3,0.1

Type RM Length L Ch R = 1 ,50440   ,1763.4,1772.3,1780.8
XS GIS Cut Line= 3
     2160468.915       317910.97     2159559.854      317952.291
     2158650.792      317993.612
#Sta/Elev= 30
       0 1831.23      57  1809.1      80 1793.31   100.3    1791   112.9 1785.34
   421.6 1769.51  435.871765.739   454.4 1769.21   480.7  1755.5  700.79  1755.5
     727 1767.42  800.781768.972   822.3  1769.1   828.8 1763.47   835.4 1758.09
   848.5  1755.5    1016 1755.53  1029.2 1762.12    1039 1768.26    1062 1770.52
  1127.7 1769.41  1216.4 1776.92    1324  1789.3  1354.3 1796.92  1459.4 1846.81
  1626.7 1961.62  1666.3 1981.55  1683.6 1982.66  1774.7 1956.09    1820 1954.88
#Mann= 6 ,-1 , 0
       0      .1       0  435.87      .1       0  700.79    .055       0
  800.78      .1       0   828.8     .04       0  1029.2      .1       0
Bank Sta=828.8,1029.2
XS Rating Curve= 0 ,0
Exp/Cntr=0.3,0.1

Type RM Length L Ch R = 1 ,48667   ,1464.4,1407,1323.8
XS GIS Cut Line= 2
2160722.47426781316305.5894961352158596.15155379316176.877467441
#Sta/Elev= 30
       0 2124.12     179  1988.5   330.7 1878.77   376.8 1848.55   406.4 1832.09
     436 1819.79   455.7 1806.87   476.6 1801.92   587.2 1759.09   622.2 1753.58
   649.1 1751.22     838 1753.36   851.91754.075  928.161755.099   984.9    1755
  1030.9 1759.69  1053.9 1767.12  1075.9 1768.65  1254.5 1767.59  1392.5 1763.11
  1454.9 1766.31  1622.5 1763.29  1731.8 1767.55  1796.6 1774.24  1829.6 1773.86
  1984.1 1804.08  2007.6 1806.33  2066.3 1820.29  2094.4 1831.43  2130.2 1840.63
#Mann= 5 ,-1 , 0
       0      .1       0   622.2     .04       0     838      .1       0
   851.9     .05       0  928.16      .1       0
Bank Sta=622.2,838
XS Rating Curve= 0 ,0
Exp/Cntr=0.3,0.1

Type RM Length L Ch R = 1 ,47260   ,1396.1,1320.7,1253.7
XS GIS Cut Line= 2
2159989.39093178314640.9772108722158352.07897151315706.489057769
#Sta/Elev= 30
       0 2241.71    28.2 2222.38    51.7 2215.33    60.4  2208.4    67.5 2200.62
      83 2160.71   91.732152.959   114.3  2117.3   165.2 2063.68   325.7 1918.91
     447 1830.29   474.4 1817.93  515.421811.359   529.2 1809.79   548.9  1799.6
   574.9 1763.16   585.4 1757.48   603.6 1749.44   834.6 1749.41   846.3 1753.35
  965.221763.405 1511.371761.053  1577.5 1761.66  1601.8 1771.57  1625.3 1767.34
  1676.2 1773.22  1710.8 1779.77    1748 1794.22  1812.7 1814.14  1953.5 1829.79
#Mann= 8 ,-1 , 0
       0     .12       0   91.73      .1       0  515.42      .1       0
   585.4     .04       0   846.3      .1       0  965.22     .05       0
 1511.37      .1       0    1748     .05       0
Bank Sta=585.4,846.3
XS Rating Curve= 0 ,0
Exp/Cntr=0.3,0.1

Type RM Length L Ch R = 1 ,45940   ,1520.3,1500,1484.1
XS GIS Cut Line= 3
2158747.24924975313537.838821897      2158424.99      314180.655
     2158012.182      314991.636
#Sta/Elev= 30
       0 2233.58    20.1  2217.9    42.2 2205.82    67.9  2206.4    71.5 2200.33
    75.2 2178.75    78.4 2154.63    80.9 2147.64   108.2 2120.97   196.3 2041.39
     255 1994.21   413.11883.006   455.5 1848.88  500.411808.579   562.5  1755.4
   577.1 1748.44   824.2 1748.44   845.8 1756.07   905.2 1758.76   927.3 1763.62
  1078.2 1758.15 1175.09 1758.19  1216.6 1758.43 1253.711762.937  1278.7  1769.8
 1378.551777.988    1439 1782.91  1564.2 1784.71 1577.571790.206  1629.1  1792.8
#Mann= 9 ,-1 , 0
       0      .1       0   413.1     .12       0  500.41      .1       0
   562.5     .04       0   845.8      .1       0 1175.09     .12       0
 1253.71     .06       0 1378.55     .05       0 1577.57     .06       0
Bank Sta=562.5,845.8
XS Rating Curve= 0 ,0
Exp/Cntr=0.3,0.1

Type RM Length L Ch R = 1 ,44440   ,1207.1,1274.1,1327.9
XS GIS Cut Line= 3
     2157383.683      312673.936     2157074.632      313529.766
     2156741.256      314376.978
#Sta/Elev= 30
       0  1869.9    76.4 1866.67  339.771869.466   508.6 1868.03  570.82 1869.74
  595.461868.044   613.3  1858.4   655.1 1828.54     676 1805.12     717 1763.23
   730.7 1752.99   742.7 1747.38  1103.7 1747.49  1111.7 1752.35 1155.291761.068
  1170.91760.975  1205.3 1758.73  1368.1 1761.88 1453.251760.269  1480.9 1756.95
  1502.1 1760.51  1559.5 1762.96  1573.6 1767.04  1600.8 1767.55  1611.4 1772.64
 1625.91 1775.45  1635.4 1776.16  1643.1 1779.32  1705.4 1784.28  1820.4 1780.73
#Mann= 10 ,-1 , 0
       0      .1       0  339.77      .1       0  570.82      .1       0
  595.46      .1       0   730.7     .04       0  1111.7      .1       0
 1155.29      .1       0  1170.9      .1       0 1453.25     .06       0
 1625.91     .05       0
Bank Sta=730.7,1111.7
XS Rating Curve= 0 ,0
Exp/Cntr=0.3,0.1

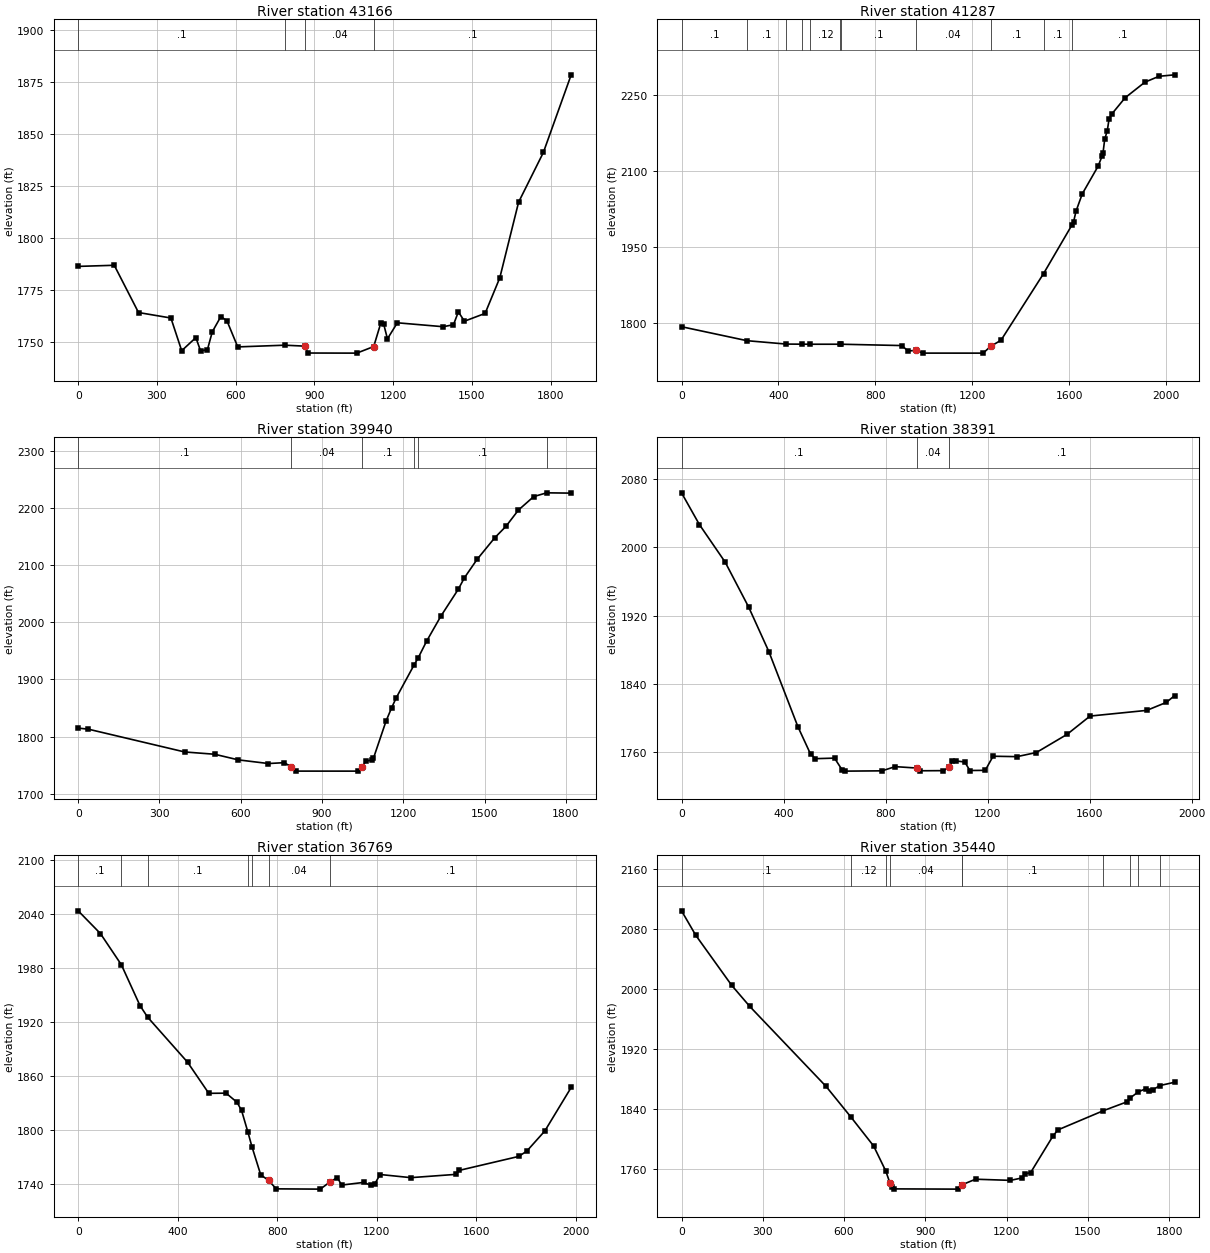
Type RM Length L Ch R = 1 ,43166   ,1674.8,1878.9,2017.4
XS GIS Cut Line= 2
2156636.64359141312325.7632840992155288.06804385313632.935196422
#Sta/Elev= 30
       0 1786.47   137.4 1787.01   229.8 1764.31   353.2 1761.68   394.3 1745.97
   448.3 1752.28   466.3 1745.86   492.4 1746.51   510.9 1755.07   543.4 1762.35
   566.6 1760.37   607.8  1747.8  787.241748.621   864.9 1748.16     874 1744.86
  1061.3 1744.81  1125.8 1747.97  1152.7 1759.18    1164 1758.67  1178.1 1751.68
  1215.9 1759.38  1390.3  1757.5  1429.7 1758.45  1448.3 1764.64  1471.5 1760.15
  1550.2 1763.89  1606.1 1780.96  1677.8 1817.33  1772.1 1841.19  1878.1 1878.49
#Mann= 4 ,-1 , 0
       0      .1       0  787.24      .1       0   864.9     .04       0
  1125.8      .1       0
Bank Sta=864.9,1125.8
XS Rating Curve= 0 ,0
Exp/Cntr=0.3,0.1

Type RM Length L Ch R = 1 ,41287   ,1286.9,1347,1381.8
XS GIS Cut Line= 2
2156907.39418202311893.6825019682155095.94502647310968.008043627
#Sta/Elev= 30
       0 1792.49  270.281764.919  432.461758.247  496.421758.053  531.971757.949
  655.19 1757.97  660.06 1757.95   909.3 1755.32   934.3 1744.62     966 1745.76
   997.7 1740.44  1244.6 1740.41  1275.7 1753.85  1318.3 1765.82 1493.711897.075
 1610.441992.594  1617.7 1999.12  1627.8 2020.22  1653.6 2054.41  1718.6 2108.65
  1736.3 2129.97    1739 2134.47  1746.3 2162.26  1756.8 2178.96  1764.1 2201.73
  1776.3 2212.33  1830.4 2243.86  1912.1 2274.66  1970.4 2286.25  2034.3 2289.13
#Mann= 11 ,-1 , 0
       0      .1       0  270.28      .1       0  432.46      .1       0
  496.42      .1       0  531.97     .12       0  655.19      .1       0
  660.06      .1       0     966     .04       0  1275.7      .1       0
 1493.71      .1       0 1610.44      .1       0
Bank Sta=966,1275.7
XS Rating Curve= 0 ,0
Exp/Cntr=0.3,0.1

Type RM Length L Ch R = 1 ,39940   ,1560.4,1548.7,1526.7
XS GIS Cut Line= 3
     2157469.486      311054.988     2156822.682      310414.875
     2156175.878      309774.761
#Sta/Elev= 30
       0  1814.8    37.6  1812.9     393 1773.06   503.8 1769.06   591.1 1759.23
   702.2 1752.82   760.6 1754.32     787 1746.93   804.7 1739.58  1034.6 1739.54
  1048.3 1747.11  1062.2    1757  1083.1 1758.98    1090 1762.05  1136.8 1827.42
  1157.4  1850.6  1174.1 1867.77 1240.361925.502 1255.641938.028  1286.1 1966.68
  1339.2 2010.79  1402.7 2057.21    1426 2077.78  1472.6 2109.84  1537.9 2147.69
  1579.3 2167.68  1625.4 2196.19  1681.7 2219.69 1729.622226.253    1820 2225.72
#Mann= 6 ,-1 , 0
       0      .1       0     787     .04       0  1048.3      .1       0
 1240.36      .1       0 1255.64      .1       0 1729.62    .055       0
Bank Sta=787,1048.3
XS Rating Curve= 0 ,0
Exp/Cntr=0.3,0.1

Type RM Length L Ch R = 1 ,38391   ,1700,1622,1506.7
XS GIS Cut Line= 3
2158591.00307264309767.0184384942158235.75787345309540.485267993
2157000.12239799308670.391954023
#Sta/Elev= 30
       0 2064.15    69.9 2026.92   171.1 1982.73   263.4  1929.8   342.5 1877.55
   456.2 1789.43   505.6 1757.39   524.5  1751.9   599.8 1752.56   630.4 1738.29
   640.8 1737.28   785.8 1737.62   837.6 1742.56   921.7  1740.9   934.2 1737.69
    1026 1737.85  1050.1 1741.73  1062.1 1749.24  1077.3 1749.23  1110.3 1747.98
  1130.3    1738  1190.5  1738.2  1221.4 1754.78  1314.9 1754.29    1391 1759.13
  1511.1 1780.41  1601.5 1801.95  1823.8 1808.63  1900.8 1818.05  1932.6 1825.91
#Mann= 3 , 0 , 0
       0      .1       0   921.7     .04       0  1050.1      .1       0
Bank Sta=921.7,1050.1
XS Rating Curve= 0 ,0
Exp/Cntr=0.3,0.1

Type RM Length L Ch R = 1 ,36769   ,1379.5,1329.3,1252.1
XS GIS Cut Line= 2
2158647.67730267307475.6231569272156873.23579273308356.929106864
#Sta/Elev= 30
       0 2043.74    89.4 2018.42  173.521983.717   248.4 1938.28  279.441925.264
   439.4 1875.34   524.8 1840.67   594.4 1840.84   638.3  1830.7   656.6 1821.56
   681.51798.006  698.321781.229   733.6 1749.94   764.9 1743.85   795.8 1734.37
   972.9 1734.06  1011.6 1741.98  1041.5 1746.93  1058.6 1738.56  1146.7 1741.52
  1176.8 1738.25  1191.5 1739.65  1213.4 1750.33  1336.9 1746.83  1517.5 1750.47
  1532.1 1754.96  1770.2 1770.45  1802.7 1776.33  1875.3 1798.78  1981.2  1847.2
#Mann= 7 ,-1 , 0
       0      .1       0  173.52      .1       0  279.44      .1       0
   681.5      .1       0  698.32      .1       0   764.9     .04       0
  1011.6      .1       0
Bank Sta=764.9,1011.6
XS Rating Curve= 0 ,0
Exp/Cntr=0.3,0.1

Type RM Length L Ch R = 1 ,35440   ,1603.8,1500,1402.1
XS GIS Cut Line= 3
     2157221.744      306441.596     2156726.153      307204.806
     2156230.562      307968.016
#Sta/Elev= 30
       0 2104.34    52.5 2071.69   185.5 2004.65     252 1976.61   533.8 1869.73
  625.581828.786   709.3 1790.17  754.161756.695   768.8  1741.3   776.2 1734.84
     784 1732.94  1018.8 1732.62  1034.2 1738.23 1036.141738.528  1085.3 1745.86
  1214.4 1744.32  1257.2  1747.6  1269.1 1753.11  1288.7 1754.65  1370.8  1803.3
  1389.3  1811.7 1557.391837.399  1644.7 1849.23  1655.71854.254 1686.57  1862.6
  1715.1 1866.91  1726.7  1863.8  1738.7 1864.89  1765.3 1870.89    1820 1875.36
#Mann= 10 ,-1 , 0
       0      .1       0  625.58     .12       0  754.16      .1       0
   768.8     .04       0  1034.2      .1       0 1036.14      .1       0
 1557.39     .06       0  1655.7      .1       0 1686.57     .06       0
  1765.3      .1       0
Bank Sta=768.8,1034.2
XS Rating Curve= 0 ,0
Exp/Cntr=0.3,0.1

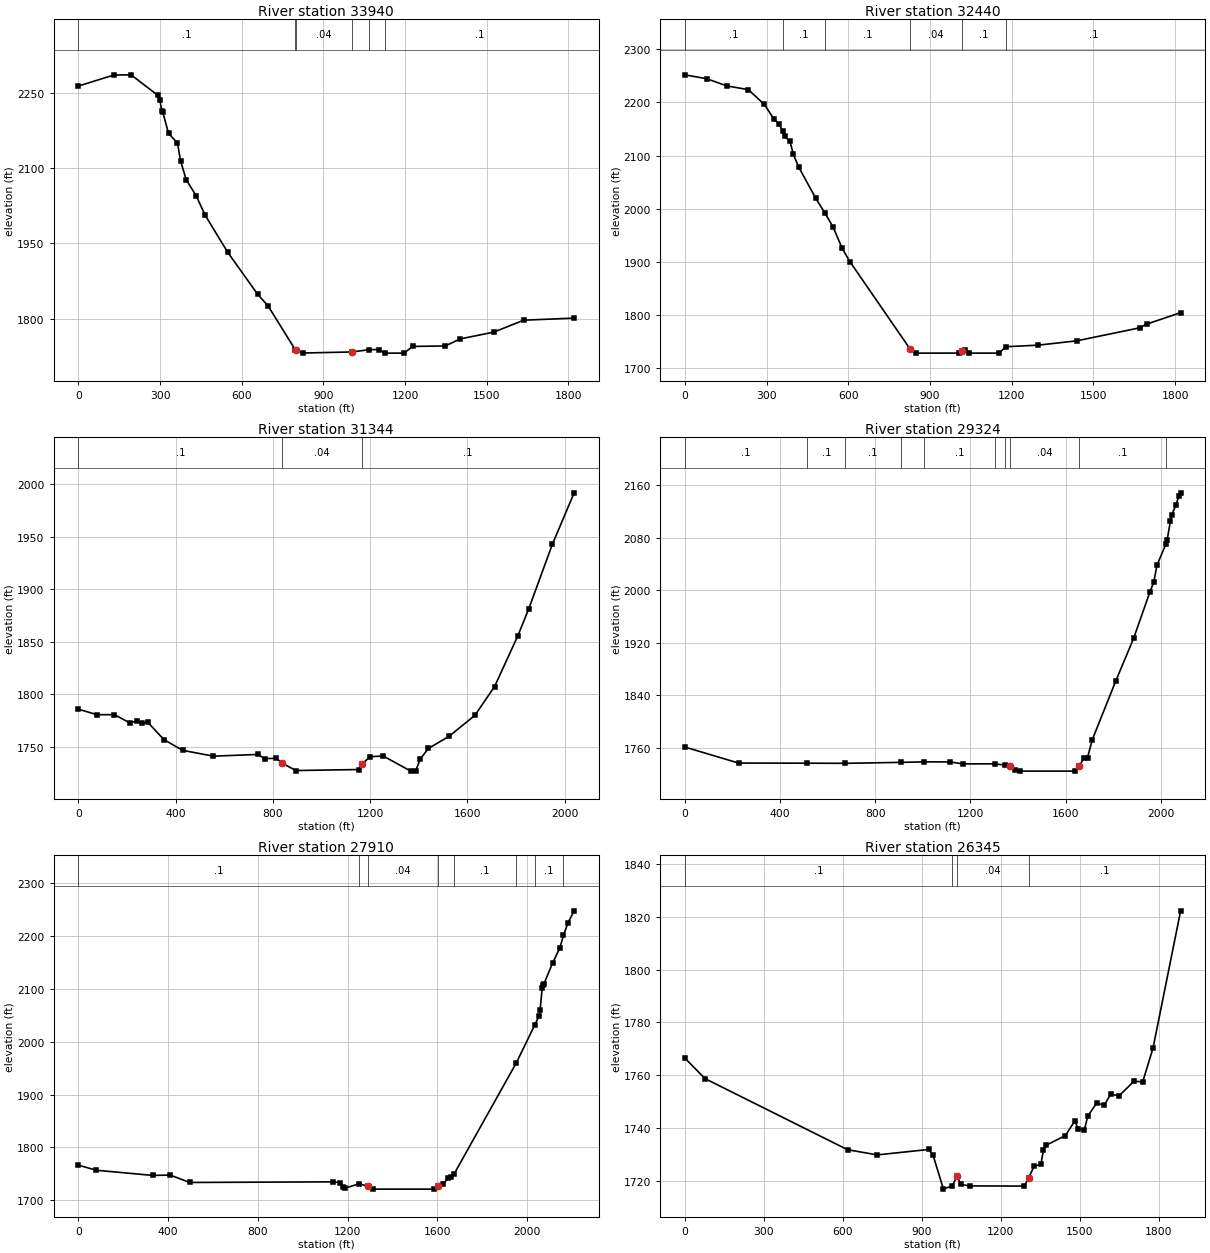
Type RM Length L Ch R = 1 ,33940   ,1565,1500,1429.6
XS GIS Cut Line= 3
     2155067.702      306004.425     2155354.125      306867.904
     2155625.586      307737.992
#Sta/Elev= 30
       0 2263.99   130.2 2286.02   193.7 2286.44   292.7 2245.21   299.6 2236.11
   306.5 2214.41     310  2212.6   331.2 2169.63     364 2150.48   375.7 2114.51
   396.1 2077.21   432.5 2045.46   465.5 2006.63   548.5 1932.39   659.1 1848.18
     697 1825.29   797.4 1737.25   798.4 1736.97     825  1731.3  1004.4 1733.39
 1069.121737.962  1103.9 1738.13 1125.681731.089  1196.7 1731.06  1227.6 1744.43
  1347.9  1745.4  1402.5 1759.37  1526.6 1773.08  1635.7  1796.8  1821.2 1800.93
#Mann= 6 ,-1 , 0
       0      .1       0   797.4      .1       0   798.4     .04       0
  1004.4      .1       0 1069.12      .1       0 1125.68      .1       0
Bank Sta=798.4,1004.4
XS Rating Curve= 0 ,0
Exp/Cntr=0.3,0.1

Type RM Length L Ch R = 1 ,32440   ,1110.8,1095.5,1081.9
XS GIS Cut Line= 3
     2153478.544      307310.072     2154237.834      307811.648
     2154997.125      308313.223
#Sta/Elev= 30
       0 2252.03    80.6 2244.67   154.5 2231.17   233.2 2224.15   292.2 2196.21
   327.6 2168.51   345.8 2159.81  358.912146.574   367.4 2136.23     386 2126.75
   398.3 2102.67     418 2078.57   480.9 2019.46     5141992.322   544.7  1965.4
   577.8 1925.34   606.2 1900.46   826.4 1736.56   850.1 1728.44  1006.4 1728.49
  1018.2 1732.52  1030.1 1734.69  1043.2 1728.47  1153.2 1728.47 1178.751740.485
  1297.6 1743.46  1438.8  1751.6  1669.4 1775.96  1695.4 1783.01    1820 1804.59
#Mann= 6 ,-1 , 0
       0      .1       0  358.91      .1       0     514      .1       0
   826.4     .04       0  1018.2      .1       0 1178.75      .1       0
Bank Sta=826.4,1018.2
XS Rating Curve= 0 ,0
Exp/Cntr=0.3,0.1

Type RM Length L Ch R = 1 ,31344   ,1826.7,2020.1,2167.4
XS GIS Cut Line= 4
2152829.50362101308310.3470150012153642.33053801308733.872619123
2153774.94966657308798.0431652022154643.39105684 309242.95895135
#Sta/Elev= 30
       0 1785.94    76.9 1780.65   148.5  1780.7   211.8 1772.87   243.1 1774.81
   263.2 1772.54   285.4 1773.54   351.9 1756.98   429.6 1746.68   555.4 1741.19
   739.3 1742.81   766.3  1738.8   814.4 1739.18     839 1734.35   895.8  1727.5
  1155.9 1728.45  1166.9 1733.65  1200.1 1740.64  1254.4 1741.34  1367.4 1726.93
  1388.1 1727.38  1406.6 1738.44  1439.7 1748.48  1524.5    1760  1631.4 1780.03
  1712.3 1807.46  1808.4 1855.98  1852.6 1881.28  1950.2 1943.02  2039.7 1991.93
#Mann= 3 ,-1 , 0
       0      .1       0     839     .04       0  1166.9      .1       0
Bank Sta=839,1166.9
XS Rating Curve= 0 ,0
Exp/Cntr=0.3,0.1

Type RM Length L Ch R = 1 ,29324   ,1312.9,1414.3,1499.4
XS GIS Cut Line= 2
 2152260.5247791308254.7325417322152286.19299754  310338.1362711
#Sta/Elev= 30
       0 1761.01   225.7  1736.6  514.271736.397  675.131736.175  908.311737.667
 1006.821738.433  1114.9 1738.33  1167.4 1735.34 1302.351735.407 1346.361733.471
  1367.5 1731.87  1387.2 1725.65  1406.9  1724.3  1639.8 1724.31  1658.4 1732.15
  1675.9 1743.84  1692.3  1744.8  1712.4  1772.2  1810.4  1861.1  1885.9 1926.44
  1954.8 1997.55  1970.7 2012.12  1984.3 2038.15 2021.982070.479    2027 2076.55
  2040.5    2105  2046.7 2114.88  2063.1  2129.1  2076.2 2143.08  2083.6 2148.31
#Mann= 10 ,-1 , 0
       0      .1       0  514.27      .1       0  675.13      .1       0
  908.31      .1       0 1006.82      .1       0 1302.35    .055       0
 1346.36      .1       0  1367.5     .04       0  1658.4      .1       0
 2021.98      .1       0
Bank Sta=1367.5,1658.4
XS Rating Curve= 0 ,0
Exp/Cntr=0.3,0.1

Type RM Length L Ch R = 1 ,27910   ,1433,1564.7,1672.7
XS GIS Cut Line= 2
2151875.50150263308023.7185758482150596.36861745309824.771902467
#Sta/Elev= 30
       0 1766.47    79.8 1756.82   330.8 1747.05   410.1 1747.58   495.8 1733.71
  1134.8 1734.87  1167.8 1733.24    1179 1724.55  1186.6 1722.66 1251.281731.242
  1292.4 1726.19  1313.6  1721.1  1586.6  1721.1    1603 1726.19  1626.6 1730.16
  1645.4 1741.58  1661.9 1743.14 1675.041750.381 1950.491959.243 2033.292031.158
  2053.1 2049.19  2057.3 2059.61  2066.6 2101.34  2068.9 2107.92  2074.3 2109.14
  2113.4 2149.01  2145.6 2177.43 2161.45 2201.08  2181.8    2225  2209.1  2247.4
#Mann= 8 ,-1 , 0
       0      .1       0 1251.28      .1       0  1292.4     .04       0
    1603      .1       0 1675.04      .1       0 1950.49      .1       0
 2033.29      .1       0 2161.45      .1       0
Bank Sta=1292.4,1603
XS Rating Curve= 0 ,0
Exp/Cntr=0.3,0.1

Type RM Length L Ch R = 1 ,26345   ,1431.6,1405.4,1373.7
XS GIS Cut Line= 2
2151370.69320681307796.982646368 2149501.1912977308027.996612253
#Sta/Elev= 30
       0 1766.51    76.8 1758.69   618.3 1731.75   731.2 1729.78   926.4 1731.84
   942.9 1729.76   982.6 1716.81 1016.481718.079  1034.3 1721.75  1048.3 1718.61
  1081.7 1718.03    1290 1717.97  1306.5 1721.17  1327.4 1725.49  1352.8 1726.21
  1362.7 1731.66  1372.6 1733.44  1445.4 1737.08  1481.7 1742.63  1494.9 1739.53
  1518.1 1739.38  1531.3 1744.54  1564.4 1749.38  1594.1 1748.64  1617.3 1752.75
  1650.3 1752.21  1706.5 1757.71  1739.6 1757.45  1778.7 1770.21  1883.7 1822.28
#Mann= 4 ,-1 , 0
       0      .1       0 1016.48      .1       0  1034.3     .04       0
  1306.5      .1       0
Bank Sta=1034.3,1306.5
XS Rating Curve= 0 ,0
Exp/Cntr=0.3,0.1

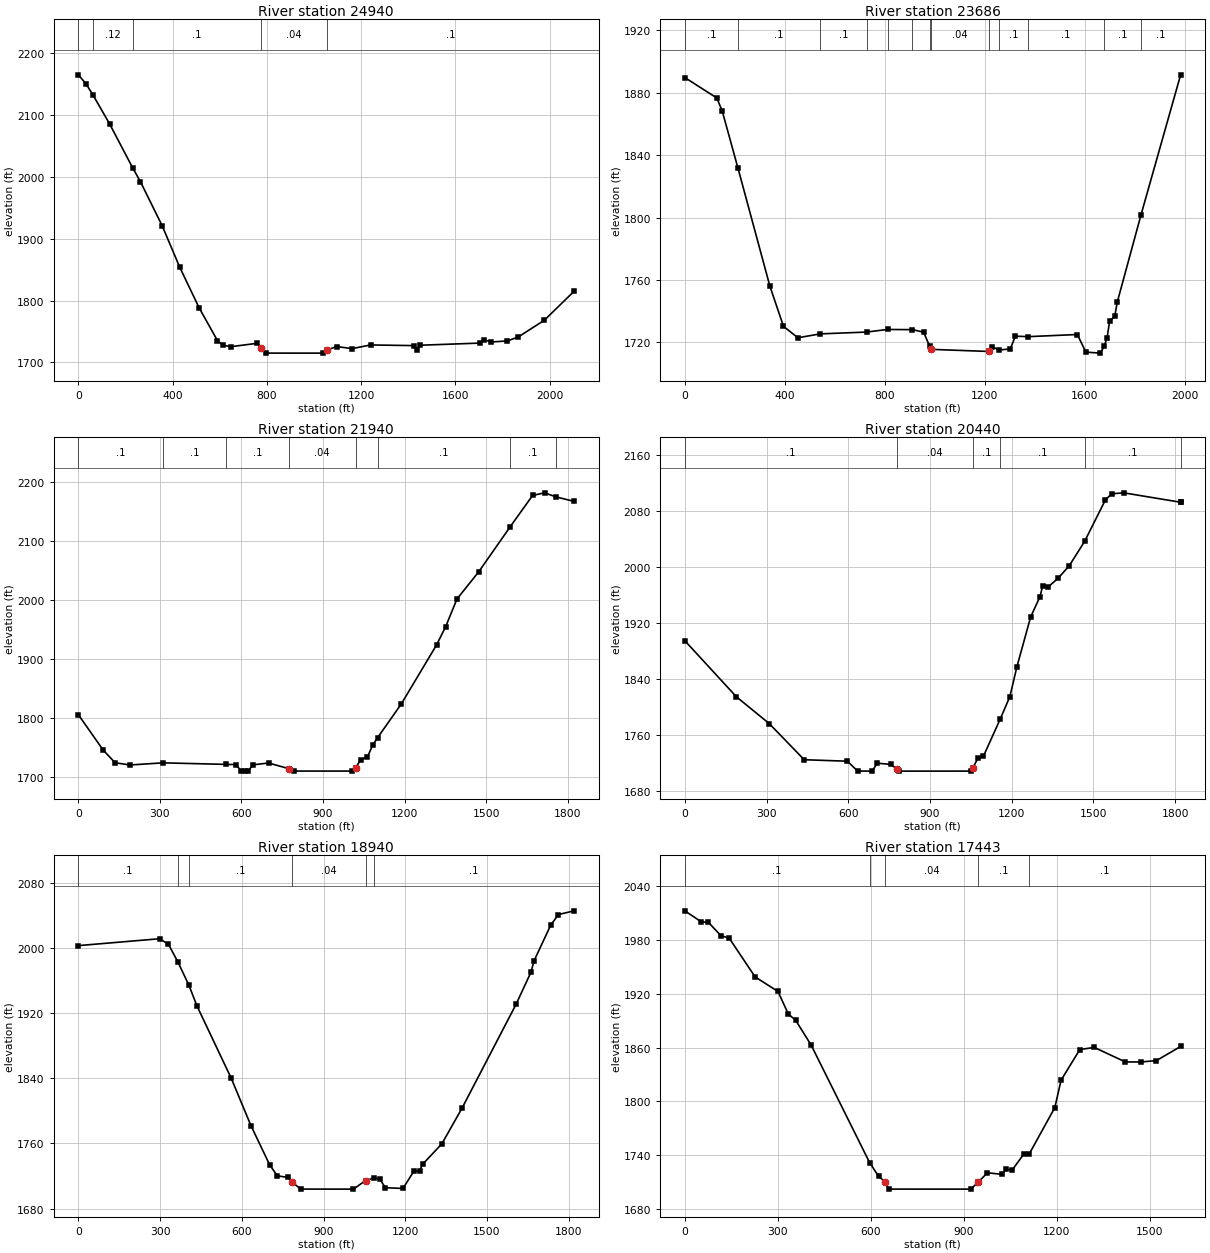
Type RM Length L Ch R = 1 ,24940   ,1242.5,1253.9,1262.2
XS GIS Cut Line= 3
     2150817.911      306271.561     2149958.274      306570.097
2148829.12070647306958.471764511
#Sta/Elev= 30
       0 2165.28    32.6 2150.72   63.15 2132.02   132.6 2085.98  230.352015.002
   263.3 1992.57   356.8 1920.32   429.7 1854.54   513.1    1788   590.3 1735.47
   613.8 1727.72   648.5 1725.59   759.7    1731     777  1723.2   794.4 1715.12
  1037.4 1715.09  1053.8 1719.99  1096.4 1725.69  1162.3 1722.41  1240.3 1728.33
  1422.5 1727.25  1436.4 1720.88  1450.2 1727.86  1703.5 1731.33  1723.1 1736.68
  1752.1 1733.09  1820.5 1734.82  1866.6 1741.17  1977.6 1768.29  2104.1 1815.32
#Mann= 5 ,-1 , 0
       0      .1       0   63.15     .12       0  230.35      .1       0
     777     .04       0  1053.8      .1       0
Bank Sta=777,1053.8
XS Rating Curve= 0 ,0
Exp/Cntr=0.3,0.1

Type RM Length L Ch R = 1 ,23686   ,1564.5,1746.1,1882.7
XS GIS Cut Line= 2
2150652.04514281305092.1975563382148736.81015585305607.045671113
#Sta/Elev= 30
       0 1889.77   128.3 1876.63   150.1 1868.08  212.341831.855   340.3    1756
   394.7 1730.21   452.4 1722.89  541.781725.373  727.061726.543   810.81728.206
  910.651728.081   955.2 1726.47   979.8  1717.3   985.8 1715.44  1216.8  1714.1
  1230.4 1717.18  1255.5 1715.03  1301.8 1715.69  1322.2 1723.92  1373.81723.598
  1570.2 1724.97  1604.1 1713.69  1661.9 1713.03 1677.151717.363  1689.1 1722.87
  1699.3 1733.61  1719.6 1736.62  1729.8 1745.77 1824.931801.818  1983.2 1891.51
#Mann= 13 ,-1 , 0
       0      .1       0  212.34      .1       0  541.78      .1       0
  727.06      .1       0   810.8     .12       0  910.65      .1       0
   979.8     .04       0   985.8     .04       0  1216.8     .04       0
  1255.5      .1       0  1373.8      .1       0 1677.15      .1       0
 1824.93      .1       0
Bank Sta=985.8,1216.8
XS Rating Curve= 0 ,0
Exp/Cntr=0.3,0.1

Type RM Length L Ch R = 1 ,21940   ,1489.9,1500,1513.6
XS GIS Cut Line= 3
     2150671.885      304738.583     2150171.031      303973.341
     2149606.152       303260.92
#Sta/Elev= 30
       0 1805.98    91.2 1746.28   135.2  1724.7   190.1 1720.92  311.161724.522
  543.471721.931     580 1721.63   597.9 1711.26   612.4 1710.53   625.4 1710.82
   641.6 1721.15   699.9 1724.26   774.4 1714.65     794 1710.62  1007.7 1710.61
  1020.3 1715.72  1037.9 1729.82  1063.6  1734.6  1083.1 1754.75 1101.031767.247
  1187.8 1824.04  1317.6 1923.91  1351.1 1954.79  1392.8 2001.71  1472.3 2047.38
 1588.262123.662  1670.8 2176.75  1715.1 2181.23 1755.252174.629  1823.8 2166.68
#Mann= 8 ,-1 , 0
       0      .1       0  311.16      .1       0  543.47      .1       0
   774.4     .04       0  1020.3      .1       0 1101.03      .1       0
 1588.26      .1       0 1755.25      .1       0
Bank Sta=774.4,1020.3
XS Rating Curve= 0 ,0
Exp/Cntr=0.3,0.1

Type RM Length L Ch R = 1 ,20440   ,1551.6,1500,1434.3
XS GIS Cut Line= 3
     2151956.232      304084.338      2151506.01      303293.515
     2151055.789      302502.692
#Sta/Elev= 30
       0 1894.49   189.5 1814.35   309.9 1776.19   438.2 1724.55   596.8 1722.42
   634.5 1708.34   687.6 1708.29   706.7 1719.62   755.3  1717.9     778 1711.54
   785.5 1708.27  1049.8 1708.31  1057.4 1713.21  1076.2 1726.75  1096.4 1729.73
  1157.91782.732  1193.3 1814.71  1219.1 1857.33  1269.6 1928.49  1303.3 1956.91
  1314.1 1973.27    1333 1971.06  1370.7 1983.76  1411.6 2001.71 1467.732036.376
  1543.9 2095.49    1567 2104.22  1611.3 2105.58 1819.572092.164    1820 2092.17
#Mann= 6 ,-1 , 0
       0      .1       0     778     .04       0  1057.4      .1       0
  1157.9      .1       0 1467.73      .1       0 1819.57      .1       0
Bank Sta=778,1057.4
XS Rating Curve= 0 ,0
Exp/Cntr=0.3,0.1

Type RM Length L Ch R = 1 ,18940   ,1535.2,1496.8,1418.1
XS GIS Cut Line= 3
     2153406.656      302909.218     2152668.159      302377.502
     2151929.662      301845.785
#Sta/Elev= 30
       0 2003.08   298.3 2011.53   330.7 2004.75  365.591982.893  406.011954.333
   435.7 1928.76   561.1 1840.17   633.8 1781.73     702 1733.87   730.2 1720.22
   770.2 1718.11   785.5 1712.35   815.8 1703.88  1009.9 1703.82  1054.3  1714.4
 1085.861717.467  1106.3 1716.33  1127.1 1705.56  1191.7 1704.65  1230.9  1725.5
  1252.4 1726.46  1264.5 1734.61  1334.3 1759.49  1408.8 1803.55    1607 1931.14
  1661.5 1970.46  1672.8 1984.46  1733.9 2028.16  1762.1 2041.25    1820 2045.83
#Mann= 6 ,-1 , 0
       0      .1       0  365.59      .1       0  406.01      .1       0
   785.5     .04       0  1054.3      .1       0 1085.86      .1       0
Bank Sta=785.5,1054.3
XS Rating Curve= 0 ,0
Exp/Cntr=0.3,0.1

Type RM Length L Ch R = 1 ,17443   ,1125.5,1072.2,970.4
XS GIS Cut Line= 2
2153902.19924327301167.6282812132152333.58589467300850.736695637
#Sta/Elev= 30
       0 2012.38      53 2000.21    76.4 1999.45   116.6 1984.72   143.3 1981.94
     227 1938.74   300.7 1922.56   334.1 1897.42   357.6 1890.52   407.8 1862.81
  596.611731.778   625.3 1716.65   645.4 1710.74   658.8 1702.34   923.2 1702.31
   946.4  1709.9   976.8 1720.56  1023.6 1718.74    1037 1724.36  1057.1 1723.79
  1093.9 1741.28 1111.841741.604  1194.3 1793.21  1214.4 1823.67    1275 1857.82
  1321.5  1860.2  1421.9 1844.03  1472.1 1843.96  1522.4 1845.54  1600.3 1861.28
#Mann= 5 ,-1 , 0
       0      .1       0  596.61      .1       0   645.4     .04       0
   946.4      .1       0 1111.84      .1       0
Bank Sta=645.4,946.4
XS Rating Curve= 0 ,0
Exp/Cntr=0.3,0.1

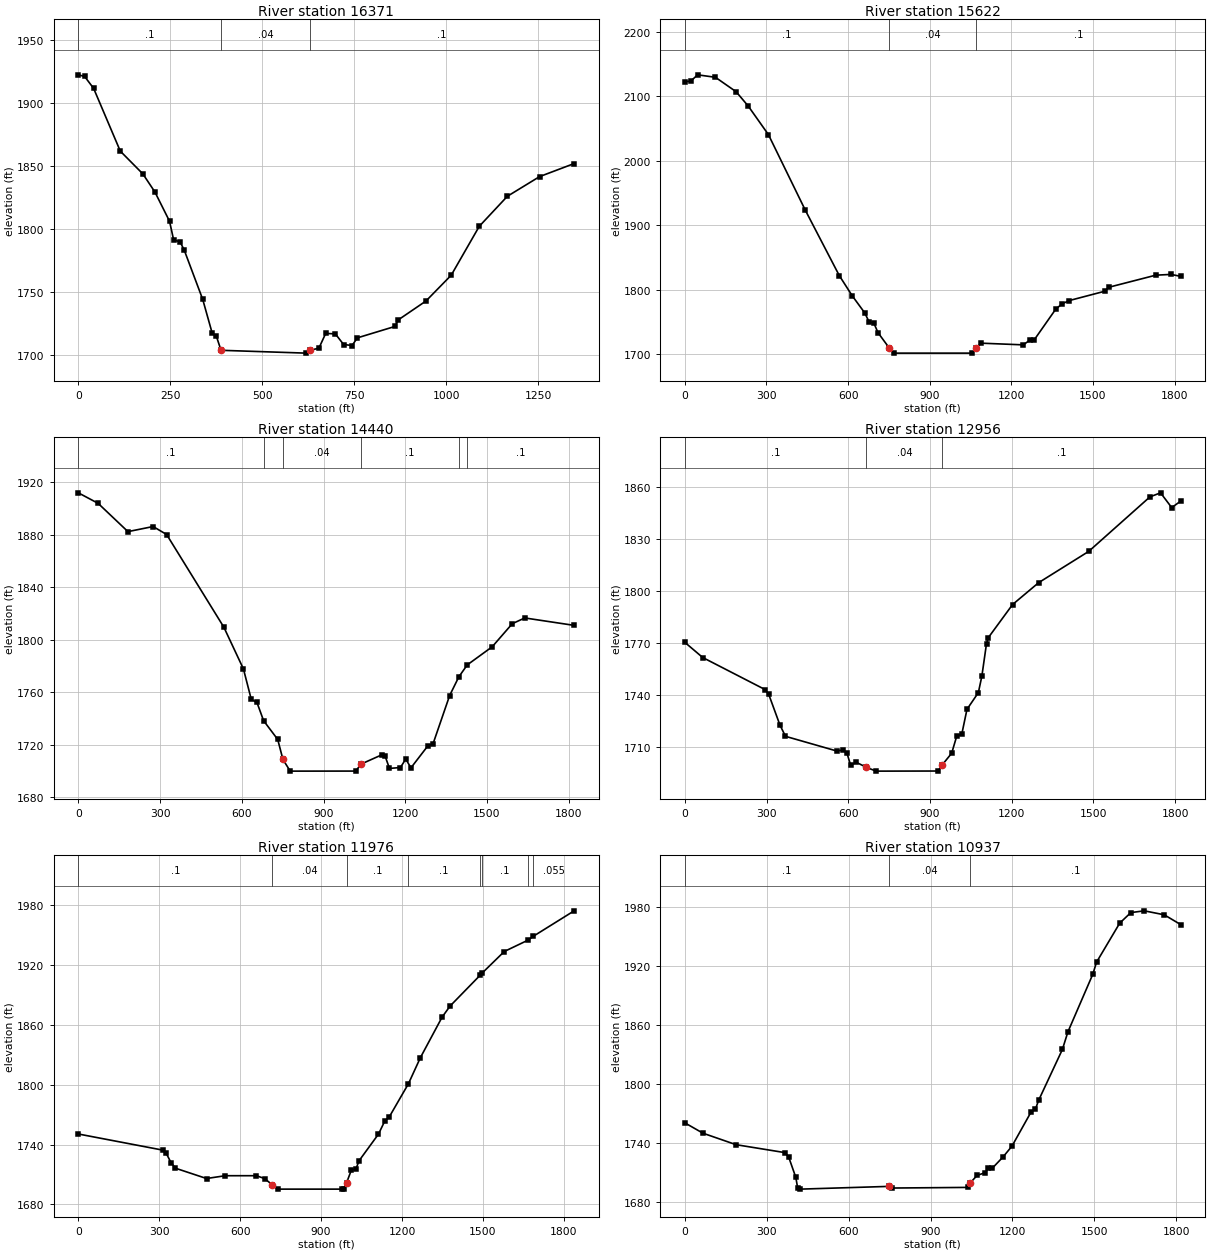
Type RM Length L Ch R = 1 ,16371   ,754,748.8,720
XS GIS Cut Line= 4
 2153602.5276627299735.5900689672153295.12725637299878.762860954
 2152697.1703016300144.0536225782152377.13700186300295.648343506
#Sta/Elev= 30
       0 1922.16    17.1 1920.87    41.6  1911.4     114 1861.74   175.5 1843.64
   208.1 1829.36   247.9 1806.18     259 1791.38   276.3 1789.95   287.7 1783.41
   338.1 1744.23   363.5 1717.82   375.3 1714.94   387.8 1703.99   618.3 1701.75
   629.5 1703.94   653.8 1705.71   672.2 1717.37   698.5 1716.99   720.9 1708.57
   743.9 1707.79   758.3 1713.85   860.2 1722.87   869.6 1728.12   944.7 1743.03
  1013.4  1763.5  1089.6 1802.21  1165.8 1825.95  1253.3 1841.53  1347.4  1851.9
#Mann= 3 , 0 , 0
       0      .1       0   387.8     .04       0   629.5      .1       0
Bank Sta=387.8,629.5
XS Rating Curve= 0 ,0
Exp/Cntr=0.3,0.1

Type RM Length L Ch R = 1 ,15622   ,1227.9,1182.2,1114.6
XS GIS Cut Line= 3
2153495.05516446298763.6327898112152769.41916446299312.011789811
2152005.41616446299811.139789811
#Sta/Elev= 30
       0 2122.41   22.03  2123.4   47.22  2133.1  112.52 2129.27   188.7 2106.86
  233.29 2084.52  307.31 2040.34  443.01 1922.98  567.77 1821.62  615.73 1790.02
  660.97 1763.95  677.42  1749.8  694.77 1747.86  710.32 1732.91  751.44 1709.24
  767.89 1701.34 1056.71 1701.34  1070.4 1709.35 1089.89 1716.77 1243.96 1714.17
 1268.33  1721.6 1284.01 1721.85 1362.39 1769.07  1385.9  1777.7 1413.33 1782.95
 1542.63 1797.28 1558.34 1803.54 1730.77 1822.28 1786.78 1823.45 1822.14 1820.51
#Mann= 3 , 0 , 0
       0      .1       0  751.44     .04       0  1070.4      .1       0
Bank Sta=751.44,1070.4
XS Rating Curve= 0 ,0
Exp/Cntr=0.3,0.1

Type RM Length L Ch R = 1 ,14440   ,1520.4,1483.9,1449.4
XS GIS Cut Line= 3
     2152377.254      297745.458     2151913.992      298528.706
     2151444.359      299308.199
#Sta/Elev= 30
       0 1912.02    72.5 1904.03   182.1 1882.47   274.5 1886.35   324.1 1880.27
   534.2 1809.67   606.1 1777.84   634.8  1754.7   655.7 1752.34  680.071738.476
   731.9 1724.19     751 1708.96   777.7 1700.07  1018.3 1700.11  1037.5  1705.4
  1113.4 1712.44  1125.6 1711.76  1142.1 1702.12  1182.2 1702.83  1201.8 1709.23
    1221  1702.6  1283.9 1719.55  1301.8 1720.75    1363 1757.66 1396.911771.958
 1427.681780.982  1519.2 1794.78  1592.9 1812.36  1638.8 1816.73    1820 1811.07
#Mann= 6 ,-1 , 0
       0      .1       0  680.07      .1       0     751     .04       0
  1037.5      .1       0 1396.91     .05       0 1427.68      .1       0
Bank Sta=751,1037.5
XS Rating Curve= 0 ,0
Exp/Cntr=0.3,0.1

Type RM Length L Ch R = 1 ,12956   ,937.6,979.8,1007.2
XS GIS Cut Line= 2
2150795.60942468297150.9720574662150287.37869974 298898.97773266
#Sta/Elev= 30
       0 1770.39    65.7 1761.65   294.6 1743.21   308.2 1740.42   349.2 1722.83
   369.7  1716.3   557.7 1707.87   581.6 1708.44   595.2 1706.68   608.9 1699.68
   629.4 1701.36     667 1698.47   701.9 1696.28   930.1 1696.34   945.4 1699.93
   979.8 1706.58   998.4 1716.42  1016.9  1717.5    1036 1731.84  1077.8 1741.45
  1090.7 1750.97  1107.7 1769.66  1114.6 1773.13  1203.4 1792.12  1299.1  1804.7
  1482.8 1822.68  1707.8 1854.07  1746.7 1856.39  1787.7 1847.89  1820.4  1851.6
#Mann= 3 , 0 , 0
       0      .1       0     667     .04       0   945.4      .1       0
Bank Sta=667,945.4
XS Rating Curve= 0 ,0
Exp/Cntr=0.3,0.1

Type RM Length L Ch R = 1 ,11976   ,1011.9,1039.1,1057.7
XS GIS Cut Line= 2
2150152.16053377296723.7104337232149221.03437023298308.606031239
#Sta/Elev= 30
       0 1750.59   313.7 1734.41   325.1 1731.62   343.4 1722.02   360.2 1716.32
   475.2 1706.01   544.7 1708.81     660 1708.82   690.9 1705.94   719.7 1699.52
   739.9 1695.38   978.6 1695.38   983.3 1695.82   994.8 1701.95  1012.1 1714.37
  1029.1 1715.56  1040.9 1723.85  1112.8  1750.5  1136.8 1763.97  1151.7 1767.21
 1223.731800.892  1268.2 1827.09  1348.7 1867.67  1378.3 1878.76  1488.71909.318
 1498.231912.056  1579.1 1933.34 1666.841944.686 1686.711948.592  1838.2 1974.08
#Mann= 8 ,-1 , 0
       0      .1       0   719.7     .04       0   994.8      .1       0
 1223.73      .1       0  1488.7      .1       0 1498.23      .1       0
 1666.84      .1       0 1686.71    .055       0
Bank Sta=719.7,994.8
XS Rating Curve= 0 ,0
Exp/Cntr=0.3,0.1

Type RM Length L Ch R = 1 ,10937   ,1274.1,1338.4,1364.4
XS GIS Cut Line= 2
2149512.25893627296105.6011506912148344.38899285297496.347037512
#Sta/Elev= 30
       0 1760.37    66.6 1749.78   187.8 1738.09   367.8 1729.96     381  1725.1
   406.6 1704.78   413.6 1693.72   423.5 1692.81   749.1 1695.61   757.6 1693.92
  1036.1 1694.56  1044.7  1698.9  1070.3 1706.71  1100.4 1709.63    1111 1713.98
  1126.3 1714.12  1165.8 1725.64  1198.4 1736.62  1268.2 1771.34  1284.5 1774.49
  1296.2 1783.42  1383.1 1835.16  1403.3 1853.05  1494.5 1911.79  1508.1 1924.01
  1593.1 1963.84  1633.8 1974.54    1683 1976.34  1755.9 1972.32  1816.1 1962.38
#Mann= 3 , 0 , 0
       0      .1       0   749.1     .04       0  1044.7      .1       0
Bank Sta=749.1,1044.7
XS Rating Curve= 0 ,0
Exp/Cntr=0.3,0.1