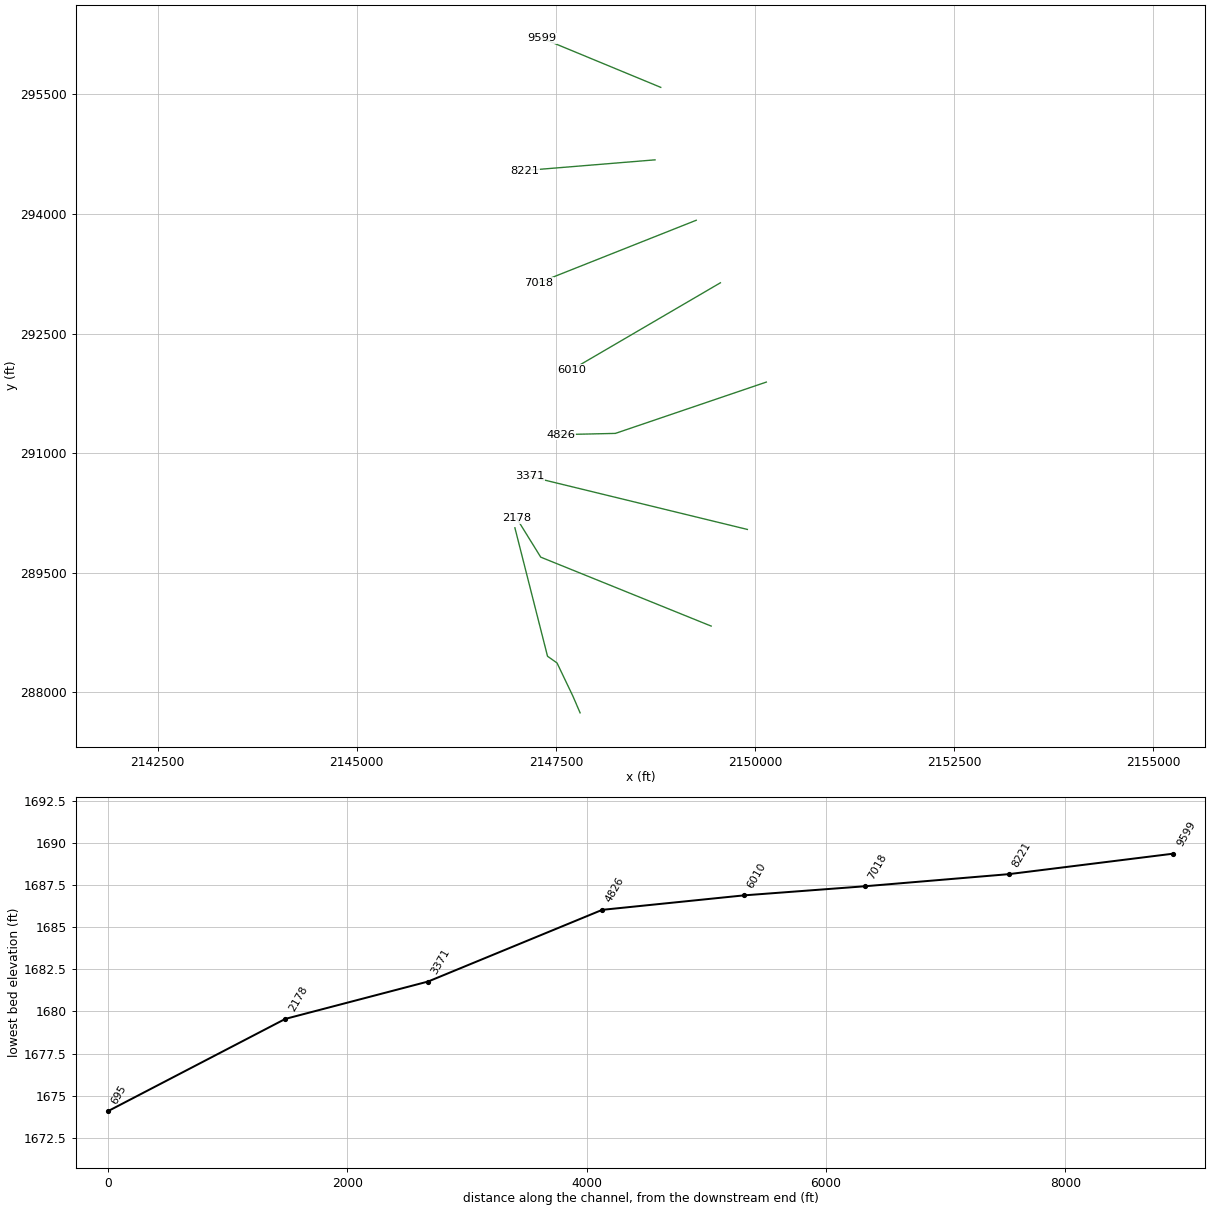
HEC-RAS study GRBRRV5.prj: GRBRRV5

--- GRBRRV5.g01 (geometry) --- (continued)

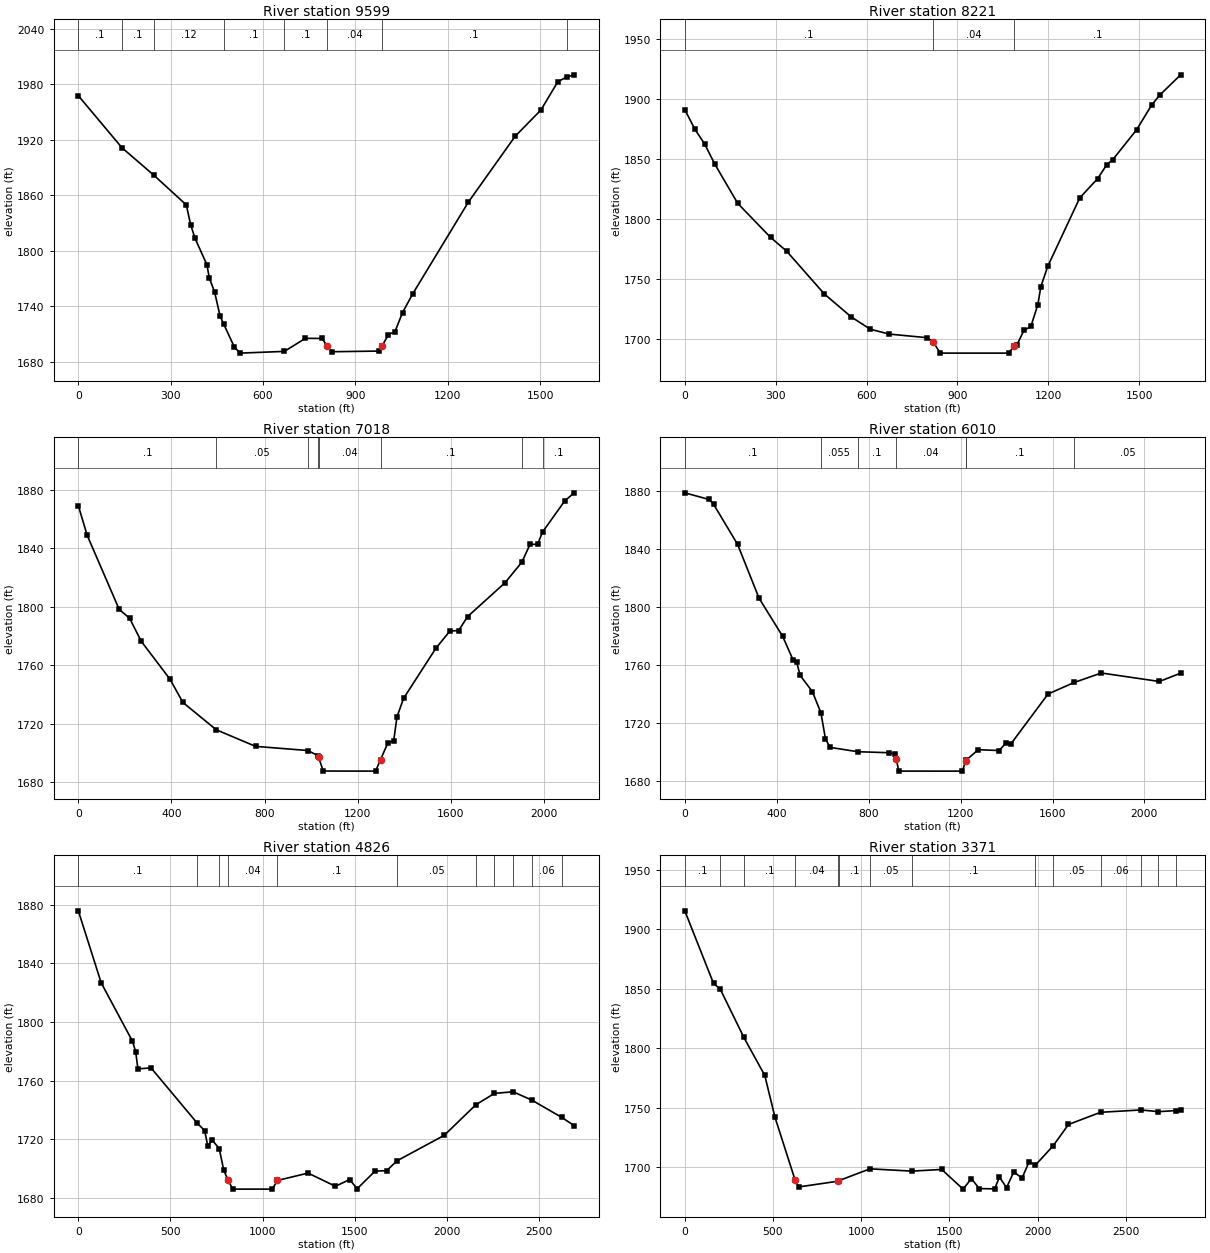
Type RM Length L Ch R = 1 ,9599    ,1314.1,1377.5,1415.9
XS GIS Cut Line= 2
2148816.88599286295588.5289620022147328.07469095296203.666565788
#Sta/Elev= 30
       0 1967.49  141.64 1911.29  246.03 1881.37   350.8 1849.52   364.9 1828.15
   379.2 1813.26   417.7 1784.96   425.3 1770.99   442.8 1755.21   460.8 1729.13
  472.981720.325     507 1695.85   525.7 1689.38  669.561691.264   737.7 1705.37
   791.9 1705.23   808.7 1696.93   822.9 1690.88   975.3  1691.6   986.2 1696.79
  1007.5 1709.41  1028.8  1712.7  1053.2 1733.08  1085.8 1753.12  1266.8 1852.33
  1419.3 1923.69  1502.8 1951.97  1557.7 1982.49 1586.221987.675  1610.9 1990.03
#Mann= 8 ,-1 , 0
       0      .1       0  141.64      .1       0  246.03     .12       0
  472.98      .1       0  669.56      .1       0   808.7     .04       0
   986.2      .1       0 1586.22     .05       0
Bank Sta=808.7,986.2
XS Rating Curve= 0 ,0
Exp/Cntr=0.3,0.1

Type RM Length L Ch R = 1 ,8221    ,1156.1,1202.8,1235.2
XS GIS Cut Line= 2
2148745.56569098294679.1951129272147114.11378528294545.469546886
#Sta/Elev= 30
       0 1891.14    33.2  1874.8    66.1  1862.2    98.8 1845.79   174.8 1812.96
   283.4 1784.55   336.1 1773.18   460.8 1737.43     550 1718.23   612.5 1708.08
   675.1 1704.02   800.2 1701.02   820.1 1697.62     843 1688.17  1070.1 1688.16
  1086.6 1694.24  1096.4 1694.99  1119.5 1707.09  1142.5 1710.36  1165.6 1728.67
  1175.5 1743.69  1198.5 1760.66  1303.8 1817.51  1363.1 1833.64  1392.7 1845.08
  1413.1 1849.49  1491.5 1874.29  1540.8 1894.76  1567.2 1903.03  1636.9 1920.11
#Mann= 3 , 0 , 0
       0      .1       0   820.1     .04       0  1086.6      .1       0
Bank Sta=820.1,1086.6
XS Rating Curve= 0 ,0
Exp/Cntr=0.3,0.1

Type RM Length L Ch R = 1 ,7018    ,986.3,1008.5,1028.4
XS GIS Cut Line= 2
2149262.63787967293921.4169053642147283.49950227293136.893584594
#Sta/Elev= 30
       0 1869.09    37.7 1848.93   175.3 1798.18   220.1 1792.01   270.6 1776.17
   394.2 1750.24   448.8 1734.47  592.231715.734     761 1704.38  985.241701.547
  1029.4 1698.02  1031.4 1697.06  1051.6  1687.5  1276.5 1687.44  1297.6 1695.36
  1329.6 1706.85  1354.1 1708.22  1368.2 1724.56  1396.4 1737.18    1535 1771.45
    1595 1783.23    1633 1783.67  1671.7 1793.25  1831.7 1816.27 1904.281830.396
  1939.9 1842.74  1971.7 1842.58 1993.32 1851.09  2088.2 1872.27    2129 1877.89
#Mann= 8 ,-1 , 0
       0      .1       0  592.23     .05       0  985.24      .1       0
  1029.4      .1       0  1031.4     .04       0  1297.6      .1       0
 1904.28     .06       0 1993.32      .1       0
Bank Sta=1031.4,1297.6
XS Rating Curve= 0 ,0
Exp/Cntr=0.3,0.1

Type RM Length L Ch R = 1 ,6010    ,1205.8,1183.7,1153.2
XS GIS Cut Line= 2
2149565.74916269293136.8935845942147702.50627586292049.258980799
#Sta/Elev= 30
       0 1878.99     106 1874.39   125.5 1871.01   229.7 1843.42   323.2 1806.22
   425.8 1779.95   471.3  1763.6   486.5 1762.37   501.7 1753.02     555  1741.8
  592.251727.225   611.9 1709.28   631.7 1703.31  751.781700.305   889.2  1699.6
   915.8 1698.52   919.8 1695.53     931 1686.91  1208.3  1686.9  1221.8 1694.07
  1223.5 1694.33  1276.7 1701.68  1367.9 1701.12  1396.9 1706.25  1417.3 1705.32
  1580.6 1740.13  1695.5 1748.16  1812.3 1754.63  2064.9 1748.78  2157.5 1754.51
#Mann= 7 ,-1 , 0
       0      .1       0  592.25    .055       0  751.78      .1       0
   919.8     .04       0  1221.8      .1       0  1223.5      .1       0
  1695.5     .05       0
Bank Sta=919.8,1221.8
XS Rating Curve= 0 ,0
Exp/Cntr=0.3,0.1

Type RM Length L Ch R = 1 ,4826    ,1518.9,1454.8,1370.1
XS GIS Cut Line= 3
2150142.34550918 291891.491893512148247.70444681291247.931750041
2147557.80797301291232.486306598
#Sta/Elev= 30
       0 1875.71   124.1  1826.6   293.6 1786.91   311.2 1779.69   323.3 1767.98
   394.5 1768.68   644.71731.105   685.4 1725.92   702.8 1715.43     727 1719.43
  764.741713.625   789.4 1698.84   813.5    1692   837.9 1686.04  1052.7 1686.05
  1080.4 1691.94  1246.8 1696.97  1395.7 1687.96    1472 1692.57  1513.6 1686.34
  1610.6 1698.35  1672.9 1698.57  1729.51705.333    1986 1722.71 2157.441743.535
 2258.46 1751.28 2359.481752.387  2460.51746.762 2623.371734.947    2691 1729.32
#Mann= 11 ,-1 , 0
       0      .1       0   644.7     .06       0  764.74      .1       0
   813.5     .04       0  1080.4      .1       0  1729.5     .05       0
 2157.44    .055       0 2258.46     .06       0 2359.48    .055       0
  2460.5     .06       0 2623.37     .05       0
Bank Sta=813.5,1080.4
XS Rating Curve= 0 ,0
Exp/Cntr=0.3,0.1

Type RM Length L Ch R = 1 ,3371    ,1210.4,1192.7,1174.8
XS GIS Cut Line= 2
2149904.52059666290043.3754901922147172.77234566290707.602755453
#Sta/Elev= 30
       0 1915.45   162.8 1854.55  201.011849.722  334.791809.151   453.6 1777.21
     511 1742.24   624.5 1689.84   646.3 1683.63   869.8 1688.46   875.6 1689.01
    10501698.833 1286.93 1696.89  1456.4  1698.3  1577.9 1681.78  1625.2 1690.66
  1669.1 1682.23  1756.9 1681.99  1783.9 1691.88  1824.4 1683.03  1864.9 1696.18
  1912.2  1691.1  1952.7 1704.88  1988.2 1702.02 2087.831718.027  2175.4 1736.06
  2357.6  1746.3 2585.981748.253 2685.611746.838 2785.241747.721  2811.3 1747.81
#Mann= 14 ,-1 , 0
       0      .1       0  201.01     .06       0  334.79      .1       0
   624.5     .04       0   869.8      .1       0   875.6      .1       0
    1050     .05       0 1286.93      .1       0  1988.2     .06       0
 2087.83     .05       0  2357.6     .06       0 2585.98    .055       0
 2685.61     .06       0 2785.24    .055       0
Bank Sta=624.5,869.8
XS Rating Curve= 0 ,0
Exp/Cntr=0.3,0.1

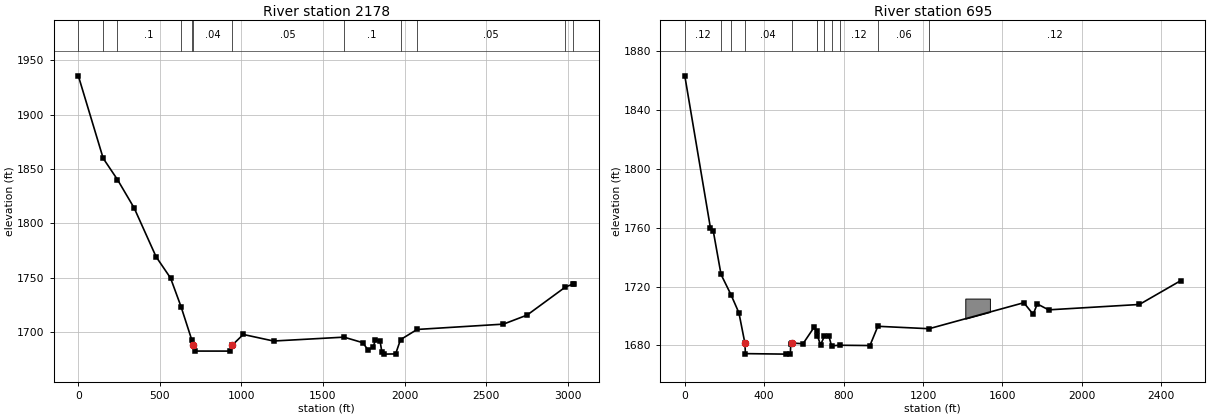
Type RM Length L Ch R = 1 ,2178    ,1580.4,1483.6,1397.1
XS GIS Cut Line= 3
2149449.85367212288830.9303580922147310.24461548289695.689018487
2147006.13312071290186.016093969
#Sta/Elev= 30
       0 1935.82  152.421859.854  239.751840.305   342.4  1814.1   476.8  1769.2
   565.3 1749.65  629.571723.334   696.2 1692.31   703.3 1688.39   713.9 1682.38
   929.8 1682.35   943.9 1687.89  1011.2 1697.67  1196.9 1691.63 1628.831695.199
  1743.8 1690.11  1775.5 1683.53  1806.7 1685.83  1821.5 1692.47  1849.8 1691.97
  1860.4 1681.89  1871.1 1679.56  1945.4 1679.75 1975.271692.889 2077.131702.283
  2606.4 1707.18  2751.6 1715.52 2985.741741.285  3035.51744.274    3040 1744.46
#Mann= 12 ,-1 , 0
       0      .1       0  152.42     .06       0  239.75      .1       0
  629.57     .12       0   696.2      .1       0   703.3     .04       0
   943.9     .05       0 1628.83      .1       0 1975.27    .035       0
 2077.13     .05       0 2985.74    .055       0  3035.5     .05       0
Bank Sta=703.3,943.9
XS Rating Curve= 0 ,0
Exp/Cntr=0.3,0.1

Type RM Length L Ch R = 1 ,695     ,528.8,490.3,443.2
XS GIS Cut Line= 5
     2147804.519      287742.606     2147713.729      287952.839
     2147515.081      288368.023     2147395.533       288452.56
     2146985.823      290063.704
#Sta/Elev= 30
       0 1863.33     129 1760.02   143.3 1757.92   182.6 1728.25   232.7 1714.47
   272.7 1702.13   302.9 1681.43   305.4 1674.41  510.51 1674.07   531.6 1674.41
   534.1 1681.21   538.2 1681.62   595.6 1681.14   650.9 1692.23   664.5 1689.86
   668.4 1686.38   684.2 1680.33   703.2 1686.31     726 1686.27   739.3 1679.71
   779.5 1680.11   932.8 1679.91   972.6    1693  1230.7 1691.35  1708.1 1709.03
  1755.3 1701.14  1775.8 1708.21  1832.9 1704.18  2290.3 1707.84  2498.1    1724
#Mann= 12 ,-1 , 0
       0     .12       0   182.6    .016       0   232.7     .12       0
   302.9     .04       0   538.2     .12       0   664.5     .08       0
   668.4     .04       0   703.2     .12       0   739.3     .04       0
   779.5     .12       0   972.6     .06       0  1230.7     .12       0
#Block Obstruct= 1 ,-1
 1413.16 1537.22 1711.86
Bank Sta=302.9,538.2
XS Rating Curve= 0 ,0
Exp/Cntr=0.3,0.1
LCMann Table=0

Chan Stop Cuts=-1
Use User Specified Reach Order=0
Composite Channel Slope=5